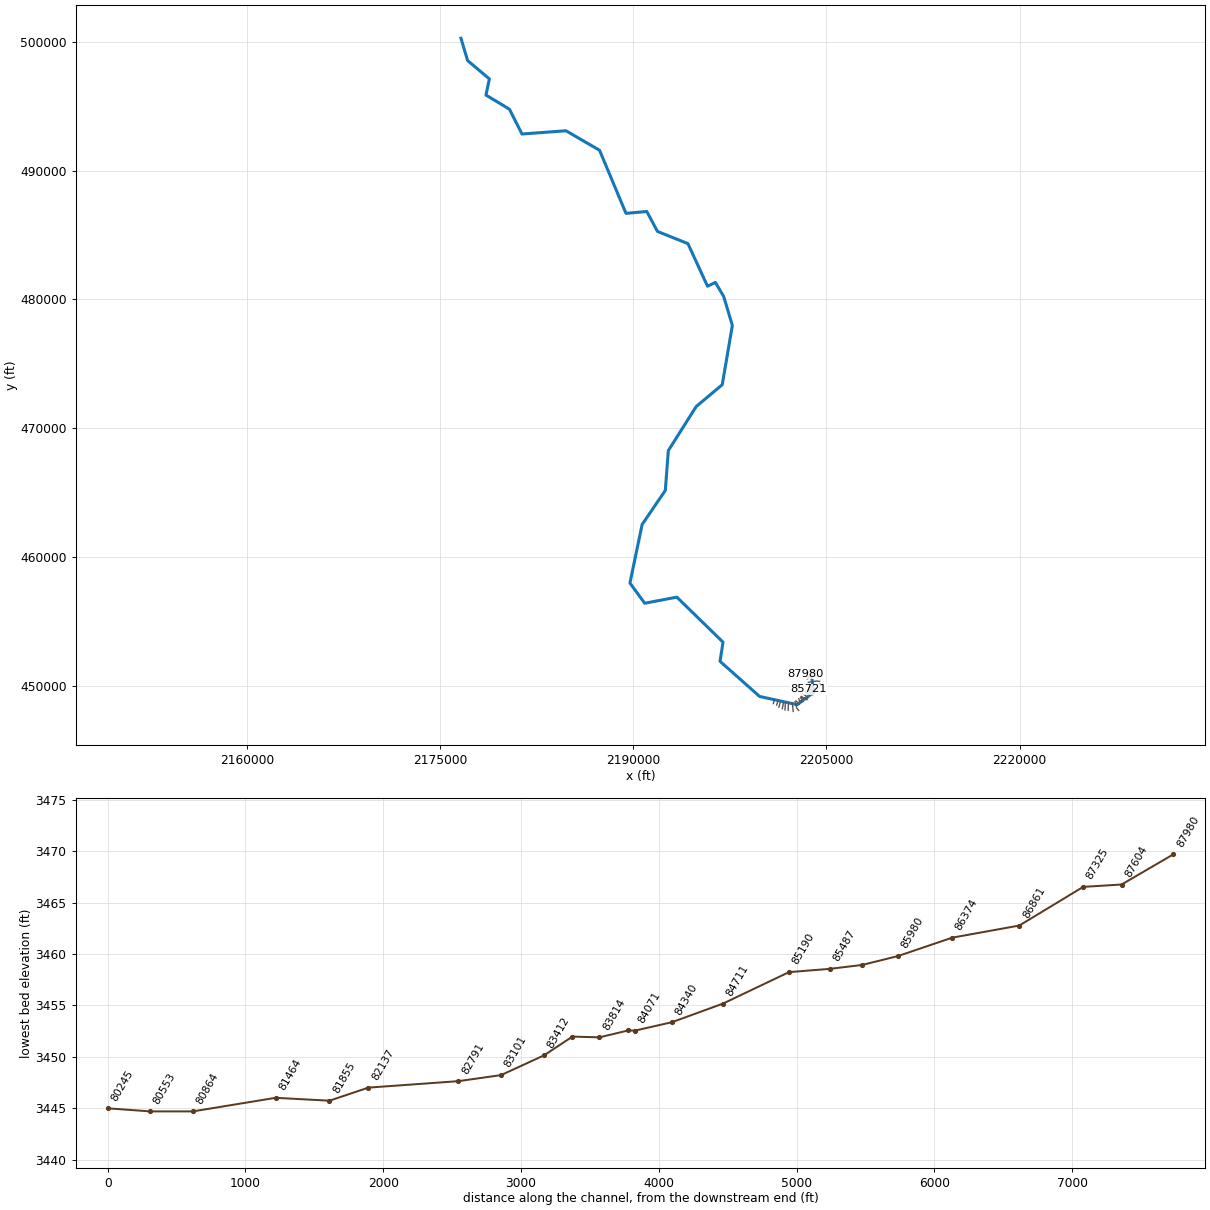
--- WILLIAMSRV.prj (project) ---

Proj Title=WILLIAMSRV
Current Plan=p01
Default Exp/Contr=0,0
English Units
Geom File=g01
Flow File=f01
Plan File=p01
Background Map Layer=Inundation Boundary (01pct Value_0)
BEGIN DESCRIPTION:
----------MODEL BY WOOD PLC 2021----------
Stream Name: Williams River
Flood Zone: Approximate
Pocahontas County, WV
HEC-RAS Version: RAS 6.1
Vertical Datum: NAVD88
Projection: NAD 1983 StatePlane West Virginia S FIPS 4702 (US Feet)
Terrain: 1-meter LIDAR (FEMA Region III 3DEP collected 2016-2018)
Land Use: 2019 NLCD
Hydrologic Method:
WV 2010 Regional Regression Equations
Model Notes:
Model extends county boundary at the downstream
END DESCRIPTION:
DSS Export Rating Curves= 0
DSS Export Rating Curve Sorted= 0
DSS Export Volume Flow Curves= 0
DXF Filename=..\CHARLESCK\CHARLESCK.
DXF OffsetX= 0
DXF OffsetY= 0
DXF ScaleX= 0
DXF ScaleY= 0

--- WILLIAMSRV.p01 (plan) ---

Plan Title=Floodplain
Program Version=6.00
Short Identifier=Floodplain
Geom File=g01
Flow File=f01
Subcritical Flow
K Sum by GR= 0
Std Step Tol= 0.01
Critical Tol= 0.01
Num of Std Step Trials= 20
Max Error Tol= 0.3
Flow Tol Ratio= 0.001
Split Flow NTrial= 30
Split Flow Tol= 0.02
Split Flow Ratio= 0.02
Log Output Level= 0
Friction Slope Method= 1
Unsteady Friction Slope Method= 2
Unsteady Bridges Friction Slope Method= 1
Parabolic Critical Depth
Global Vel Dist= 0 , 0 , 0
Global Log Level= 0
CheckData=True
Encroach Param=-1 ,0,0, 0
Mapping Interval=1HOUR
Computation Time Step Use Courant=        0
Computation Time Step Use Time Series=    0
Computation Time Step Count To Double=0
Computation Time Step Max Doubling=0
Computation Time Step Max Halving=0
Computation Time Step Residence Courant=0
Run HTab= 0
Run UNet= 0
Run Sediment= 0
Run PostProcess= 0
Run WQNet= 0
Run RASMapper=-1
UNET Theta= 0
UNET Theta Warmup= 0
UNET ZTol= 0
UNET ZSATol= 0
UNET MxIter= 0
UNET Max Iter WO Improvement= 0
UNET MaxInSteps= 0
UNET DtIC= 0
UNET DtMin= 0
UNET MaxCRTS= 0
UNET WFStab= 0
UNET SFStab= 0
UNET WFX= 1
UNET SFX= 1
UNET Gravity=32.174
UNET 1D Methodology=Finite Difference
UNET DSS MLevel= 1
UNET Pardiso=0
UNET DZMax Abort= 0
UNET Use Existing IB Tables= 0
UNET Froude Reduction=False
UNET Froude Limit= 0
UNET Froude Power= 0
UNET D1 Cores= 0
UNET WindReference=Eulerian
UNET WindDragFormulation=Hsu (1988)
UNET D2 Coriolis=0
UNET D2 Cores= 0
UNET D2 Theta= 1
UNET D2 Theta Warmup= 1
UNET D2 Z Tol= 0.01
UNET D2 Volume Tol= 0.01
UNET D2 Max Iterations= 20
UNET D2 Equation= 0
UNET D2 RampUpFraction=0.1
UNET D2 TimeSlices= 1
UNET D2 Turbulence Formulation=Non-Conservative (original)
UNET D2 Eddy Viscosity=0.3
UNET D2 Transverse Eddy Viscosity=0.1
UNET D2 Smagorinsky Mixing=0
UNET D2 BCVolumeCheck=0
UNET D2 Cores=0
UNET D2 SolverType=PARDISO (Direct)
UNET D2 Minimum Iterations= 2147483647
UNET D2 Maximum Iterations= 2147483647
UNET D2 Restart Number= 10
UNET D2 Relaxation Coeff=1.3
UNET D2 SOR Precondition Iterations= 10
UNET D2 ILUT Maximum Fill= 8
UNET D2 ILUT Tolerance=1E-08
UNET D1D2 MaxIter= 0
UNET D1D2 ZTol=0.01
UNET D1D2 QTol=0.1
UNET D1D2 MinQTol=1
Write IC File= 0
Write IC File at Fixed DateTime=0
Write IC File at Sim End=0
Echo Input=False
Echo Parameters=False
Echo Output=False
Write Detailed= 0
HDF Write Warmup=0
HDF Write Time Slices=0
HDF Flush=0
HDF Compression= 1
HDF Chunk Size= 1
HDF Spatial Parts= 1
HDF Use Max Rows=0
HDF Fixed Rows= 1
Calibration Method= 0
Calibration Iterations= 20
Calibration Max Change=0.05
Calibration Tolerance=0.2
Calibration Maximum=1.5
Calibration Minimum=0.5
Calibration Optimization Method= 1
WQ AD Non Conservative
WQ ULTIMATE=-1
WQ Max Comp Step=1HOUR
WQ Output Interval=15MIN
WQ Output Selected Increments= 0
WQ Output face flow=0
WQ Output face velocity=0
WQ Output face area=0
WQ Output face dispersion=0
WQ Output cell volume=0
WQ Output cell surface area=0
WQ Output cell continuity=0
WQ Output cumulative cell continuity=0
WQ Output face conc=0
WQ Output face dconc_dx=0
WQ Output face courant=0
WQ Output face peclet=0
WQ Output face adv mass=0
WQ Output face disp mass=0
WQ Output cell mass=0
WQ Output cell source sink temp=0
WQ Output nsm pathways=0
WQ Output nsm derived pathways=0
WQ Create Restart=0
WQ Fixed Restart=0
WQ System Summary=0
WQ Write To DSS=0
Sorting and Armoring Iterations= 10
XS Update Threshold= 0.02
Bed Roughness Predictor= 0
Hydraulics Update Threshold= 0.02
Energy Slope Method= 1
Volume Change Method= 1
Sediment Retention Method= 0
Sediment TS Multiplier= 1
Warm Up Method= 0
XS Weighting Method= 0
Number of US Weighted Cross Sections= 1
Number of DS Weighted Cross Sections= 1
Upstream XS Weight=0
Main XS Weight=1
Downstream XS Weight=0
Number of DS XS's Weighted with US Boundary= 1
Upstream Boundary Weight= 1
Weight of XSs Associated with US Boundary= 0
Number of US XS's Weighted with DS Boundary= 1
Downstream Boundary Weight= 0.5
Weight of XSs Associated with DS Boundary= 0.5
Percentile Method= 0
Sediment Output Level= 3
Mass or Volume Output= 0
Output Increment Type= 1
Profile and TS Output Increment= 1
Transport Output Increment 1
XS Output Flag= 0
XS Output Increment= 10
Read HDF5 Sediment Hotstart= 0
Sediment Hotstart Type= 0
Write Gradation File= 0
Read Gradation Hotstart= 0
Write HDF5 File= 1
Write Binary Output= 1
Write DSS Sediment File= 0
DSS Sediment Output Type= 1
SV Curve= 0
Specific Gage Flag= 0
Subcell Erosion Methods= 0
Subcell Deposition Methods= 0
Advection Scheme= 1
Matrix Solver= 0
Implicit Weighting Factor= 1
Maximum Outer Loop Convergence Iterations= 5
Convergence Maximum Absolute= 0.001
Convergence RMSE= 0.0001
Grain Fractions Max Abs Error= 0.001
Max Subgrid Regions= 1
Max Subgrid Length Scale= 3.402823E+38
Initial Layer Thickness= 3.402823E+38
Min Layer Thickness= 3.402823E+38
Max Layer Thickness= 3.402823E+38
Number of Layers= 5

--- WILLIAMSRV.f01 (steady flow) ---

Flow Title=Flow
Program Version=6.00
Number of Profiles= 6
Profile Names=01pct,10pct,04pct,02pct,0_2pct,01plus
River Rch & RM=WILLIAMSRV,Main            ,87980
     575     304     404     487     803     850
River Rch & RM=WILLIAMSRV,Main            ,82791
     969     523     688     824    1340    1430
River Rch & RM=WILLIAMSRV,Main            ,77773
    1370     747     977    1170    1880    2020
River Rch & RM=WILLIAMSRV,Main            ,76516
    1530     837    1090    1300    2090    2260
River Rch & RM=WILLIAMSRV,Main            ,70859
    1810     998    1300    1540    2470    2670
River Rch & RM=WILLIAMSRV,Main            ,63528
    2110    1170    1520    1800    2870    3120
River Rch & RM=WILLIAMSRV,Main            ,62377
    2410    1350    1740    2060    3270    3560
River Rch & RM=WILLIAMSRV,Main            ,53448
    2730    1530    1980    2340    3700    4040
River Rch & RM=WILLIAMSRV,Main            ,45382
    3450    1950    2510    2960    4650    5100
River Rch & RM=WILLIAMSRV,Main            ,34732
    4490    2570    3290    3870    6030    6640
River Rch & RM=WILLIAMSRV,Main            ,34489
    5120    2950    3760    4420    6870    7580
River Rch & RM=WILLIAMSRV,Main            ,28469
    5700    3290    4190    4920    7620    8430
River Rch & RM=WILLIAMSRV,Main            ,20081
    7070    4120    5220    6120    9420   10500
River Rch & RM=WILLIAMSRV,Main            ,14524
    8070    4720    5980    6990   10700   11900
Boundary for River Rch & Prof#=WILLIAMSRV,Main            , 1
Up Type= 0
Dn Type= 3
Dn Slope=0.01
Boundary for River Rch & Prof#=WILLIAMSRV,Main            , 2
Up Type= 0
Dn Type= 3
Dn Slope=0.01
Boundary for River Rch & Prof#=WILLIAMSRV,Main            , 3
Up Type= 0
Dn Type= 3
Dn Slope=0.01
Boundary for River Rch & Prof#=WILLIAMSRV,Main            , 4
Up Type= 0
Dn Type= 3
Dn Slope=0.01
Boundary for River Rch & Prof#=WILLIAMSRV,Main            , 5
Up Type= 0
Dn Type= 3
Dn Slope=0.01
Boundary for River Rch & Prof#=WILLIAMSRV,Main            , 6
Up Type= 0
Dn Type= 3
Dn Slope=0.01
DSS Import GetInterval= 0
DSS Import GetPeak= 0
DSS Import FillOption= 0

--- WILLIAMSRV.g01 (geometry) ---

Geom Title=Geometry
Program Version=6.10

River Reach=WILLIAMSRV      ,Main
Reach XY= 30
2203807.40824081451136.6289569742204002.18534918  449482.5029463
2202725.89939801448526.1065300262199813.50612365449162.107971638
2196740.21448199451892.4403274662196972.61906929453381.596569076
2193385.91587083456876.1052581072190893.45059304456401.774239585
2189746.30480142457972.2022280542190692.70776422462519.158357233
2192493.05619763465162.2327954922192725.78866467468253.013194654
2194890.38904328471677.2158178892196911.23708554473369.319645658
2197696.45417829477973.4122048912197023.13965715480225.178063229
2196379.49704222481316.6398802252195771.19735293481016.382145479
2194249.51397081484324.3316103222191883.46161635 485275.42485249
2191053.66635992486821.6117207412189439.04050104486678.102292836
2187385.90433849491577.0982727262184778.67103593 493090.67661041
 2181367.0751688492838.4048052432180391.20474525494764.456399322
2178568.72348209495863.8597123322178834.92472129497116.534700409
2177145.91956915498537.6745746432176627.81168149500275.048724562

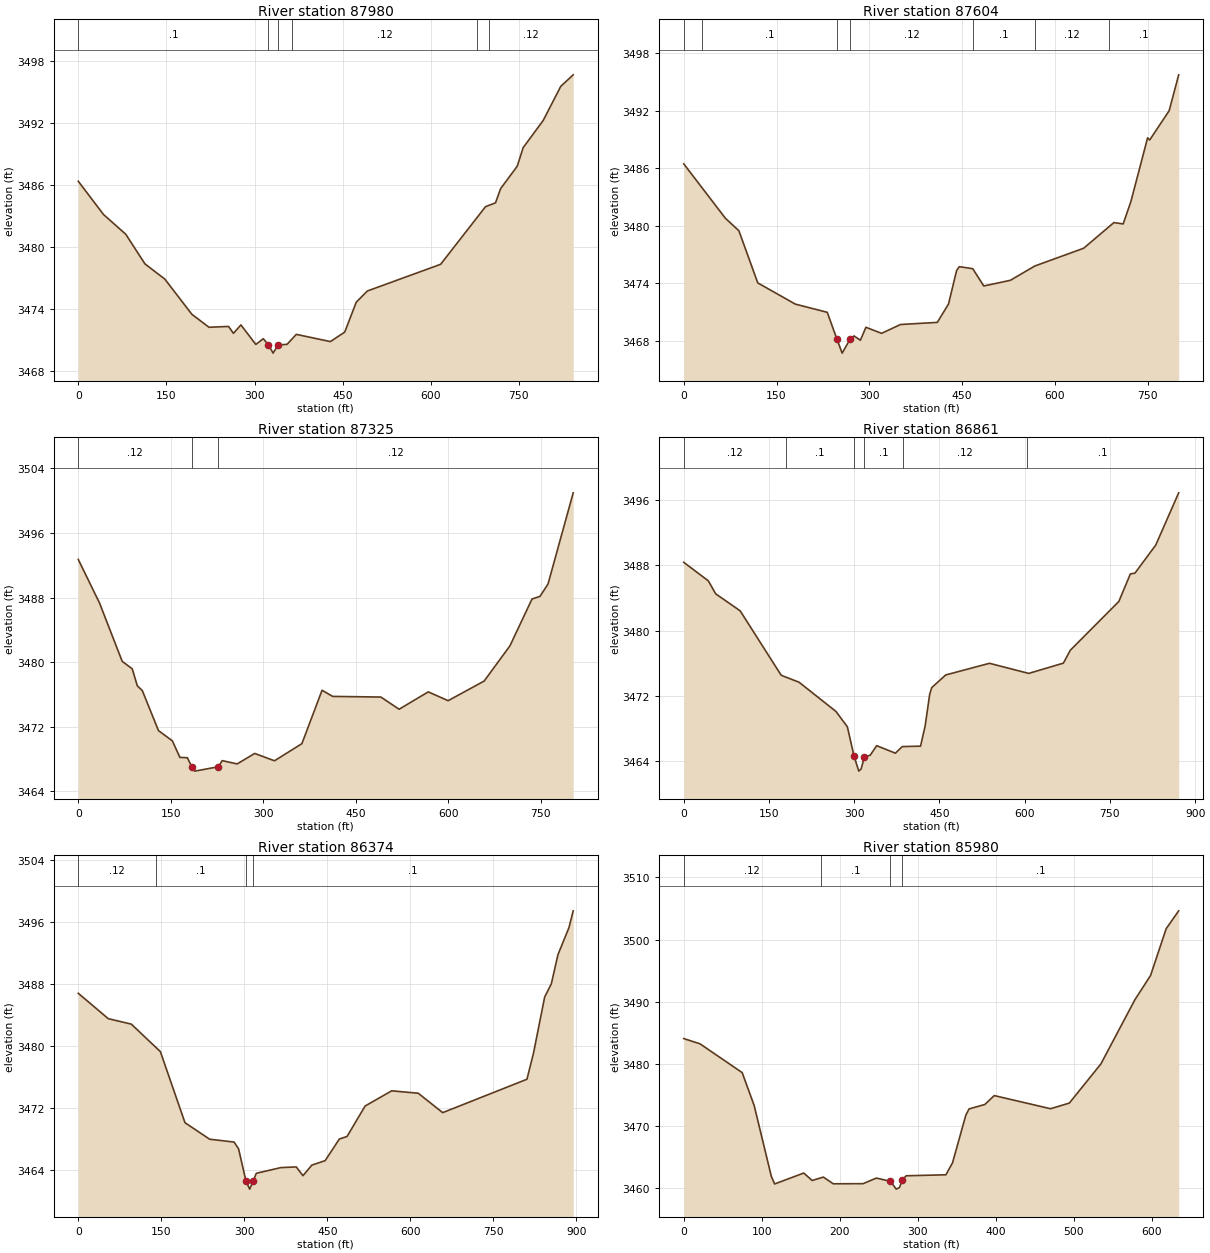
Type RM Length L Ch R = 1 ,87980   ,351.6,375.9,359.7
XS GIS Cut Line= 4
2204129.68369501 451217.054249162203876.02572586451142.854979274
2203625.81888555451056.5767584772203332.47293484450946.140635856
#Sta/Elev= 30
       0 3486.37      43 3483.14    80.8 3481.23   113.5 3478.35   147.4 3476.87
   193.3 3473.46   222.5  3472.2   255.8 3472.28   264.1 3471.61   276.8 3472.43
   302.2 3470.53   314.9 3471.09   323.4 3470.51   331.6 3469.69   340.3 3470.49
   355.3 3470.54   371.1 3471.51   429.1 3470.81   453.5 3471.73   473.1 3474.63
     492 3475.72   616.7 3478.31   693.1  3483.9   710.2 3484.28   718.8 3485.65
   747.1 3487.83   757.2 3489.63   791.4 3492.28   821.3 3495.59842.3976  3496.7
#Mann= 6 ,-1,0
       0      .1       0   323.4    .045       0   340.3      .1       0
  364.29     .12       0  678.95      .1       0  698.95     .12       0
Bank Sta=323.4,340.3
XS Rating Curve= 0 ,0
Exp/Cntr(USF)=0,0
Exp/Cntr=0.3,0.1

Type RM Length L Ch R = 1 ,87604   ,287.3,278.9,229.2
XS GIS Cut Line= 4
2204190.07844957 451008.260954832204012.34531472450932.336120529
 2203825.9843578 450808.095482582203473.96921695450657.971378392
#Sta/Elev= 30
       0 3486.45    67.3 3480.79    89.1 3479.49   119.6 3474.06   180.4 3471.85
   231.9    3471   247.6  3468.2     256 3466.75     269 3468.22   275.2 3468.54
   285.5 3468.09   294.4 3469.44   319.7 3468.81   350.4 3469.73   409.8 3469.95
   427.9 3471.86     441 3475.35   445.3 3475.75   467.1 3475.54   484.9 3473.74
   527.9 3474.33   567.4 3475.82   646.4 3477.67   695.2 3480.34   710.2  3480.2
   722.7 3482.53   749.7 3489.16   753.1 3488.94   784.5 3491.98799.9393 3495.72
#Mann= 7 ,-1,0
       0     .12       0      30      .1       0   247.6    .045       0
     269     .12       0  467.25      .1       0  567.25     .12       0
  687.25      .1       0
Bank Sta=247.6,269
XS Rating Curve= 0 ,0
Exp/Cntr(USF)=0,0
Exp/Cntr=0.3,0.1

Type RM Length L Ch R = 1 ,87325   ,460.2,463.7,450.6
XS GIS Cut Line= 4
2204278.08223478450747.7007280222204145.21377475450721.817261783
2203893.28137002450687.3059734642203510.20606968450533.730740444
#Sta/Elev= 30
       0 3492.72    34.5 3487.32    71.2 3480.11    87.5 3479.18    95.7 3477.08
   103.8 3476.49     130 3471.54   152.6 3470.26   164.7 3468.22   176.8 3468.18
  184.043467.065   188.9 3466.52  227.173467.064   233.3 3467.82   257.6 3467.41
     286 3468.71   318.1  3467.8   362.5 3469.92   395.2 3476.53   412.4 3475.77
   490.6 3475.69   520.1 3474.18   567.4 3476.33   599.6 3475.24     658 3477.67
   699.8 3482.03   735.6 3487.83   748.5 3488.15   761.5 3489.68802.3643 3500.97
#Mann= 3 ,-1,0
       0     .12       0  184.04    .045       0  227.17     .12       0
Bank Sta=184.04,227.17
XS Rating Curve= 0 ,0
Exp/Cntr(USF)=0,0
Exp/Cntr=0.3,0.1

Type RM Length L Ch R = 1 ,86861   ,486,487.2,481.7
XS GIS Cut Line= 4
2204459.26649846450340.4675258582204224.58973789450355.997605601
2203977.83402641450328.3885749462203596.48429048450259.365998308
#Sta/Elev= 30
       0 3488.36    43.2 3486.09    56.2  3484.5    99.3 3482.41   171.5 3474.51
   202.9 3473.66   267.8 3470.08   287.9  3468.2   299.7 3464.59   308.1 3462.76
   312.1 3463.02   317.8 3464.46   328.2 3464.72   339.5 3465.88   372.5 3464.96
   384.5 3465.77   416.7 3465.82   424.8 3468.29   432.8 3472.18   436.4    3473
     461 3474.55     538 3475.98   607.1 3474.74   668.1    3476   680.3 3477.58
   765.7 3483.56     786 3486.94     794 3487.03   830.7 3490.48871.0313 3496.88
#Mann= 6 ,-1,0
       0     .12       0     180      .1       0   299.7    .045       0
   317.8      .1       0  385.19     .12       0  603.49      .1       0
Bank Sta=299.7,317.8
XS Rating Curve= 0 ,0
Exp/Cntr(USF)=0,0
Exp/Cntr=0.3,0.1

Type RM Length L Ch R = 1 ,86374   ,396.1,393.9,388
XS GIS Cut Line= 4
2204511.03343093450107.5163297042204241.84538205450069.553912553
2203972.65733316450088.535121129 2203620.6421923450073.005041385
#Sta/Elev= 30
       0  3486.8    54.2 3483.53    95.8 3482.83   148.3 3479.29   192.7 3470.14
   237.2 3468.01   281.5 3467.64   289.6 3466.76  302.883462.631   309.6 3461.58
  315.953462.633   321.6 3463.62   365.8 3464.35   393.8 3464.44   405.9 3463.31
   421.9 3464.67     446 3465.25   471.6 3468.03   485.5 3468.36   518.1 3472.28
   566.2 3474.24   614.1 3473.93   658.3 3471.43   810.5 3475.73   822.5 3479.15
   842.5 3486.32   854.5 3488.01   866.5 3491.77   886.4 3495.26894.0657 3497.42
#Mann= 4 ,-1,0
       0     .12       0     140      .1       0  302.88    .045       0
  315.95      .1       0
Bank Sta=302.88,315.95
XS Rating Curve= 0 ,0
Exp/Cntr(USF)=0,0
Exp/Cntr=0.3,0.1

Type RM Length L Ch R = 1 ,85980   ,251.6,258.9,253.3
XS GIS Cut Line= 4
2204252.19876854449729.6177226112204083.09345578449777.933526258
2203900.18362769449843.5049740642203636.17227205449826.249329904
#Sta/Elev= 30
       0 3484.04    20.8  3483.2    74.9 3478.56    90.3 3473.26   112.3 3461.85
   116.5 3460.62   153.9 3462.38   164.7 3461.18     179 3461.73   191.7 3460.65
     230 3460.67     247 3461.57   265.1 3461.05   272.5 3459.79   276.7 3460.05
   280.3 3461.28   285.2 3461.94   336.2  3462.1   344.7 3464.03   361.7 3471.68
   365.9 3472.71   386.2 3473.43   398.2 3474.86   470.4 3472.74   494.5 3473.65
     535 3479.96   578.6  3490.3   598.7 3494.21   618.7 3501.74634.7549 3504.62
#Mann= 4 ,-1,0
       0     .12       0  175.87      .1       0   265.1    .045       0
   280.3      .1       0
Bank Sta=265.1,280.3
XS Rating Curve= 0 ,0
Exp/Cntr(USF)=0,0
Exp/Cntr=0.3,0.1

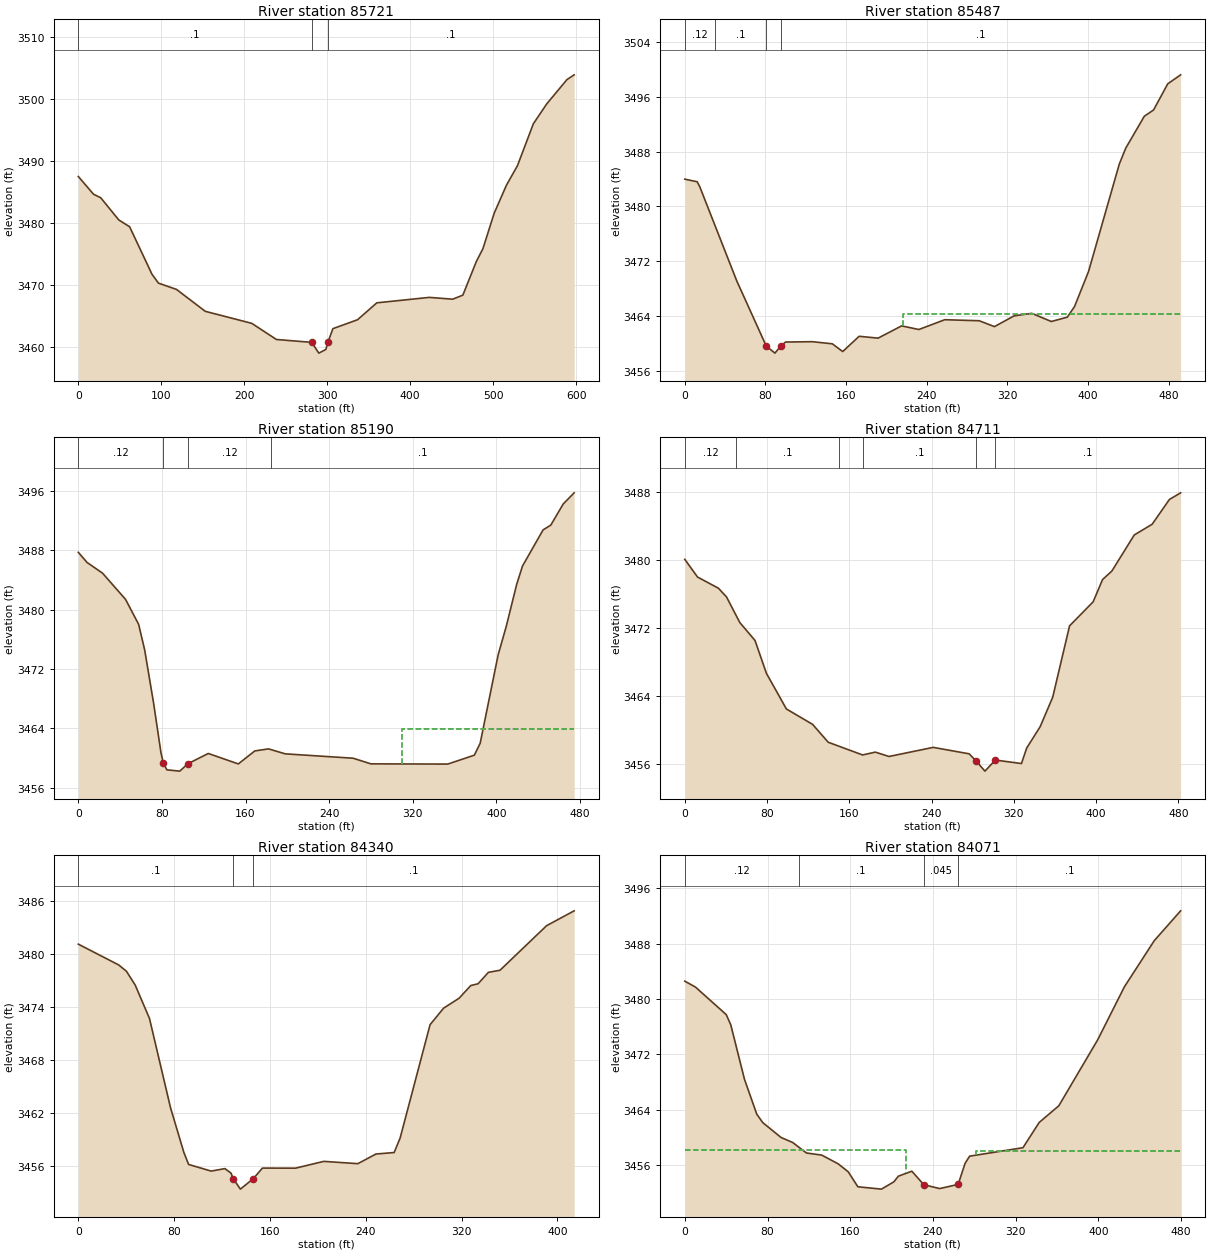
Type RM Length L Ch R = 1 ,85721   ,236.6,234.3,230.3
XS GIS Cut Line= 4
2204209.05965814449553.6101521842204038.22878096449626.083857654
2203870.84903262449686.4786122122203639.62340088449722.715464947
#Sta/Elev= 30
       0 3487.45    18.3 3484.59      27 3484.02    48.8 3480.43    61.8 3479.34
    88.8 3471.66    96.6 3470.23   118.3 3469.22     153 3465.68     209 3463.74
   238.8 3461.13   281.3 3460.67   289.8 3458.93   298.3 3459.52   300.8  3460.7
   306.8 3462.88   336.5 3464.32   359.7 3467.05   422.9 3467.93   451.2 3467.64
   463.4 3468.29   479.6  3473.7   487.7 3475.83   501.2 3481.53     516 3486.06
   529.2 3489.19   548.4 3495.97   564.6 3499.19   588.9  3503.1597.5587 3503.87
#Mann= 3 ,-1,0
       0      .1       0   281.3    .045       0   300.8      .1       0
Bank Sta=281.3,300.8
XS Rating Curve= 0 ,0
Exp/Cntr(USF)=0,0
Exp/Cntr=0.3,0.1

Type RM Length L Ch R = 1 ,85487   ,294.5,297.1,286.6
XS GIS Cut Line= 4
2204062.27285655 449410.547166082204013.41458927449444.928909722
2203805.31456196449602.3611042922203656.93019466449687.410680669
#Sta/Elev= 30
       0 3483.96    12.3 3483.58    14.9 3482.84    51.5 3469.11    80.8 3459.58
    89.4 3458.55    95.1 3459.58    99.9 3460.17   126.5 3460.22   146.3 3459.91
   156.6 3458.78   172.9 3461.01   191.7 3460.74     215 3462.53   232.1    3462
   257.8 3463.43     292 3463.28   307.1 3462.42   326.5 3463.99   344.1 3464.36
   363.5 3463.17   379.3  3463.8   386.5 3465.35   400.4 3470.48   430.9 3486.17
   437.3  3488.5   455.7 3493.15   464.9 3494.07   478.9 3497.88   491.7  3499.2
#Mann= 4 ,-1,0
       0     .12       0      30      .1       0    80.8    .045       0
    95.1      .1       0
#XS Ineff= 2 , 0
                          216.45         3464.32
Permanent Ineff=
       F       F
Bank Sta=80.8,95.1
XS Rating Curve= 0 ,0
Exp/Cntr(USF)=0,0
Exp/Cntr=0.3,0.1

Type RM Length L Ch R = 1 ,85190   ,469.7,479,468.5
XS GIS Cut Line= 4
2203951.95056017449293.0499253762203898.45806327449344.816857854
2203682.76251128449570.865796344 2203630.9955788449641.613937398
#Sta/Elev= 30
       0 3487.72     8.4 3486.35    23.2 3484.91    45.2 3481.38    57.7 3478.02
    63.5 3474.57    72.1 3467.34    79.1 3460.71   81.36  3459.3    84.8  3458.4
    97.1 3458.23  104.78 3459.22   124.4 3460.61   153.1  3459.2   168.9 3460.95
     182 3461.23     198 3460.56     263 3459.97     280 3459.21   353.6 3459.18
     379 3460.38   384.6 3461.98   401.8  3473.9   409.6 3477.76   419.5 3483.38
   425.1 3485.87   444.8 3490.74   452.2 3491.39   464.1 3494.24474.5508 3495.74
#Mann= 4 ,-1,0
       0     .12       0   81.36    .045       0  104.78     .12       0
  184.44      .1       0
#XS Ineff= 2 , 0
                          309.58         3463.94
Permanent Ineff=
       F       F
Bank Sta=81.36,104.78
XS Rating Curve= 0 ,0
Exp/Cntr(USF)=0,0
Exp/Cntr=0.3,0.1

Type RM Length L Ch R = 1 ,84711   ,362.9,370.7,361.1
XS GIS Cut Line= 4
2203725.90162168449236.1062996492203605.11211256449331.012342527
2203439.45792863449460.4296737232203356.63083666449544.982330104
#Sta/Elev= 30
       0 3480.04    12.4 3477.96    32.7 3476.65    40.6 3475.62    53.5 3472.62
    68.3 3470.51    79.4 3466.65    98.8 3462.47   124.3 3460.66   139.5 3458.56
   172.9 3457.07   185.3  3457.4   198.6 3456.89   241.6 3457.96   276.6  3457.2
  282.95  3456.4   291.9 3455.17     302 3456.47   327.4 3456.06   332.5 3457.88
   345.6 3460.39   357.8 3463.85   374.2 3472.23   397.1 3475.05   406.3 3477.67
   415.3 3478.66   437.1  3482.9   454.5 3484.16   471.3 3487.07482.1902 3487.85
#Mann= 6 ,-1,0
       0     .12       0      50      .1       0     150     .12       0
  173.61      .1       0  282.95    .045       0     302      .1       0
Bank Sta=282.95,302
XS Rating Curve= 0 ,0
Exp/Cntr(USF)=0,0
Exp/Cntr=0.3,0.1

Type RM Length L Ch R = 1 ,84340   ,184.8,269.1,275.7
BEGIN DESCRIPTION:
structure xs 4
END DESCRIPTION:
XS GIS Cut Line= 4
2203572.32638866449079.079937798 2203511.9316341449118.767919365
2203348.00301458449244.7341217292203237.56689196449322.384520447
#Sta/Elev= 30
       0 3481.07    33.7 3478.72    40.2    3478    47.5 3476.44    59.4 3472.67
      77 3462.56    88.1 3457.52    92.1 3456.15   110.9  3455.4   122.4 3455.68
   127.5 3455.17  129.32 3454.54   135.3 3453.36  146.07 3454.54   153.7 3455.74
   181.3 3455.73     205  3456.5   233.4 3456.24   248.5 3457.33   263.7  3457.5
   268.7 3459.14   293.7 3471.96     305 3473.83   317.9 3474.95   327.7 3476.39
   333.8 3476.59   342.4 3477.88   352.1 3478.12     391 3483.16414.0074 3484.84
#Mann= 3 ,-1,0
       0      .1       0  129.32    .045       0  146.07      .1       0
Bank Sta=129.32,146.07
XS Rating Curve= 0 ,0
Exp/Cntr(USF)=0,0
Exp/Cntr=0.5,0.3

Type RM Length L Ch R = 1 ,84071   ,125.5,48.3,48.5
BEGIN DESCRIPTION:
structure xs 3
END DESCRIPTION:
XS GIS Cut Line= 5
2203488.42856772448956.8147519992203356.58694276 449018.77626935
2203295.79298181449022.0485026132203203.31443831  449068.8818521
2203062.14601344449162.528232953
#Sta/Elev= 30
       0 3482.57    10.3 3481.72    40.1 3477.74    44.5 3476.26    57.7 3468.42
    69.6 3463.37    75.4 3462.15    93.1    3460   104.3 3459.28   117.7 3457.76
   132.5 3457.45   148.4 3456.19   158.1 3455.04   167.4 3452.88   190.2 3452.54
   202.2 3453.59   206.6 3454.41   219.6 3455.13   231.2 3453.18   246.5 3452.62
   264.4 3453.22   271.1 3456.26   275.5  3457.3   327.1 3458.52   342.8 3462.17
   361.8 3464.58   399.3 3474.08   425.2 3481.75   454.1 3488.42   479.6 3492.73
#Mann= 4 ,-1,0
       0     .12       0     110      .1       0   231.2    .045       0
   264.4      .1       0
#XS Ineff= 2 , 0
           214.4 3458.18   281.2         3458.11
Permanent Ineff=
       F       F
Bank Sta=231.2,264.4
XS Rating Curve= 0 ,0
Exp/Cntr(USF)=0,0
Exp/Cntr=0.5,0.3

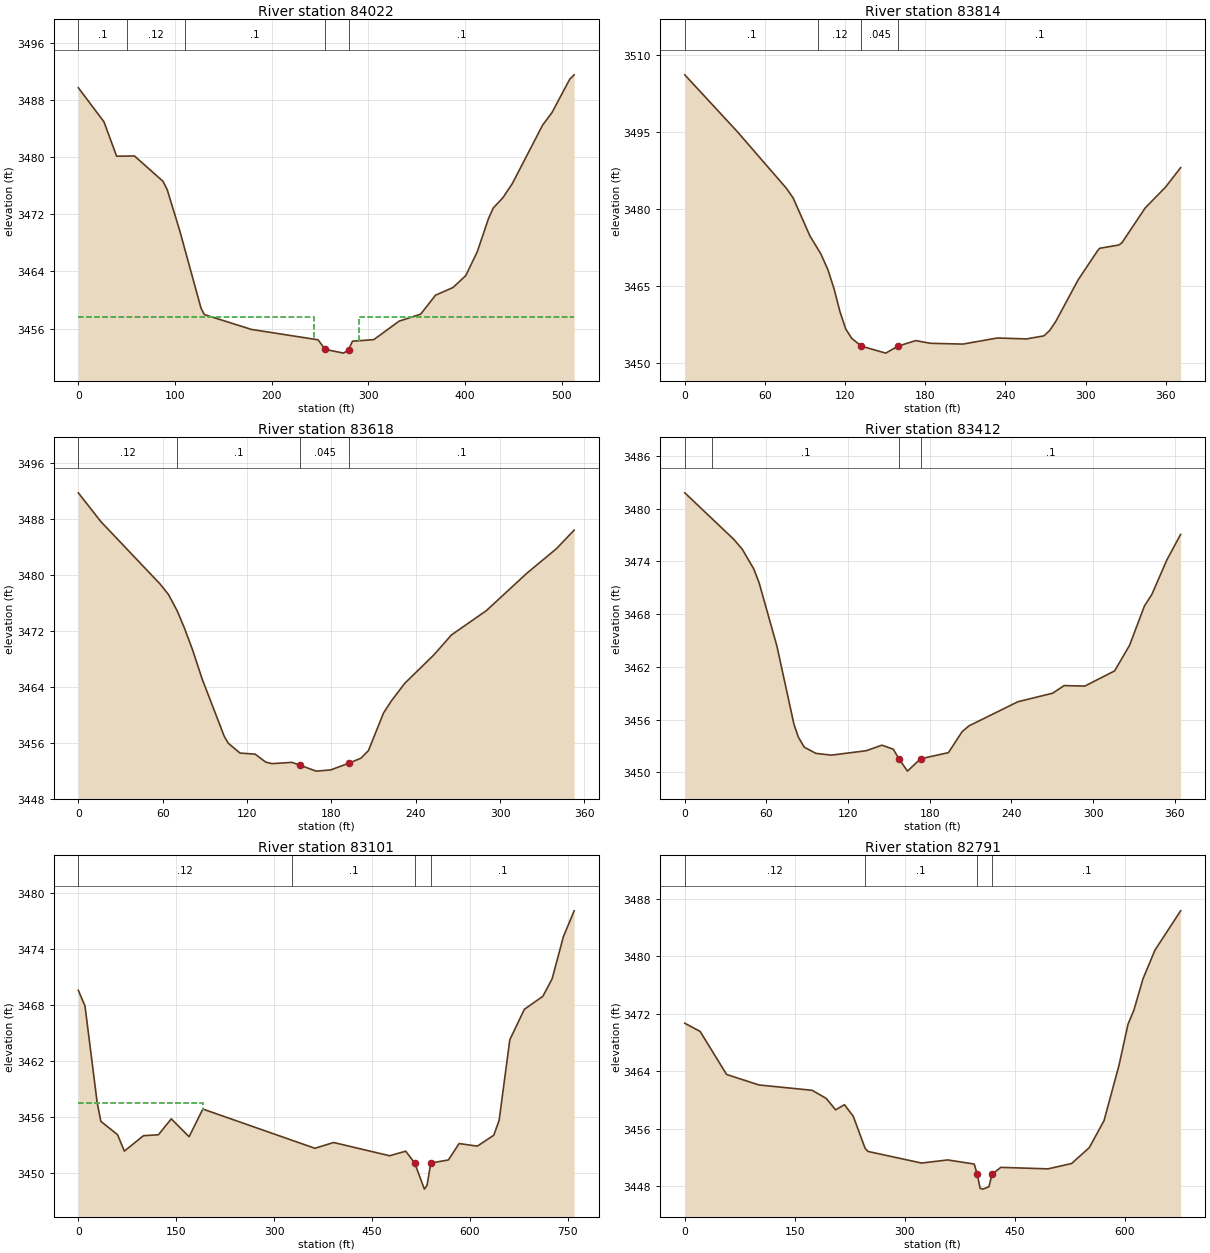
Type RM Length L Ch R = 1 ,84022   ,222.3,208.3,187.8
BEGIN DESCRIPTION:
structure xs 2
END DESCRIPTION:
XS GIS Cut Line= 5
2203488.47008832448914.0412854492203313.51379746448990.010892692
  2203256.440054448989.9709059952203134.82678664449046.518537269
2203020.21479813 449109.41536023
#Sta/Elev= 30
       0 3489.74    26.5 3484.97    39.6 3480.15    58.1 3480.18    87.5 3476.64
    91.9 3475.47     105 3469.65   126.8 3458.89   130.3 3457.96     179 3455.88
   247.8 3454.43   255.4 3453.08   274.4 3452.56  279.39 3453.05   283.5 3454.23
   305.5 3454.45   331.7 3457.04     354 3458.02   369.3 3460.67   387.5 3461.76
   400.6 3463.42   412.4 3466.72   424.1  3471.4     429 3472.89   438.9 3474.31
   448.8 3476.32   480.1 3484.51   489.9 3486.29   508.1 3490.93   512.7 3491.55
#Mann= 5 ,-1,0
       0      .1       0      50     .12       0     110      .1       0
   255.4    .045       0  279.39      .1       0
#XS Ineff= 2 , 0
           244.2 3457.57   290.6         3457.57
Permanent Ineff=
       F       F
Bank Sta=255.4,279.39
XS Rating Curve= 0 ,0
Exp/Cntr(USF)=0,0
Exp/Cntr=0.5,0.3

Type RM Length L Ch R = 1 ,83814   ,186.7,196.2,203.9
XS GIS Cut Line= 4
2203181.88292826448758.9014604182203111.99756942448842.763891034
2203042.11221057449002.7237123922202993.96896336449075.715087187
#Sta/Elev= 30
       0 3506.14    39.4 3495.04    75.9 3484.07    81.1 3482.14    93.7 3474.72
   101.9 3471.21   107.1 3468.17   111.8 3464.38   116.2 3459.92   120.5 3456.59
   124.9 3454.79   132.1 3453.26   150.4 3451.89   159.8 3453.27   172.9 3454.33
   183.8 3453.81   208.1 3453.65     234 3454.84   255.8 3454.66   268.9 3455.26
   273.3 3456.35   277.7 3458.07   294.5  3466.2     309 3471.85   310.6 3472.33
     325 3472.97   327.3 3473.43   344.6 3480.18   359.9 3484.26371.1628 3488.05
#Mann= 4 ,-1,0
       0      .1       0     100     .12       0   132.1    .045       0
   159.8      .1       0
Bank Sta=132.1,159.8
XS Rating Curve= 0 ,0
Exp/Cntr(USF)=0,0
Exp/Cntr=0.3,0.1

Type RM Length L Ch R = 1 ,83618   ,200.9,205.8,210.3
XS GIS Cut Line= 4
2203048.32424247448710.7582132132202984.65091552 448766.66650029
2202888.36442111448873.8240505212202855.75125365448993.405664546
#Sta/Elev= 30
       0 3491.68      16 3487.58    58.2 3478.66    64.2 3477.15    70.4 3474.81
    75.5 3472.37    81.2 3469.31    88.1 3465.11   103.8 3456.93   106.7 3455.94
     115 3454.54   125.8 3454.38   133.3 3453.25   137.8 3453.03     152 3453.21
     158 3452.78   169.2 3451.96   179.5 3452.13  192.223453.075     201  3453.8
   206.4 3454.89   217.1 3460.25   222.8 3462.01   232.3 3464.51     253 3468.56
   265.4 3471.39   290.3 3474.87   319.3 3480.24   340.1  3483.7352.7461 3486.36
#Mann= 4 ,-1,0
       0     .12       0      70      .1       0     158    .045       0
  192.22      .1       0
Bank Sta=158,192.22
XS Rating Curve= 0 ,0
Exp/Cntr(USF)=0,0
Exp/Cntr=0.3,0.1

Type RM Length L Ch R = 1 ,83412   ,325.3,311.2,293.8
XS GIS Cut Line= 4
2202916.31856465448581.8585513422202865.06930149448625.342774624
 2202731.5106157448726.2882929572202636.77712926448814.809747495
#Sta/Elev= 30
       0 3481.79      36  3476.5    42.2 3475.38    50.7 3473.13    54.6 3471.56
    67.7 3464.35    80.2 3455.47    83.4 3454.02    87.7 3452.87    96.3 3452.16
   107.7 3451.96   133.3 3452.46   144.8 3453.09   153.2 3452.63  157.323451.543
   163.6 3450.14  173.223451.544   193.7 3452.24   203.7 3454.62   208.7 3455.28
   244.7 3458.03   270.2    3459   278.7 3459.87   293.9 3459.81   315.8 3461.54
   326.8 3464.46   337.7 3468.92   343.2 3470.25   354.2 3474.17 364.282 3477.06
#Mann= 4 ,-1,0
       0     .12       0      20      .1       0  157.32    .045       0
  173.22      .1       0
Bank Sta=157.32,173.22
XS Rating Curve= 0 ,0
Exp/Cntr(USF)=0,0
Exp/Cntr=0.3,0.1

Type RM Length L Ch R = 1 ,83101   ,308.9,310.1,300.8
XS GIS Cut Line= 4
 2202850.7279439448075.1178011912202691.59255888448264.929886946
2202603.39704428448677.148052978 2202555.4646994448753.839804798
#Sta/Elev= 30
       0 3469.54    10.2 3467.87    28.8 3457.54    34.5 3455.49    60.1 3454.06
    70.5  3452.3    99.8 3453.95   122.7 3454.05   142.4 3455.76   169.7 3453.84
   190.8 3456.81   362.5  3452.6   391.1 3453.22     477  3451.8   501.6 3452.29
  515.423451.014   530.2 3448.22   534.3 3448.62  539.963451.015     567 3451.35
   583.4 3453.11   611.3 3452.83   636.5    3454   644.7 3455.59   661.1 3464.24
   683.4 3467.51   711.7  3468.9   725.9 3470.77   743.2  3475.3759.6808 3478.07
#Mann= 4 ,-1,0
       0     .12       0  327.69      .1       0  515.42    .045       0
  539.96      .1       0
#XS Ineff= 2 , 0
          190.31 3457.46
Permanent Ineff=
       F       F
Bank Sta=515.42,539.96
XS Rating Curve= 0 ,0
Exp/Cntr(USF)=0,0
Exp/Cntr=0.3,0.1

Type RM Length L Ch R = 1 ,82791   ,626.4,653.8,649.4
XS GIS Cut Line= 4
2202417.41954612448000.3433431672202398.24660816 448224.66671724
2202363.73531984448571.6968942262202342.64508809448671.396171592
#Sta/Elev= 30
       0 3470.71    20.9 3469.57      57 3463.58   101.2 3462.12   173.5 3461.38
   192.7 3460.26   205.6 3458.66   217.6 3459.38   229.7 3457.75   245.7 3453.32
   249.8 3452.87   322.6 3451.26   358.3 3451.69   394.5 3451.12   398.5 3449.73
   402.5 3447.75   406.5 3447.63   414.6 3447.97   418.6 3449.67   430.7 3450.66
     495 3450.45   527.1 3451.19   551.3  3453.4   571.4 3457.16   591.8 3464.86
     604 3470.54   612.2 3472.57   624.5 3476.89   640.8 3480.88675.7888 3486.35
#Mann= 4 ,-1,0
       0     .12       0  245.14      .1       0   398.5    .045       0
   418.6      .1       0
Bank Sta=398.5,418.6
XS Rating Curve= 0 ,0
Exp/Cntr(USF)=0,0
Exp/Cntr=0.3,0.1

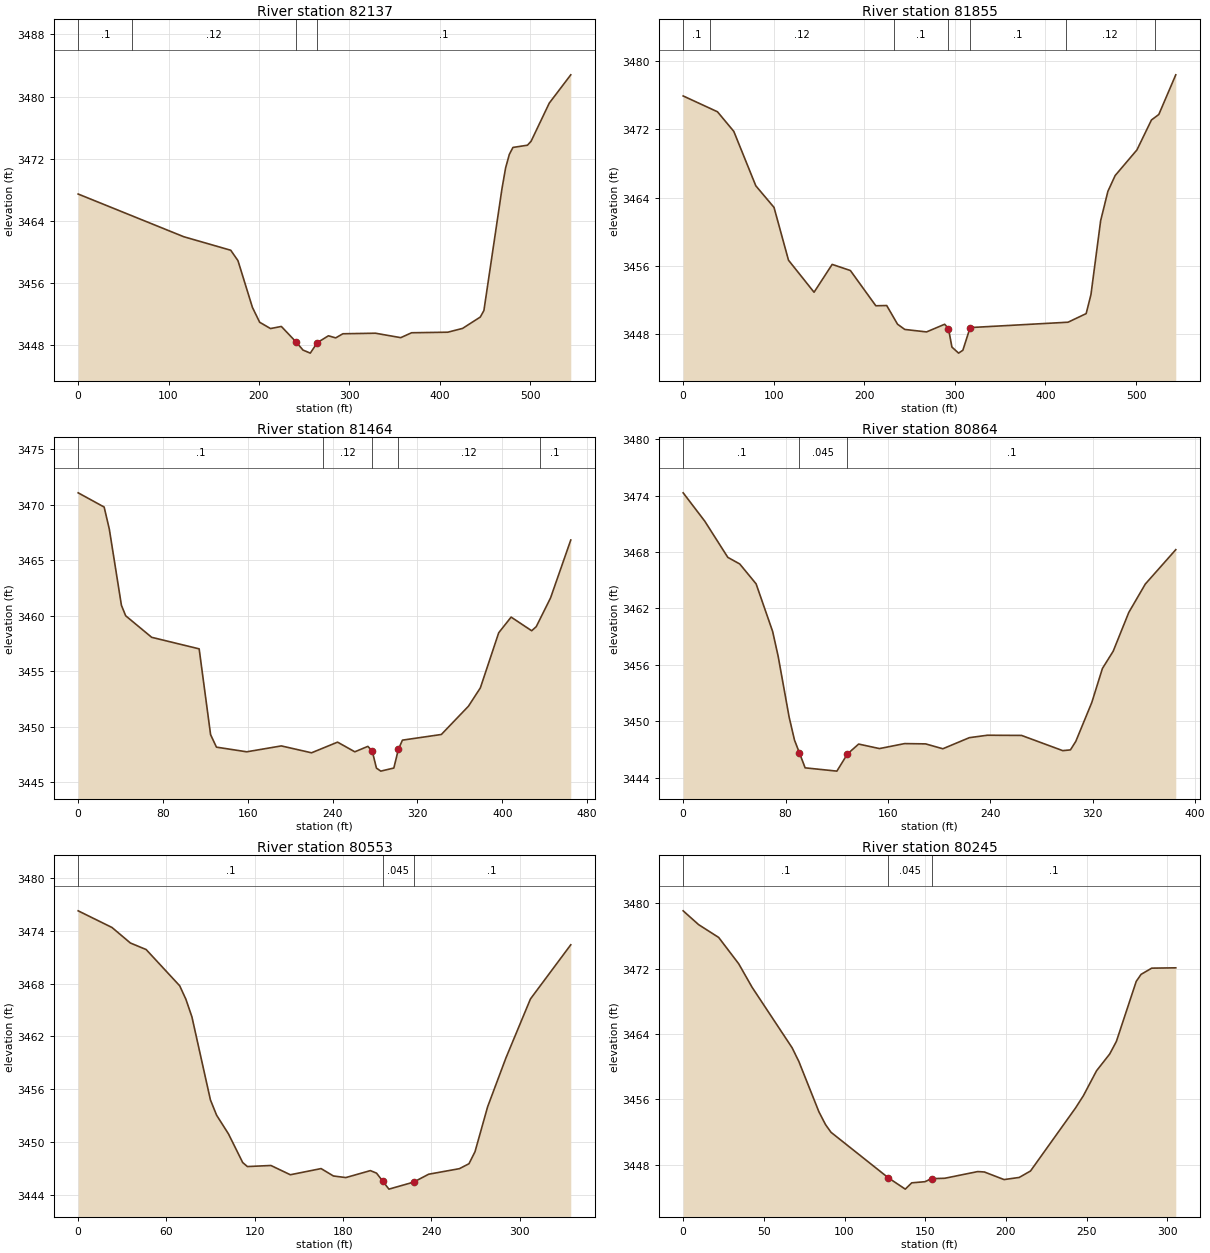
Type RM Length L Ch R = 1 ,82137   ,280.7,281.8,281.1
XS GIS Cut Line= 4
2202032.04349322448092.3734453512202033.96078702448261.095299355
 2202041.6299622448558.2758376572202049.29913738448636.884883273
#Sta/Elev= 30
       0 3467.46   116.8 3461.97   168.8 3460.23   176.8 3458.89   192.8 3452.88
   200.8 3450.97   212.8 3450.16   224.8 3450.43   240.8 3448.47   248.8 3447.39
   256.8    3447   264.6 3448.35   276.9 3449.23   284.9 3448.96   292.9 3449.49
   328.9 3449.56   356.9 3448.99   368.9 3449.62   408.9 3449.69   425.3 3450.18
   444.9 3451.64   448.9 3452.48   468.9 3468.16   472.9 3470.82     477 3472.55
     481 3473.45   497.1 3473.74   501.1 3474.25   521.2 3479.15544.9945 3482.79
#Mann= 4 ,-1,0
       0      .1       0      60     .12       0   240.8    .045       0
   264.6      .1       0
Bank Sta=240.8,264.6
XS Rating Curve= 0 ,0
Exp/Cntr(USF)=0,0
Exp/Cntr=0.3,0.1

Type RM Length L Ch R = 1 ,81855   ,388.8,391,379.6
XS GIS Cut Line= 4
2201778.96071222448117.2982646922201796.21635638448309.027644242
2201807.72011915 448587.035244592201813.47200054448659.892408819
#Sta/Elev= 30
       0 3475.93    37.9 3474.07    55.9 3471.77    80.2 3465.38   100.3 3462.84
   116.3 3456.64   144.5 3452.88   164.5 3456.15   184.6 3455.43   212.7 3451.29
   224.7 3451.32   236.7 3449.12   244.7 3448.51   268.7 3448.22   288.7 3449.12
   292.9 3448.62   296.7 3446.44   304.1 3445.73   308.8 3446.07   316.8 3448.73
   424.9 3449.36   444.9 3450.37   450.2  3452.6   460.9 3461.28   468.9 3464.73
   476.9 3466.58     501  3469.6     517 3473.11   525.1 3473.75543.8337 3478.41
#Mann= 7 ,-1,0
       0      .1       0      30     .12       0   232.5      .1       0
   292.9    .045       0   316.8      .1       0   422.5     .12       0
  520.75      .1       0
Bank Sta=292.9,316.8
XS Rating Curve= 0 ,0
Exp/Cntr(USF)=0,0
Exp/Cntr=0.3,0.1

Type RM Length L Ch R = 1 ,81464   ,600.2,600.2,600.2
XS GIS Cut Line= 4
 2201573.8102761448213.1629544672201594.90050785448322.448700811
2201646.66744033448581.2833632032201669.67496587448667.561584001
#Sta/Elev= 30
       0 3471.07    24.5 3469.79    29.4 3467.79    40.8 3460.94    44.8    3460
    69.3 3458.06   114.1 3457.02   124.9 3449.29   130.4 3448.17     159 3447.75
   191.6 3448.28   220.1 3447.66   244.6 3448.62   260.9 3447.75   273.2 3448.24
   277.3 3447.82   281.3 3446.28   285.4 3446.01   297.7 3446.29  301.98 3447.97
   305.8  3448.8   342.5 3449.31   368.1 3451.86   379.3 3453.51   396.6 3458.47
   408.3 3459.88   427.7 3458.65     432 3459.02   445.5 3461.61 464.556 3466.82
#Mann= 5 ,-1,0
       0      .1       0   231.3     .12       0   277.3    .045       0
  301.98     .12       0  435.26      .1       0
Bank Sta=277.3,301.98
XS Rating Curve= 0 ,0
Exp/Cntr(USF)=0,0
Exp/Cntr=0.3,0.1

Type RM Length L Ch R = 1 ,80864   ,304.3,310.5,304.3
XS GIS Cut Line= 4
2201303.47185093448332.0351697882201334.14855166448410.644215404
2201378.24630896448575.5314818172201414.67489107448700.155578524
#Sta/Elev= 30
       0 3474.31    16.9 3471.29    34.9 3467.44    44.2 3466.74      57 3464.62
    69.9 3459.56    74.2 3456.93    82.8 3450.44      87 3447.99    90.8 3446.65
    95.3 3445.04   120.1 3444.69   128.4 3446.52   137.1 3447.57   153.4 3447.09
     173 3447.62   189.4 3447.59   202.9 3447.07   223.6 3448.25   237.7 3448.51
   264.4 3448.49   296.6 3446.87   302.6 3446.95   306.8 3447.86   319.3    3452
   327.6 3455.62     336 3457.45   348.2 3461.58   361.1  3464.6384.9041 3468.26
#Mann= 3 ,-1,0
       0      .1       0    90.8    .045       0   128.4      .1       0
Bank Sta=90.8,128.4
XS Rating Curve= 0 ,0
Exp/Cntr(USF)=0,0
Exp/Cntr=0.3,0.1

Type RM Length L Ch R = 1 ,80553   ,305.6,308.2,307.8
XS GIS Cut Line= 4
2201134.74999693448491.1705548152201180.76504802448642.636764659
2201217.19363014 448761.50897998 2201232.5319805448811.358618663
#Sta/Elev= 30
       0 3476.25      23 3474.36    35.5  3472.6    46.2 3471.86      69 3467.75
    73.2 3466.23    77.3 3464.23    89.9  3454.8    94.1 3453.07   102.2 3450.94
   111.8 3447.71     115 3447.25     131 3447.37   144.2 3446.32   165.1 3447.02
   173.5 3446.18   181.9    3446   198.6 3446.79   202.8  3446.5     207 3445.59
   211.2 3444.69   227.9 3445.48   238.2 3446.38   259.1 3447.01   265.6 3447.57
   269.7 3448.93   278.3 3454.04   290.7 3459.56   307.4 3466.26334.7864  3472.4
#Mann= 3 ,-1,0
       0      .1       0     207    .045       0   227.9      .1       0
Bank Sta=207,227.9
XS Rating Curve= 0 ,0
Exp/Cntr(USF)=0,0
Exp/Cntr=0.3,0.1

Type RM Length L Ch R = 1 ,80245   ,308.1,306.6,300.3
XS GIS Cut Line= 4
2200879.74992213448611.9600639312200908.50932906448719.328516479
2200931.51685461448830.5315566182200948.77249877448909.140602234
#Sta/Elev= 30
       0 3479.07     9.5 3477.39      22 3475.81    34.4 3472.59    42.7 3469.71
    67.5  3462.3    71.7 3460.61    84.1 3454.46    88.2 3452.89    91.6 3451.95
  127.173446.367   137.6 3444.99   141.6 3445.76   149.8  3445.9   153.9 3446.27
   162.1 3446.32   182.5 3447.14   186.6 3447.09   198.8 3446.16   208.2 3446.42
   215.2 3447.21   243.1 3454.93   247.9 3456.41   256.1 3459.48   264.3 3461.55
   268.4 3463.08   280.7 3470.43   283.7 3471.29   290.3 3472.05305.1923 3472.09
#Mann= 3 ,-1,0
       0      .1       0  127.17    .045       0   153.9      .1       0
Bank Sta=127.17,153.9
XS Rating Curve= 0 ,0
Exp/Cntr(USF)=0,0
Exp/Cntr=0.3,0.1