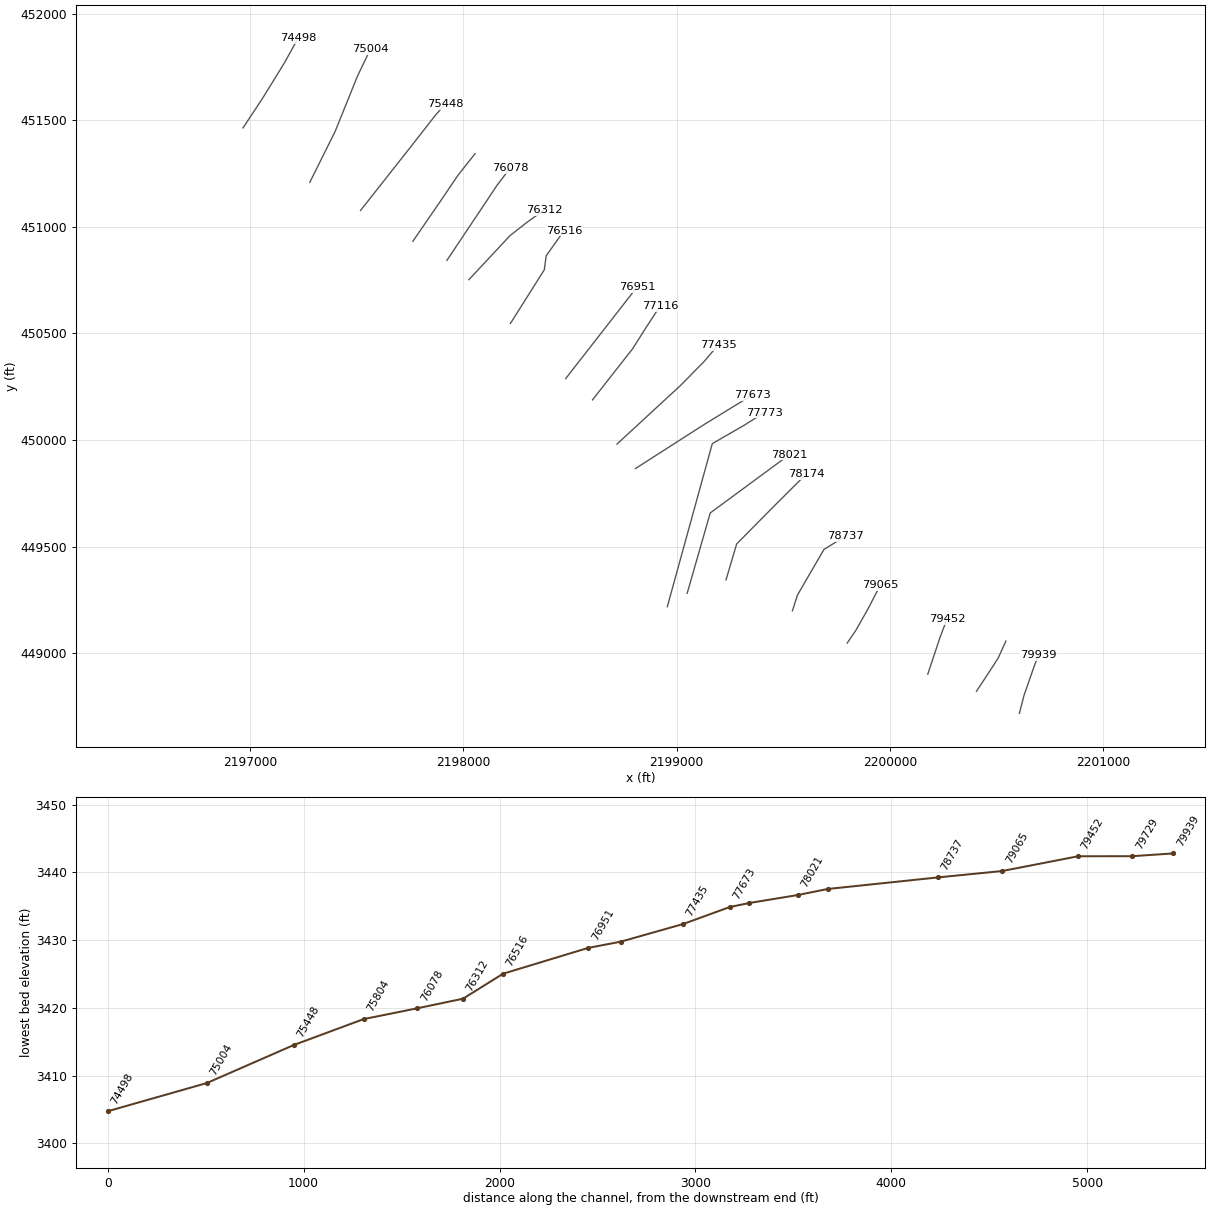
HEC-RAS study WILLIAMSRV.prj: WILLIAMSRV

--- WILLIAMSRV.g01 (geometry) --- (continued)

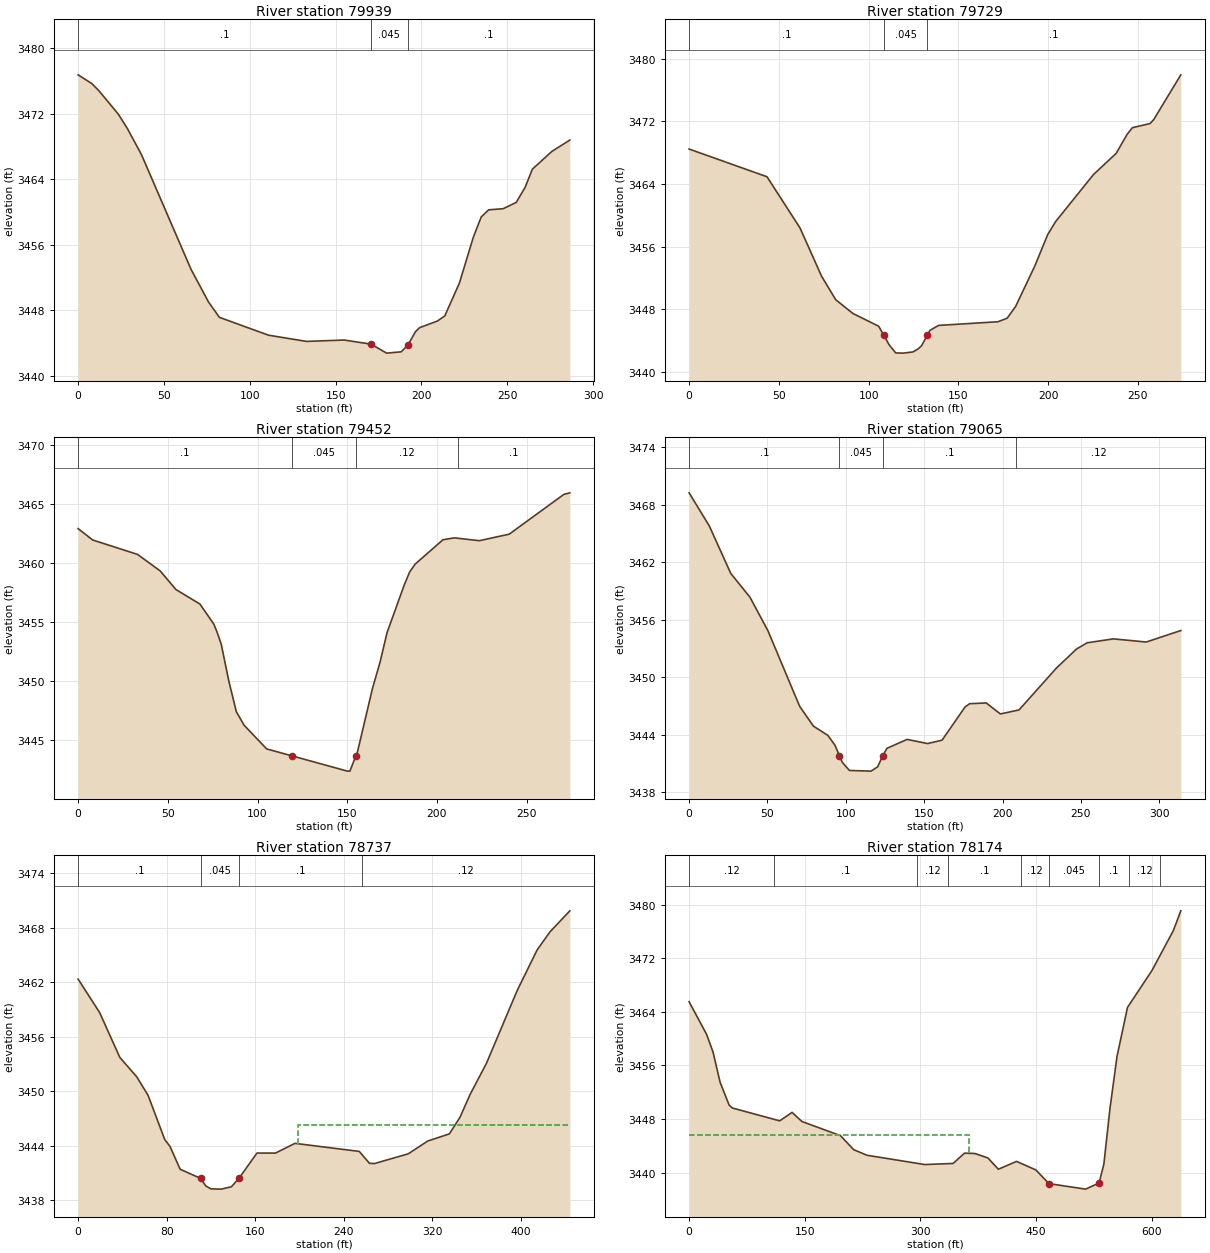
Type RM Length L Ch R = 1 ,79939   ,214.1,209.3,203.2
XS GIS Cut Line= 4
2200607.49420317448717.4112226842200628.58443492 448799.85485589
2200672.68219221448926.3962463932200695.68971776448989.666941645
#Sta/Elev= 30
       0 3476.78       8 3475.71    12.1 3474.84    23.4 3471.98    28.7 3470.22
    36.9 3467.03    65.8 3453.01      76 3449.02    82.3 3447.16   110.9 3444.98
   133.1 3444.22   154.9 3444.39   170.6 3443.89   179.7 3442.79   188.2 3442.95
   191.9 3443.73   196.6 3445.43   198.9  3445.9   209.3 3446.71   213.6 3447.34
   222.1 3451.35   230.2 3456.94   234.8 3459.42   239.1 3460.29   247.6 3460.43
   255.2  3461.2   260.4 3463.05   264.6 3465.26   276.1 3467.45286.4275 3468.81
#Mann= 3 ,-1,0
       0      .1       0   170.6    .045       0   191.9      .1       0
Bank Sta=170.6,191.9
XS Rating Curve= 0 ,0
Exp/Cntr(USF)=0,0
Exp/Cntr=0.3,0.1

Type RM Length L Ch R = 1 ,79729   ,269.9,277.3,281.9
XS GIS Cut Line= 4
2200406.17835464448820.9450876412200457.94528712448899.554133256
 2200507.7949258448976.2458850762200544.22350791449056.772224487
#Sta/Elev= 30
       0 3468.45    43.4 3464.91    61.8 3458.37    73.8 3452.21    81.7  3449.2
    91.3 3447.44   105.6 3445.82  108.523444.662   111.4 3443.46   115.1 3442.41
   119.3 3442.38   124.7 3442.53   127.6 3442.92   129.5 3443.32  132.723444.662
   134.2 3445.29     139 3445.92   172.1 3446.39   177.2 3446.84   181.9 3448.33
   192.6  3453.5   199.8 3457.52   204.2 3459.18   225.3 3465.19     238 3467.91
     244 3470.31     247 3471.18   256.9 3471.71   258.9 3472.22273.9754 3477.93
#Mann= 3 ,-1,0
       0      .1       0  108.52    .045       0  132.72      .1       0
Bank Sta=108.52,132.72
XS Rating Curve= 0 ,0
Exp/Cntr(USF)=0,0
Exp/Cntr=0.3,0.1

Type RM Length L Ch R = 1 ,79452   ,389.9,387.4,382.1
XS GIS Cut Line= 4
2200178.02039297448901.4714270522200206.77979991448987.749647849
2200235.53920684449074.0278686472200268.13320136449160.306089444
#Sta/Elev= 30
       0 3462.89     8.1 3461.93    33.1 3460.71    45.7 3459.32    54.5 3457.74
    67.9 3456.51    75.6 3454.82    77.4 3454.16    79.8  3453.1      84    3450
    88.2  3447.4    92.5 3446.26   105.1 3444.25  119.133443.665   150.1 3442.37
   151.5 3442.37  154.853443.663   155.7 3443.98   164.1 3449.37   168.3 3451.58
   172.2 3454.08   181.7 3458.08   184.8 3459.22   187.9 3459.89   203.4 3461.95
   209.7 3462.11   223.7 3461.87   240.3 3462.42   270.8 3465.79274.1201 3465.92
#Mann= 4 ,-1,0
       0      .1       0  119.13    .045       0  154.85     .12       0
  211.89      .1       0
Bank Sta=119.13,154.85
XS Rating Curve= 0 ,0
Exp/Cntr(USF)=0,0
Exp/Cntr=0.3,0.1

Type RM Length L Ch R = 1 ,79065   ,326.3,327.7,326.9
XS GIS Cut Line= 4
2199800.31351526 449047.185755512199840.57668497 449106.62186317
2199898.09549883449208.238434332 2199955.6143127449319.441474471
#Sta/Elev= 30
       0 3469.25    12.9 3465.79    26.6 3460.83    38.8 3458.36    50.3 3454.85
    70.5 3446.97    79.3 3444.89    88.5 3443.93    93.1 3442.89   95.933441.795
    97.7 3441.12   102.3 3440.26   116.1 3440.19   120.3 3440.64  123.573441.797
   126.2 3442.57   139.1  3443.5   152.2 3443.07   161.4 3443.42   176.1 3446.89
     179 3447.23   189.6 3447.31   198.6 3446.16   210.5 3446.58   234.6 3450.99
   247.2 3452.94     254 3453.59   270.7    3454   291.7 3453.67313.7539 3454.87
#Mann= 4 ,-1,0
       0      .1       0   95.93    .045       0  123.57      .1       0
  208.56     .12       0
Bank Sta=95.93,123.57
XS Rating Curve= 0 ,0
Exp/Cntr(USF)=0,0
Exp/Cntr=0.3,0.1

Type RM Length L Ch R = 1 ,78737   ,541.9,563.5,557.3
XS GIS Cut Line= 4
2199543.39614666449198.6519653542199566.40367221449271.509129583
2199691.02776892449486.2460346792199792.64434008449549.516729931
#Sta/Elev= 30
       0 3462.37    19.4  3458.7    37.7 3453.75      53 3451.61    63.2 3449.58
    78.3  3444.7      83 3443.96    92.2 3441.44  110.783440.428   115.3 3439.61
     120 3439.28   129.2 3439.25   138.5 3439.51   145.33440.427   161.6 3443.22
   178.4 3443.22     196 3444.29   254.1  3443.4   263.3 3442.09     268 3442.07
   298.4 3443.14     316 3444.55   335.5 3445.33   345.1 3447.16   354.3 3449.69
   369.1 3453.12   396.7 3461.09   414.8 3465.58   426.4 3467.57444.3882 3469.89
#Mann= 4 ,-1,0
       0      .1       0  110.78    .045       0   145.3      .1       0
   256.4     .12       0
#XS Ineff= 2 , 0
                          198.79         3446.35
Permanent Ineff=
       F       F
Bank Sta=110.78,145.3
XS Rating Curve= 0 ,0
Exp/Cntr(USF)=0,0
Exp/Cntr=0.3,0.1

Type RM Length L Ch R = 1 ,78174   ,152,152.9,153.7
XS GIS Cut Line= 4
2199231.88699254449343.4382995062199282.01102776449512.438739624
2199460.95251346449693.4126078042199607.65527402449839.591036505
#Sta/Elev= 30
       0 3465.51    22.7 3460.64      31 3458.02    40.2  3453.5    51.9 3450.09
    56.1 3449.65   117.5 3447.73   133.6 3448.99   146.4 3447.63   196.4 3445.52
   213.5 3443.43   230.6  3442.6   305.6 3441.21   342.4 3441.37   357.3 3442.91
   370.7 3442.86   387.6  3442.2   401.2 3440.51   424.8 3441.68   449.9  3440.4
   466.8 3438.36   514.4 3437.54   531.9 3438.46   538.1  3441.3     546  3449.6
   555.1 3457.33   568.7 3464.66   600.5 3470.18   628.1 3476.11   637.9 3479.08
#Mann= 9 ,-1,0
       0     .12       0     110      .1       0  296.28     .12       0
  336.28      .1       0  430.78     .12       0   466.8    .045       0
   531.9      .1       0  570.78     .12       0  610.78      .1       0
#XS Ineff= 2 , 0
          362.69  3445.6
Permanent Ineff=
       F       F
Bank Sta=466.8,531.9
XS Rating Curve= 0 ,0
Exp/Cntr(USF)=0,0
Exp/Cntr=0.3,0.1

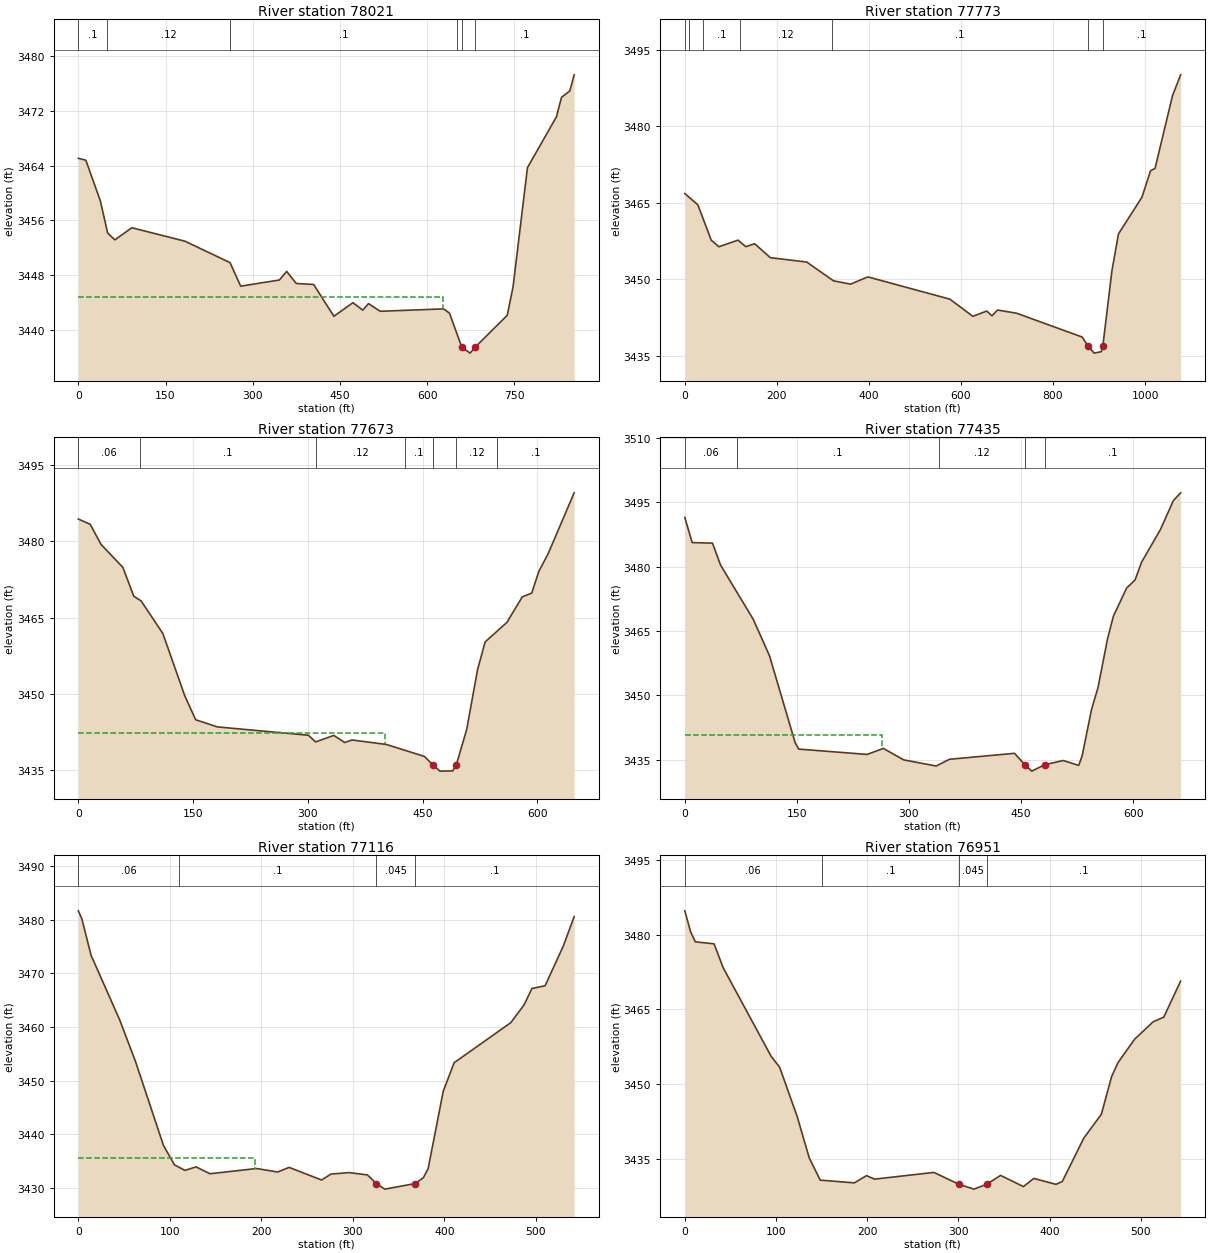
Type RM Length L Ch R = 1 ,78021   ,249.7,247.8,246.6
XS GIS Cut Line= 3
2199049.92799752449280.7686375892199157.89803042449657.565772432
2199528.81063922449930.885418047
#Sta/Elev= 30
       0 3465.05    12.9 3464.78    37.9 3458.84    50.4 3454.17    62.8 3453.16
      92 3454.93   183.3 3452.97   260.9 3449.84   279.2 3446.41   345.8 3447.31
   358.3 3448.56   374.9  3446.8   404.7 3446.66   439.5 3442.02   472.2    3444
   489.2 3442.92   499.1 3443.87     519 3442.75   628.3  3443.1   638.3 3442.48
   659.4 3437.54   673.7 3436.65     683 3437.57   737.6 3442.16   747.6 3446.29
   772.4 3463.69   822.1 3471.08     831 3473.94   845.3 3474.88   852.7 3477.22
#Mann= 6 ,-1,0
       0      .1       0      50     .12       0     260      .1       0
  651.96     .12       0   659.4    .045       0     683      .1       0
#XS Ineff= 2 , 0
          627.63 3444.77
Permanent Ineff=
       F       F
Bank Sta=659.4,683
XS Rating Curve= 0 ,0
Exp/Cntr(USF)=0,0
Exp/Cntr=0.3,0.1

Type RM Length L Ch R = 1 ,77773   ,99.3,100.1,100.4
XS GIS Cut Line= 4
2198956.70424524449217.8249033092199167.60656275449982.825127714
2199317.15547879450069.1033485112199411.10287477450128.539456172
#Sta/Elev= 30
       0 3466.83    28.4 3464.61    57.4 3457.67      74 3456.37   115.5 3457.67
   132.4 3456.39   151.9 3456.96     186 3454.22   264.9 3453.37     323 3449.68
   360.3 3449.02   397.7 3450.45   576.1 3446.07   625.9  3442.7   656.1 3443.74
   667.4  3442.8   679.8 3443.94   721.3  3443.3   863.5 3438.63  875.573436.941
   889.4 3435.47     905 3435.75  908.453436.941   928.1 3451.65   942.3 3458.88
   993.4 3466.12  1011.9 3471.29  1021.8 3471.77  1059.7 3486.041077.362 3490.15
#Mann= 7 ,-1,0
       0      .1       0      10     .12       0      40      .1       0
     120     .12       0     320      .1       0  875.57    .045       0
  908.45      .1       0
Bank Sta=875.57,908.45
XS Rating Curve= 0 ,0
Exp/Cntr(USF)=0,0
Exp/Cntr=0.3,0.1

Type RM Length L Ch R = 1 ,77673   ,228.4,237.3,242.8
XS GIS Cut Line= 4
2198807.15532919449865.8702061882199133.09527443450074.855229898
2199276.89230909450163.050744491 2199355.5013547450210.983089378
#Sta/Elev= 30
       0 3484.37    15.5 3483.33    29.7 3479.38    58.2 3474.87    72.5  3469.2
      82  3468.3   110.5 3461.88     139  3449.7   153.3 3444.96   181.8 3443.55
   300.6 3441.92     310 3440.61   333.8 3441.88   348.1 3440.49   357.6 3440.99
   402.7  3440.1   452.2 3437.76  463.413436.101   472.6 3434.87   489.3 3434.91
  493.943436.101   507.5 3443.04   521.7 3454.78   531.6 3460.24     560 3464.06
   580.2 3469.09   592.5 3469.82   601.9 3474.13   613.7 3477.47647.9434 3489.51
#Mann= 7 ,-1,0
       0     .06       0      80      .1       0     310     .12       0
  427.18      .1       0  463.41    .045       0  493.94     .12       0
  547.18      .1       0
#XS Ineff= 2 , 0
          400.88 3442.45
Permanent Ineff=
       F       F
Bank Sta=463.41,493.94
XS Rating Curve= 0 ,0
Exp/Cntr(USF)=0,0
Exp/Cntr=0.3,0.1

Type RM Length L Ch R = 1 ,77435   ,307.9,319,315.3
XS GIS Cut Line= 4
2198720.87710839449980.9078339182199019.97494049 450256.99814047
2199129.26068684 450368.201180612199194.44867588 450444.89293243
#Sta/Elev= 30
       0 3491.47     9.9 3485.61    37.1 3485.48    47.8 3480.39    91.6 3467.74
   113.4 3459.23   147.8 3438.94   152.6  3437.5     244 3436.26   265.8 3437.66
     293 3434.99   336.5 3433.56   354.2 3435.13   441.3 3436.52   455.4 3433.81
   464.4 3432.37   481.5 3433.85   506.3 3434.84   527.2 3433.72   531.8 3435.92
   544.3 3446.67   553.1 3451.86   565.7 3463.12   573.6 3468.44   591.3 3475.01
   602.6 3476.89   611.5 3481.08   636.7 3488.68   653.9 3495.39 663.613  3497.2
#Mann= 5 ,-1,0
       0     .06       0      70      .1       0     340     .12       0
   455.4    .045       0   481.5      .1       0
#XS Ineff= 2 , 0
          263.66 3440.82
Permanent Ineff=
       F       F
Bank Sta=455.4,481.5
XS Rating Curve= 0 ,0
Exp/Cntr(USF)=0,0
Exp/Cntr=0.3,0.1

Type RM Length L Ch R = 1 ,77116   ,165.1,165.4,163.6
XS GIS Cut Line= 4
2198605.83948066450187.9755638322198793.73427262 450427.63728827
2198857.00496787450527.3365656362198922.19295692450627.035843002
#Sta/Elev= 30
       0 3481.62     3.8 3480.16    13.9 3473.35    45.3 3461.25    62.5 3453.53
      93  3437.9   105.1 3434.28   116.5 3433.25   128.6 3433.91   143.8 3432.63
   194.7  3433.6   217.7 3432.95   230.3 3433.81   265.8 3431.46   276.1 3432.57
     296 3432.84   315.8 3432.41  325.743430.794   334.8 3429.76  368.093430.794
     377 3431.89   382.2 3433.58   398.7    3448   410.6 3453.31   472.5 3460.78
   486.9 3464.06   495.6 3467.15     510 3467.66     530  3475.1541.7364 3480.54
#Mann= 4 ,-1,0
       0     .06       0     110      .1       0  325.74    .045       0
  368.09      .1       0
#XS Ineff= 2 , 0
          192.98 3435.53
Permanent Ineff=
       F       F
Bank Sta=325.74,368.09
XS Rating Curve= 0 ,0
Exp/Cntr(USF)=0,0
Exp/Cntr=0.3,0.1

Type RM Length L Ch R = 1 ,76951   ,415.5,434.6,444.4
XS GIS Cut Line= 2
2198480.27537116450287.9933855982198814.36963402450716.909261765
#Sta/Elev= 30
       0 3484.82     6.5 3480.54    11.6 3478.58    32.1 3478.18    42.1 3473.37
    94.8 3455.52     104 3453.37   123.2 3443.47   136.5 3435.11   148.5 3430.66
     186 3430.11   199.2 3431.56   208.1 3430.86   273.2 3432.21   300.6 3429.82
   317.1 3428.85   331.1 3429.83   346.3 3431.61   371.3 3429.36   382.7    3431
   407.1 3429.81     414  3430.4   437.5  3439.1   456.8 3443.91     468 3451.47
     475 3454.28   493.3 3459.01   513.6 3462.51   525.2 3463.43   543.7 3470.69
#Mann= 4 ,-1,0
       0     .06       0     150      .1       0   300.6    .045       0
   331.1      .1       0
Bank Sta=300.6,331.1
XS Rating Curve= 0 ,0
Exp/Cntr(USF)=0,0
Exp/Cntr=0.3,0.1

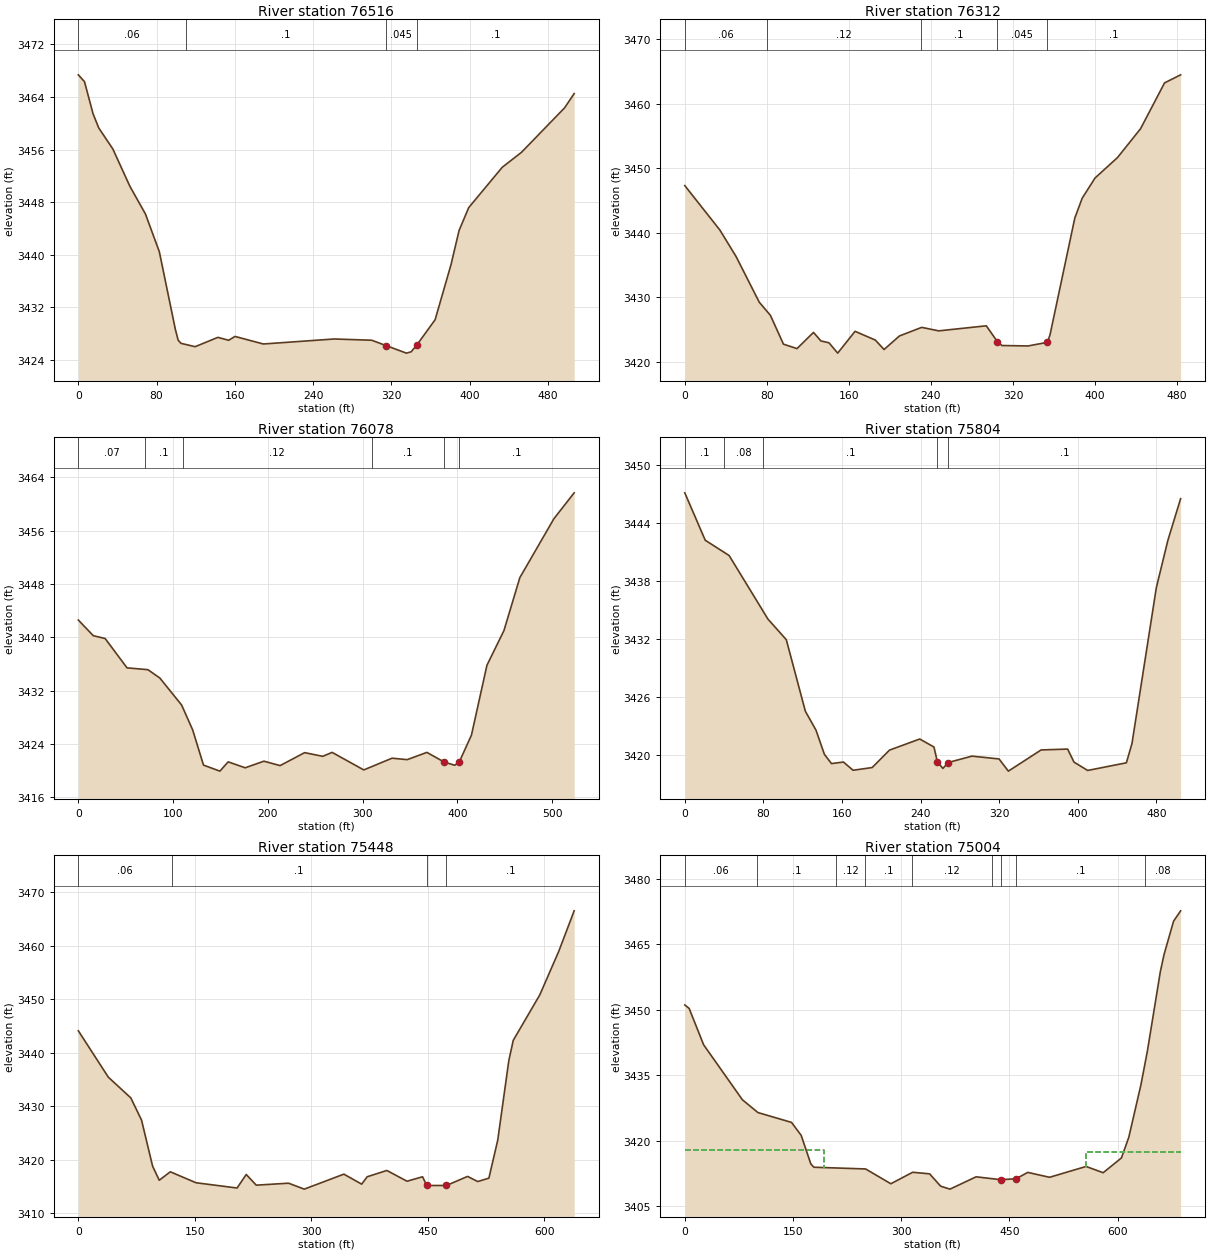
Type RM Length L Ch R = 1 ,76516   ,225.4,204.6,186.4
XS GIS Cut Line= 4
 2198221.5101423450547.1101292332198380.01013616450798.697421079
2198388.81569137450864.1101169592198471.83949768450981.098207667
#Sta/Elev= 30
       0 3467.36     6.3 3466.32      15 3461.46    20.8  3459.3    35.3 3456.08
    52.7 3450.41    68.6  3446.2    82.8 3440.46    99.1 3428.71     102 3427.02
   104.9 3426.53   119.4 3426.02   142.7 3427.44   153.7 3426.99   160.1 3427.58
   189.1 3426.43   261.6 3427.19   299.9    3427  314.46 3426.19   335.3 3425.04
   340.2 3425.24  346.043426.284   364.7 3430.12   380.9 3438.48   389.2 3443.69
     399 3447.16   433.3  3453.3     453 3455.58   497.1 3462.35506.8094 3464.51
#Mann= 4 ,-1,0
       0     .06       0     110      .1       0  314.46    .045       0
  346.04      .1       0
Bank Sta=314.46,346.04
XS Rating Curve= 0 ,0
Exp/Cntr(USF)=0,0
Exp/Cntr=0.3,0.1

Type RM Length L Ch R = 1 ,76312   ,227.3,233.4,233.7
XS GIS Cut Line= 4
2198026.52999112450752.1537720872198220.25220584 450959.71328786
2198300.76013923451022.6101108222198380.01013616451079.217251487
#Sta/Elev= 30
       0  3447.3    34.2 3440.42      50 3436.32    72.6 3429.24    83.5  3427.2
    96.2 3422.74   109.4 3422.05   125.5 3424.56   132.7 3423.24   140.6 3422.95
   149.1 3421.35     166 3424.73   185.8 3423.37   194.3 3421.91   209.3 3424.01
     231 3425.34   247.6  3424.8     294 3425.58   304.9 3423.11   309.2 3422.53
   334.6 3422.46  353.533423.017   356.1 3424.17   380.3 3442.28   387.5 3445.35
   400.1 3448.49   421.9 3451.64   444.4 3456.11   467.8 3463.21483.4726 3464.46
#Mann= 5 ,-1,0
       0     .06       0      80     .12       0     230      .1       0
   304.9    .045       0  353.53      .1       0
Bank Sta=304.9,353.53
XS Rating Curve= 0 ,0
Exp/Cntr(USF)=0,0
Exp/Cntr=0.3,0.1

Type RM Length L Ch R = 1 ,76078   ,270.3,274.2,275.3
XS GIS Cut Line= 4
2197923.37920146450842.7251971522198115.84347972451130.792646315
2198157.35538288451193.6894692772198218.99426938451274.197402667
#Sta/Elev= 30
       0 3442.59    15.8 3440.24    28.3 3439.82    51.4 3435.42    73.4 3435.15
      86  3433.9     109 3429.85   120.6 3426.14   132.1 3420.84   149.4 3419.94
   158.1 3421.33   176.1 3420.44   195.8 3421.43   212.9 3420.77   238.8 3422.71
   257.9 3422.16   267.8 3422.75   301.2 3420.12   331.1 3421.88     347 3421.66
   367.8 3422.75   385.9 3421.31   397.2 3420.82     402 3421.32   414.8 3425.33
   431.2 3435.82   449.1    3441   465.9 3448.95   501.8 3457.77523.2022 3461.66
#Mann= 6 ,-1,0
       0     .07       0      70      .1       0     110     .12       0
     310      .1       0   385.9    .045       0     402      .1       0
Bank Sta=385.9,402
XS Rating Curve= 0 ,0
Exp/Cntr(USF)=0,0
Exp/Cntr=0.3,0.1

Type RM Length L Ch R = 1 ,75804   ,347.8,356.4,357.7
XS GIS Cut Line= 4
2197763.62127114450932.0386857572197890.67285352451116.955345264
2197974.95459629451241.4910547272198055.46252968451343.383907925
#Sta/Elev= 30
       0 3447.11    20.8 3442.21    45.1 3440.63    84.6 3434.06   103.3 3431.93
   122.7 3424.53   133.5 3422.58   142.1 3420.07   149.3 3419.12   161.5 3419.28
   171.2 3418.43   190.7 3418.71   208.3 3420.51   239.1 3421.66   253.6 3420.83
  257.06 3419.29   262.7 3418.62   268.1 3419.23   292.2 3419.89   319.8  3419.6
   329.3 3418.34   362.6 3420.53   389.6 3420.62   396.1 3419.27     410 3418.41
   449.4  3419.2   455.1  3421.2   479.9 3437.32   491.6 3442.19504.5924 3446.51
#Mann= 5 ,-1,0
       0      .1       0      40     .08       0      80      .1       0
  257.06    .045       0   268.1      .1       0
Bank Sta=257.06,268.1
XS Rating Curve= 0 ,0
Exp/Cntr(USF)=0,0
Exp/Cntr=0.3,0.1

Type RM Length L Ch R = 1 ,75448   ,433.7,443.8,444.2
XS GIS Cut Line= 4
2197518.32366159451076.7013785682197757.33158884451379.864065243
2197869.28793371451523.268821595 2197915.8315827451576.102152882
#Sta/Elev= 30
       0 3444.13    38.7 3435.44    67.6 3431.58    81.4 3427.42    95.6 3418.83
   104.2 3416.18   118.4 3417.76   151.6 3415.71   204.4 3414.73   216.2 3417.26
   229.1 3415.26   270.6 3415.63   290.9 3414.52   341.9 3417.32   364.8 3415.45
   371.9 3416.83   397.2 3418.01   423.2    3416   443.2 3416.83   448.6  3415.2
     474  3415.2   501.2  3416.9   514.2 3415.94   528.6 3416.57     540 3423.68
   554.3 3438.58     560 3442.35   594.1 3450.83   618.5 3458.96638.3896 3466.56
#Mann= 4 ,-1,0
       0     .06       0     120      .1       0   448.6    .045       0
     474      .1       0
Bank Sta=448.6,474
XS Rating Curve= 0 ,0
Exp/Cntr(USF)=0,0
Exp/Cntr=0.3,0.1

Type RM Length L Ch R = 1 ,75004   ,508.9,505.8,491.6
XS GIS Cut Line= 4
2197280.57367079451208.7847067882197398.81969796451446.534697582
2197504.48636054451708.1854811012197564.86731058451833.979127024
#Sta/Elev= 30
       0 3451.08       6  3450.3    26.1 3441.96    79.9 3429.36   101.4 3426.44
   147.9 3424.19   161.3 3421.23   174.7 3414.68     179 3413.92   250.6 3413.53
   285.6 3410.14   315.8 3412.77   339.3 3412.41   354.6 3409.59   367.6 3408.91
   403.8 3411.73   437.6 3411.07   459.1 3411.28   475.4 3412.74   505.6 3411.62
   556.2  3414.1   579.9 3412.67   605.2 3416.05   615.4 3420.77   632.2 3432.77
   641.2 3440.53   659.1 3458.67   664.2 3462.58   677.5 3470.27687.2483 3472.63
#Mann= 9 ,-1,0
       0     .06       0     100      .1       0     210     .12       0
     250      .1       0  315.53     .12       0  425.53      .1       0
   437.6    .045       0   459.1      .1       0  637.71     .08       0
#XS Ineff= 2 , 0
          192.73 3417.94  555.84         3417.33
Permanent Ineff=
       F       F
Bank Sta=437.6,459.1
XS Rating Curve= 0 ,0
Exp/Cntr(USF)=0,0
Exp/Cntr=0.3,0.1

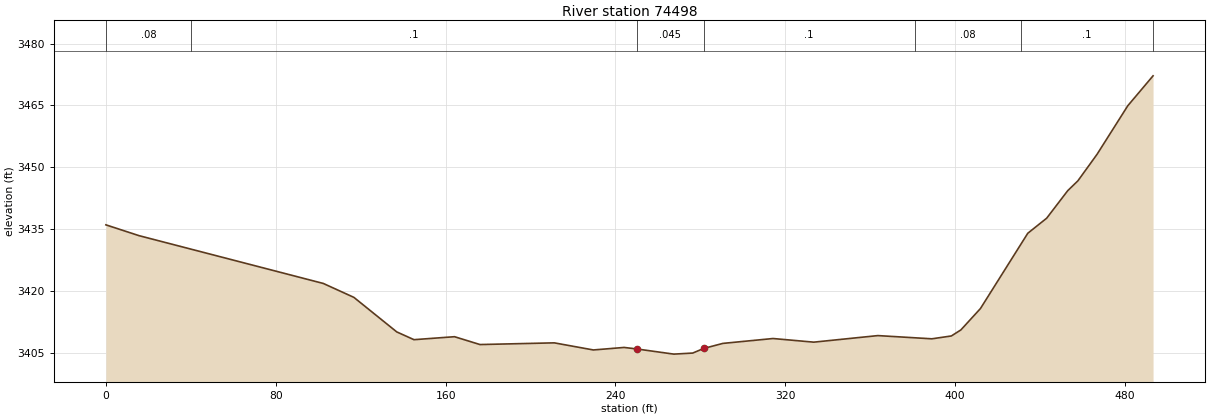
Type RM Length L Ch R = 1 ,74498   ,269.6,267.4,263.3
XS GIS Cut Line= 4
2196967.34749245451464.1458080112197057.91891751451601.260882067
2197161.06970717451768.5664311442197225.22446659451884.296585393
#Sta/Elev= 30
       0 3436.07    15.6 3433.45   102.4 3421.87   116.8  3418.5     137 3410.13
   145.1 3408.25   164.2 3408.97   176.2 3407.07   211.2 3407.48   229.6 3405.76
   244.1 3406.37   250.2 3405.99   267.5 3404.75   276.4 3405.01   281.53406.114
   290.6 3407.35   314.2 3408.53   333.4 3407.65   363.6 3409.24     389 3408.46
   398.2 3409.15   402.7 3410.62   411.9 3415.79   434.2 3434.03   443.1 3437.68
     453 3444.34   457.8 3446.73   466.8 3453.14   481.3 3464.92493.1991 3472.17
#Mann= 7 ,-1,0
       0     .08       0      40      .1       0   250.2    .045       0
   281.5      .1       0  380.88     .08       0  430.88      .1       0
   493.2     .08       0
Bank Sta=250.2,281.5
XS Rating Curve= 0 ,0
Exp/Cntr(USF)=0,0
Exp/Cntr=0.3,0.1