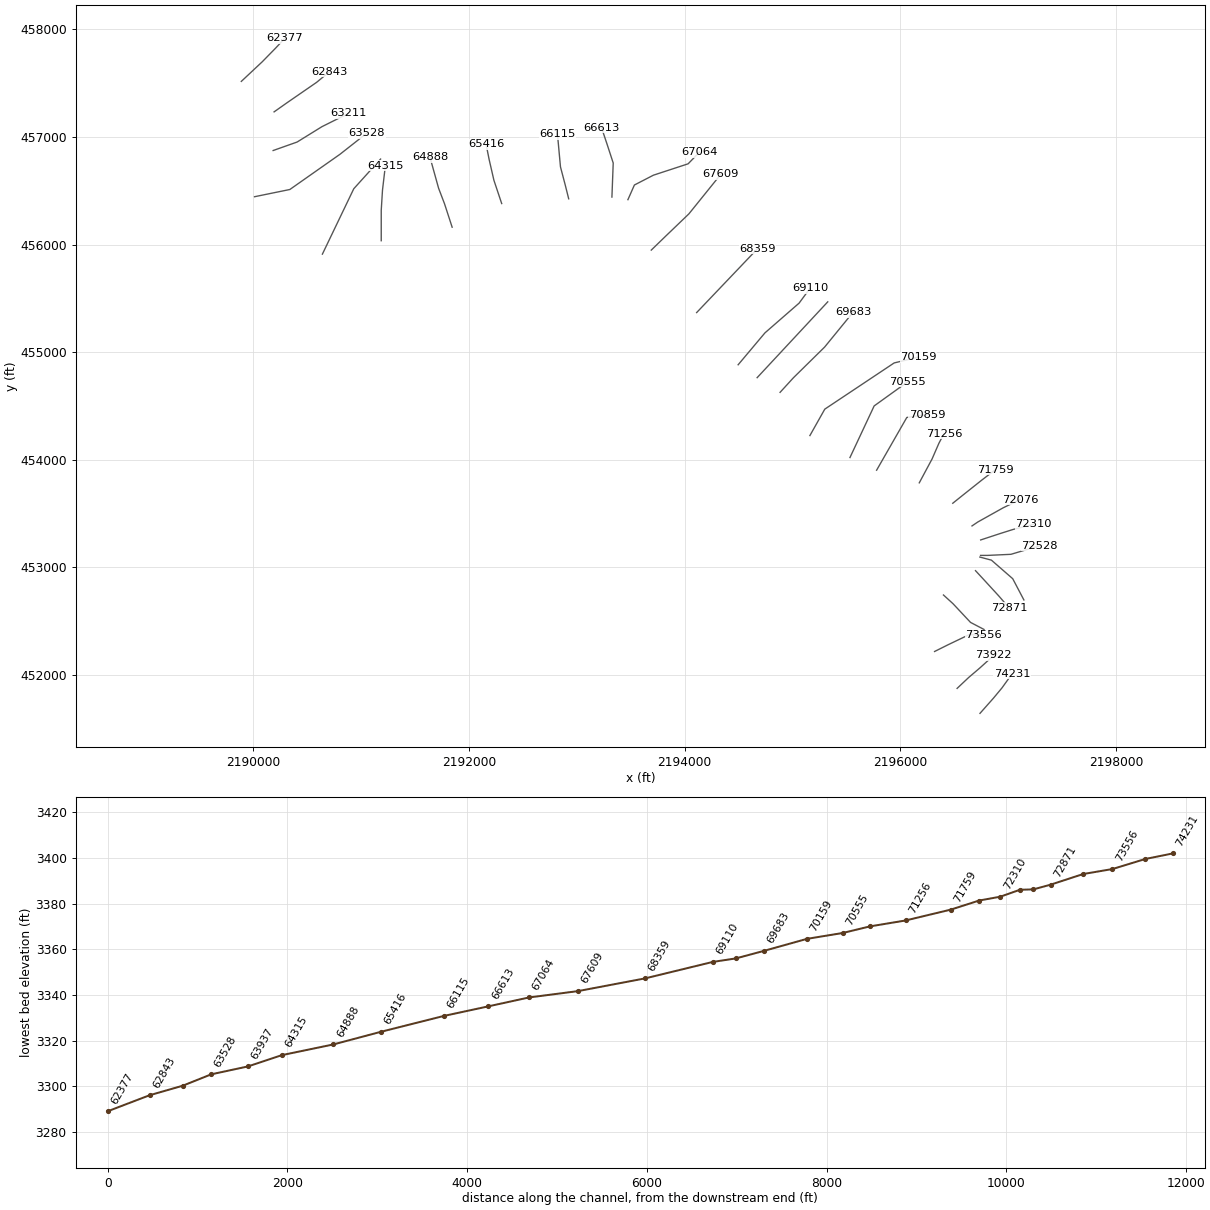
HEC-RAS study WILLIAMSRV.prj: WILLIAMSRV

--- WILLIAMSRV.g01 (geometry) --- (continued)

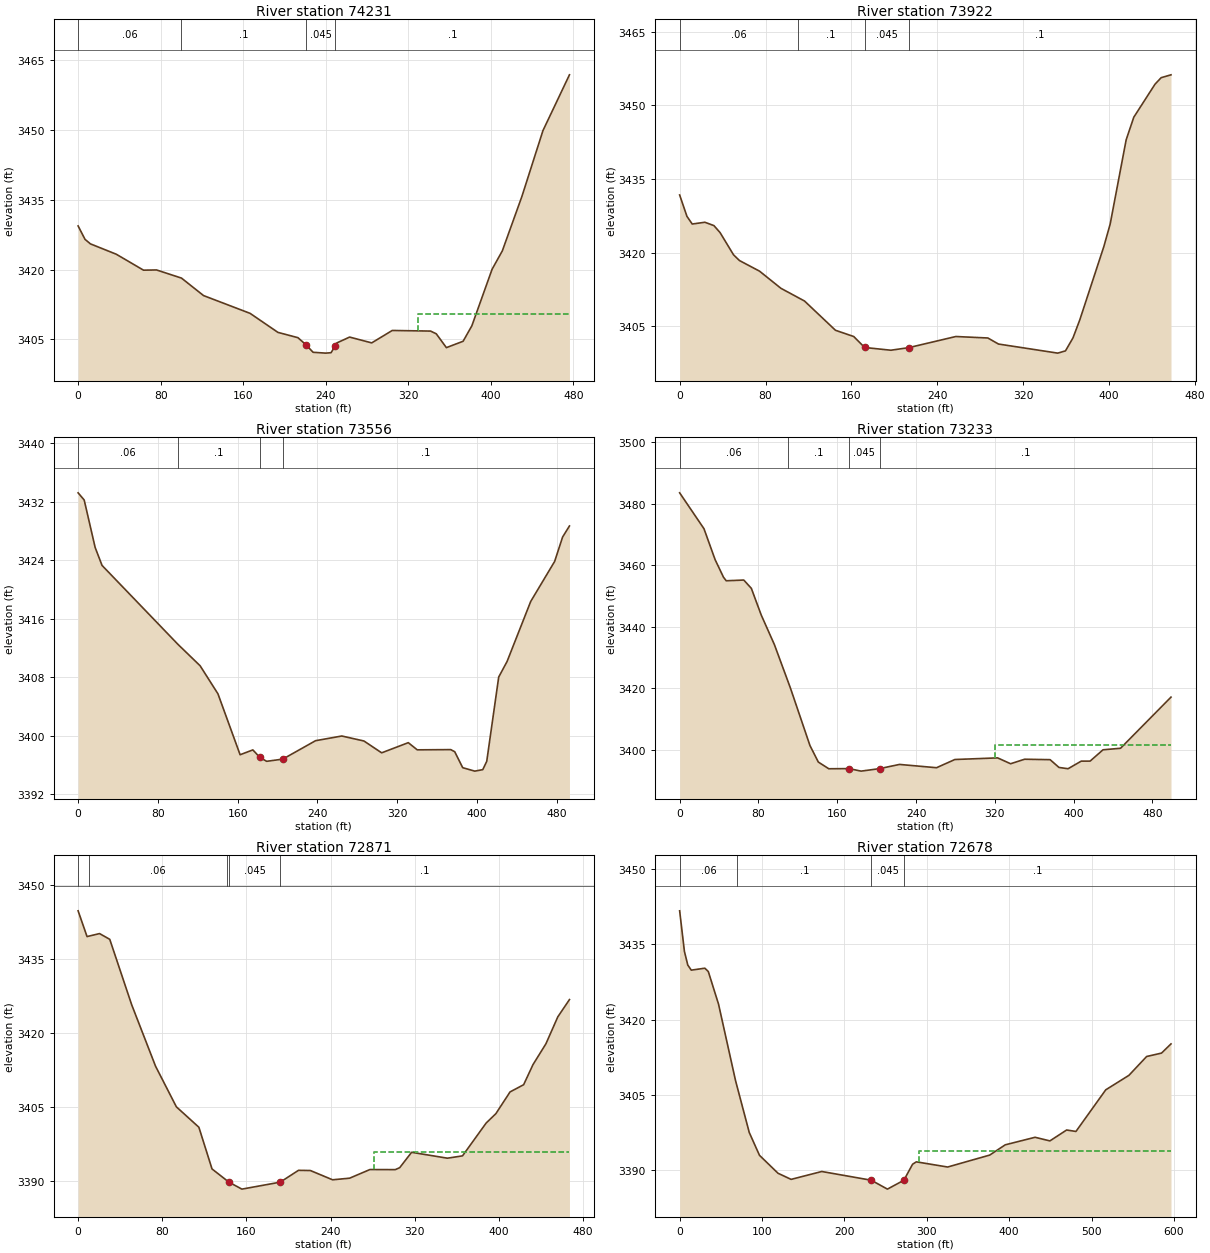
Type RM Length L Ch R = 1 ,74231   ,313.4,308.5,303.1
XS GIS Cut Line= 4
2196739.66099333451640.2569123032196864.19670279451781.145795737
2196943.44669972451876.7489666382197039.04987062452010.090231316
#Sta/Elev= 30
       0 3429.37     6.7 3426.49    11.9 3425.52      37 3423.29    63.4 3419.86
      76 3419.91   100.2 3418.16   121.6  3414.4   166.7 3410.58   193.7 3406.49
   213.1 3405.35  220.723403.859   227.8 3402.21     240 3402.03   245.2 3402.12
   249.2 3403.57   250.7 3404.21   263.2 3405.48   284.6 3404.23   304.5  3406.9
   341.7 3406.77   347.2 3406.18     357 3403.21   373.2 3404.58   381.7 3407.91
   401.3 3420.06   411.2    3424   430.2 3435.71   450.6 3449.86476.2916 3461.85
#Mann= 4 ,-1,0
       0     .06       0     100      .1       0  220.72    .045       0
   249.2      .1       0
#XS Ineff= 2 , 0
                          329.58         3410.38
Permanent Ineff=
       F       F
Bank Sta=220.72,249.2
XS Rating Curve= 0 ,0
Exp/Cntr(USF)=0,0
Exp/Cntr=0.3,0.1

Type RM Length L Ch R = 1 ,73922   ,368.7,365.8,355.8
XS GIS Cut Line= 4
2196527.69227701451872.5073375742196635.06072956451974.123908736
2196740.51188831452064.2367171242196867.05327882452179.274344855
#Sta/Elev= 30
       0 3431.75     6.8  3427.4    11.7 3425.84    23.5  3426.2    31.9 3425.52
    37.6 3424.11    50.2 3419.57    55.7 3418.41    74.4 3416.25    94.3 3412.76
   116.3 3410.17   145.1 3404.22   162.1 3402.95  172.293400.716   196.7 3400.16
   213.2 3400.68   257.2 3402.95     287 3402.65   296.9 3401.42   352.1 3399.57
   359.3 3400.03   366.3 3402.68   372.6 3406.32     395 3421.24   400.9 3425.82
   415.8 3442.97   422.9 3447.57   442.7  3454.3   448.4 3455.62457.5557  3456.2
#Mann= 4 ,-1,0
       0     .06       0     110      .1       0  172.29    .045       0
   213.2      .1       0
Bank Sta=172.29,213.2
XS Rating Curve= 0 ,0
Exp/Cntr(USF)=0,0
Exp/Cntr=0.3,0.1

Type RM Length L Ch R = 1 ,73556   ,352.2,323.4,292.3
XS GIS Cut Line= 4
 2196318.7072533452215.702926969 2196445.2486438452278.973622221
2196640.81261095  452372.92101822196775.02317663452365.251843018
#Sta/Elev= 30
       0 3433.21     6.1 3432.23    17.1 3425.74      24 3423.29     100 3412.52
   122.4 3409.57   140.3 3405.73   162.5 3397.41   175.3 3398.07  182.193397.063
   189.1 3396.51   205.3 3396.81   238.2 3399.33   264.5 3399.97   286.7 3399.29
   304.5 3397.67   331.2 3399.06   340.2 3398.08   373.8 3398.11   377.8 3397.82
   385.8 3395.64   397.9 3395.17   405.9 3395.37   409.9 3396.51   421.9 3408.03
   430.3 3410.16     454 3418.36     478 3423.83     486 3427.17492.8665 3428.68
#Mann= 4 ,-1,0
       0     .06       0     100      .1       0  182.19    .045       0
   205.3      .1       0
Bank Sta=182.19,205.3
XS Rating Curve= 0 ,0
Exp/Cntr(USF)=0,0
Exp/Cntr=0.3,0.1

Type RM Length L Ch R = 1 ,73233   ,361.7,362.5,362.3
XS GIS Cut Line= 4
2196401.15088651452741.041426936 2196489.3464011452660.515087525
2196652.31637372452486.0413521352196776.94047043452420.853363088
#Sta/Elev= 30
       0 3483.57    24.7 3471.89      36 3461.83    44.5 3456.12    47.3 3454.95
    65.1 3455.19    72.8 3452.48    82.8 3443.82    96.2 3434.17   112.4  3420.1
   132.3 3401.33   140.8 3395.96   151.4 3393.78   171.9 3393.83   184.2 3393.01
     203 3393.82   223.2 3395.19   260.8 3394.12   279.4 3396.79   322.8 3397.32
     336 3395.41   350.2 3396.88   376.1 3396.74   385.1 3394.21   394.3 3393.79
   407.7 3396.26   416.7 3396.27   429.8 3399.95   447.6 3400.45498.8186 3417.09
#Mann= 4 ,-1,0
       0     .06       0     110      .1       0   171.9    .045       0
     203      .1       0
#XS Ineff= 2 , 0
                          319.93         3401.45
Permanent Ineff=
       F       F
Bank Sta=171.9,203
XS Rating Curve= 0 ,0
Exp/Cntr(USF)=0,0
Exp/Cntr=0.3,0.1

Type RM Length L Ch R = 1 ,72871   ,188.4,192.2,194.6
XS GIS Cut Line= 4
2196698.33142481452967.2820948062196767.35400145452892.507636781
2196913.06832991452733.3722517542197010.85031348 452620.25191782
#Sta/Elev= 30
       0 3444.75     8.5 3439.53    20.4 3440.14    30.1 3438.97    50.9 3425.73
    73.6 3413.27    93.4 3405.03   114.8 3400.89   127.3 3392.44   143.43389.759
   155.7 3388.35  192.073389.759   209.5 3392.16   220.8 3392.12   241.9 3390.24
   258.1 3390.57   277.4 3392.32   301.5  3392.3   305.7  3392.7     317 3395.81
   351.1 3394.62   365.4 3395.09   387.9 3401.75   397.1 3403.64   410.6 3408.05
   423.5 3409.51   432.4 3413.58   444.7 3417.81     456 3423.27467.0556 3426.76
#Mann= 5 ,-1,0
       0      .1       0      10     .06       0  141.76      .1       0
   143.4    .045       0  192.07      .1       0
#XS Ineff= 2 , 0
                          280.84         3395.91
Permanent Ineff=
       F       F
Bank Sta=143.4,192.07
XS Rating Curve= 0 ,0
Exp/Cntr(USF)=0,0
Exp/Cntr=0.3,0.1

Type RM Length L Ch R = 1 ,72678   ,127.1,150.7,173.9
XS GIS Cut Line= 4
2196738.59459452453093.8234853092196845.96304707453065.064078376
  2197043.444308452892.5076367812197146.97817296452695.026375844
#Sta/Elev= 30
       0 3441.68     5.8 3433.59     9.9 3430.88    14.1 3429.87    30.6 3430.26
    34.8 3429.59    47.2  3423.1    67.9 3407.84    84.5 3397.55    96.9 3393.01
   119.4 3389.44   135.3 3388.22   172.5 3389.79  232.593388.051   252.2 3386.28
  272.173388.052   282.7 3391.23   287.3 3391.71   325.3 3390.68   376.4 3393.06
   395.2  3395.1   431.4  3396.6   449.4 3395.88   469.7 3398.05     481 3397.76
   517.2 3406.05   545.3 3408.93   566.8 3412.68   584.9 3413.36596.3781 3415.19
#Mann= 4 ,-1,0
       0     .06       0      70      .1       0  232.59    .045       0
  272.17      .1       0
#XS Ineff= 2 , 0
                          290.75         3393.79
Permanent Ineff=
       F       F
Bank Sta=232.59,272.17
XS Rating Curve= 0 ,0
Exp/Cntr(USF)=0,0
Exp/Cntr=0.3,0.1

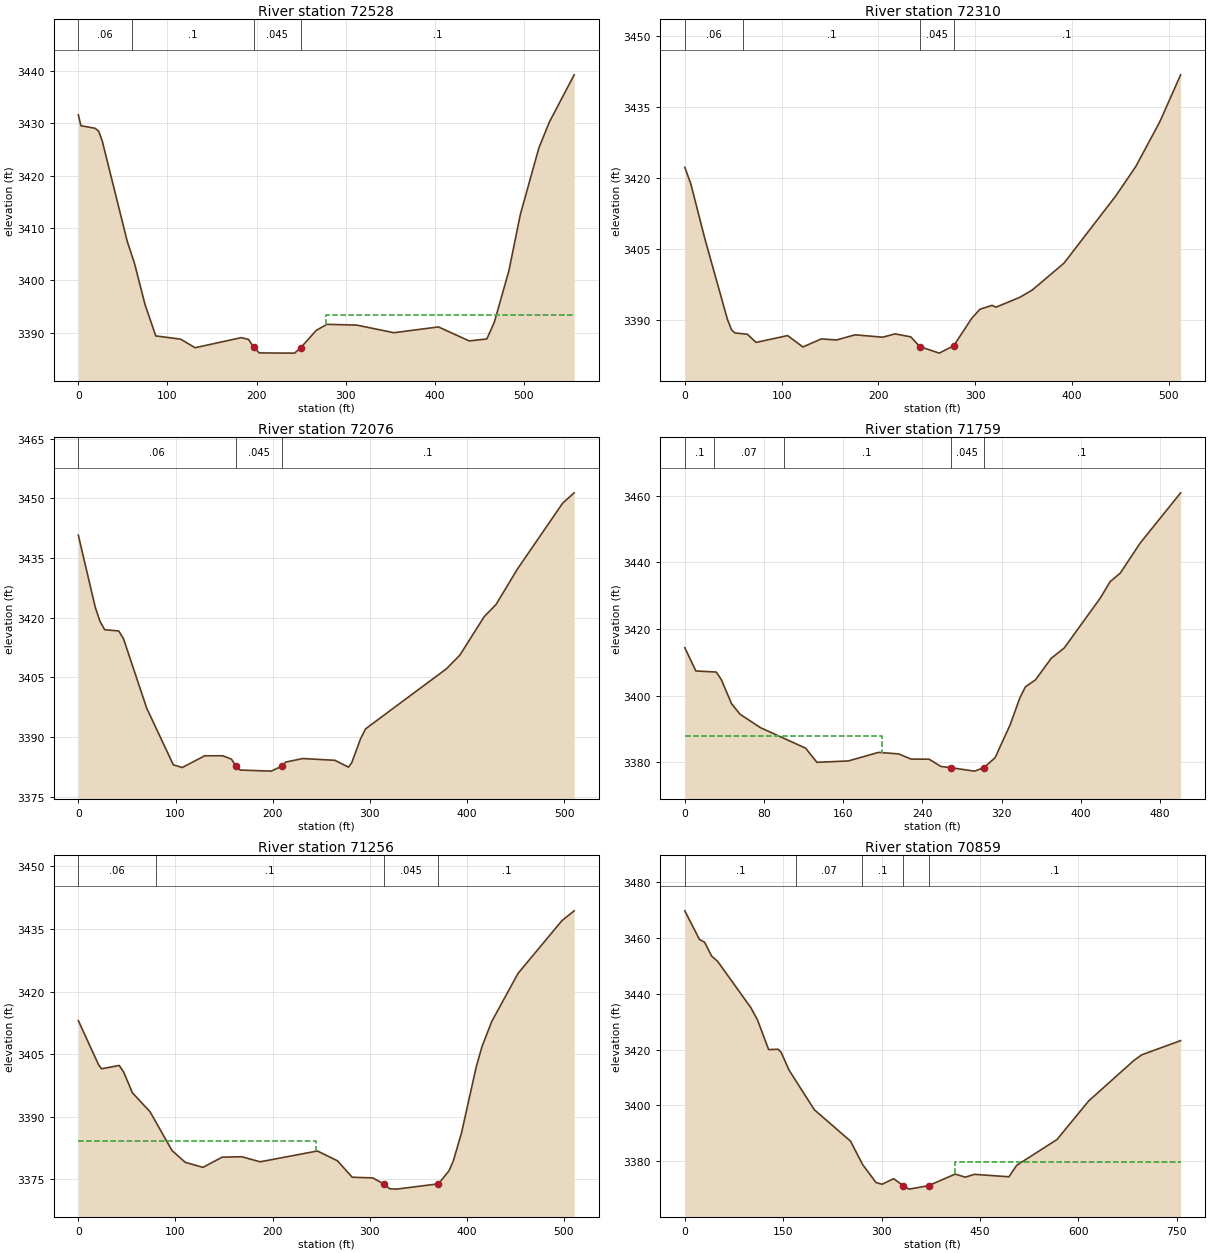
Type RM Length L Ch R = 1 ,72528   ,214.2,217.6,225.2
XS GIS Cut Line= 4
2196745.25767851453109.3207996112196811.60841186453109.320799611
2197026.74563815453119.3739410272197290.13794324 453197.78844407
#Sta/Elev= 30
       0 3431.58     2.9 3429.52    18.9 3429.02    22.9 3428.45    26.9 3426.56
    54.9 3407.44    63.1  3403.2    74.9 3395.35    86.9 3389.39     115 3388.76
     131 3387.13     183 3389.06   191.1  3388.7   196.8 3387.24   203.1 3386.14
   242.7  3386.1  249.37 3387.09   267.1 3390.45   279.1  3391.6   312.4 3391.45
   354.2    3390   404.2  3391.1   438.7 3388.43   458.5 3388.81   466.8 3391.95
   483.2 3401.79   496.1 3412.57   516.9 3425.27   528.7 3430.22   556.5 3439.23
#Mann= 4 ,-1,0
       0     .06       0      60      .1       0   196.8    .045       0
  249.37      .1       0
#XS Ineff= 2 , 0
                          277.53         3393.36
Permanent Ineff=
       F       F
Bank Sta=196.8,249.37
XS Rating Curve= 0 ,0
Exp/Cntr(USF)=0,0
Exp/Cntr=0.3,0.1

Type RM Length L Ch R = 1 ,72310   ,234.2,234.6,238.9
XS GIS Cut Line= 4
 2196746.2637697453252.9588703352196926.48938648453312.394977996
2197047.27889559453350.7408539062197237.09098135453398.673198794
#Sta/Elev= 30
       0 3422.26     6.2  3418.8    20.7 3407.22    44.1 3390.16    48.3 3387.98
    51.8 3387.33    64.6 3387.06    73.6 3385.33   106.2 3386.77     122 3384.37
     141 3386.06   156.9 3385.85   175.9 3386.93   204.5 3386.43   217.2 3387.13
   233.5  3386.5   242.7 3384.45   262.9 3383.07  277.873384.633   296.5 3390.43
   304.9 3392.31   317.4 3393.15   321.6 3392.77   346.3 3394.86   358.8 3396.35
   391.7 3402.03   445.3 3416.24   465.9 3422.41   490.7 3431.84 512.274 3441.77
#Mann= 4 ,-1,0
       0     .06       0      60      .1       0   242.7    .045       0
  277.87      .1       0
Bank Sta=242.7,277.87
XS Rating Curve= 0 ,0
Exp/Cntr(USF)=0,0
Exp/Cntr=0.3,0.1

Type RM Length L Ch R = 1 ,72076   ,314.1,316.8,320.6
XS GIS Cut Line= 4
2196665.73743029 453383.334848432196719.42165656453419.763430544
2196955.24879341453552.0567024342197112.46688464453628.748454254
#Sta/Elev= 30
       0 3440.76    17.4 3422.65    22.3 3419.08    27.1 3416.98    41.6 3416.66
    46.5  3414.7    70.3 3397.27    97.8 3382.97     107 3382.31     130 3385.26
   148.7 3385.26   157.5 3384.42   162.1  3382.7   166.6 3381.67   198.6  3381.4
   209.4 3382.65   213.4 3383.67   230.9 3384.57     264 3384.12     278  3382.4
   281.3  3383.5   290.5  3389.6   295.6 3392.04   378.7 3407.13   392.6 3410.58
   417.6 3420.25   429.8 3423.31     452  3432.3   498.3 3448.79510.2029 3451.41
#Mann= 3 ,-1,0
       0     .06       0   162.1    .045       0   209.4      .1       0
Bank Sta=162.1,209.4
XS Rating Curve= 0 ,0
Exp/Cntr(USF)=0,0
Exp/Cntr=0.3,0.1

Type RM Length L Ch R = 1 ,71759   ,484.1,503.2,518
XS GIS Cut Line= 4
2196487.42910731453594.237165935 2196575.6246219453665.177036368
2196755.85023868453808.9740710312196880.47433539453904.838760806
#Sta/Elev= 30
       0 3414.43    11.2 3407.45    31.8 3407.12    36.8 3404.91    47.2 3397.65
    55.8 3394.48    76.6 3390.42   122.1 3384.29   133.5 3380.05   165.1 3380.46
   195.8 3383.03   216.2 3382.57   228.6 3381.02   246.9 3380.99   258.7 3378.82
   268.6 3378.44   292.8 3377.41  302.17 3378.45   313.5 3381.42   328.8 3391.36
   338.4 3399.27   344.1 3402.68   354.3 3404.78   370.3 3411.27   383.4 3414.35
   419.9 3429.35   429.7 3434.22     440 3436.79   460.2 3445.84500.9771 3460.87
#Mann= 5 ,-1,0
       0      .1       0      30     .07       0     100      .1       0
   268.6    .045       0  302.17      .1       0
#XS Ineff= 2 , 0
           199.1 3387.89
Permanent Ineff=
       F       F
Bank Sta=268.6,302.17
XS Rating Curve= 0 ,0
Exp/Cntr(USF)=0,0
Exp/Cntr=0.3,0.1

Type RM Length L Ch R = 1 ,71256   ,397.1,397,393.6
XS GIS Cut Line= 4
2196176.82751244453784.0492516892196295.69972776454006.455331968
2196358.97042301454152.169660426 2196404.9854741454240.365175019
#Sta/Elev= 30
       0 3413.06      21 3402.39      24 3401.51    42.1  3402.3    46.6 3400.75
    55.7 3395.74    73.8 3391.22    96.5  3381.9   110.1 3379.08   128.3 3377.88
   148.1 3380.32   168.3 3380.42   187.2 3379.21   246.2  3381.8   266.8 3379.45
     282 3375.51   303.1 3375.35  314.383373.929   320.6 3372.75   327.6 3372.66
  370.76 3373.93   381.6 3377.04     386 3379.36   394.5 3386.11   409.7 3401.97
   415.6 3406.81   425.7 3412.86   452.8 3424.39   497.9    3437510.5164 3439.36
#Mann= 4 ,-1,0
       0     .06       0      80      .1       0  314.38    .045       0
  370.76      .1       0
#XS Ineff= 2 , 0
          245.15 3384.11
Permanent Ineff=
       F       F
Bank Sta=314.38,370.76
XS Rating Curve= 0 ,0
Exp/Cntr(USF)=0,0
Exp/Cntr=0.3,0.1

Type RM Length L Ch R = 1 ,70859   ,301.3,303.3,305.9
XS GIS Cut Line= 3
2195781.18357277453901.6282138952196061.27735966454391.951533784
2196250.83511652454419.261449603
#Sta/Elev= 30
       0 3469.64    22.4 3459.39    30.2 3458.42    40.9 3453.45    50.2 3451.54
   100.8 3434.97   110.9 3430.59   127.9 3419.99   142.3 3420.11   146.9 3419.02
   159.3 3412.53   197.6 3398.46   252.8 3387.22   271.3 3378.81   291.6 3372.43
   300.9  3371.8   318.5  3373.8   333.2  3371.3     342 3370.06  371.86  3371.3
   412.3 3375.44   427.9 3374.34   441.7 3375.35   494.4 3374.48   506.2 3378.58
   567.6  3387.8   616.1 3401.64   684.8 3416.07   696.9 3418.12   756.2  3423.2
#Mann= 5 ,-1,0
       0      .1       0     170     .07       0     270      .1       0
   333.2    .045       0  371.86      .1       0
#XS Ineff= 2 , 0
                          412.85          3379.6
Permanent Ineff=
       F       F
Bank Sta=333.2,371.86
XS Rating Curve= 0 ,0
Exp/Cntr(USF)=0,0
Exp/Cntr=0.3,0.1

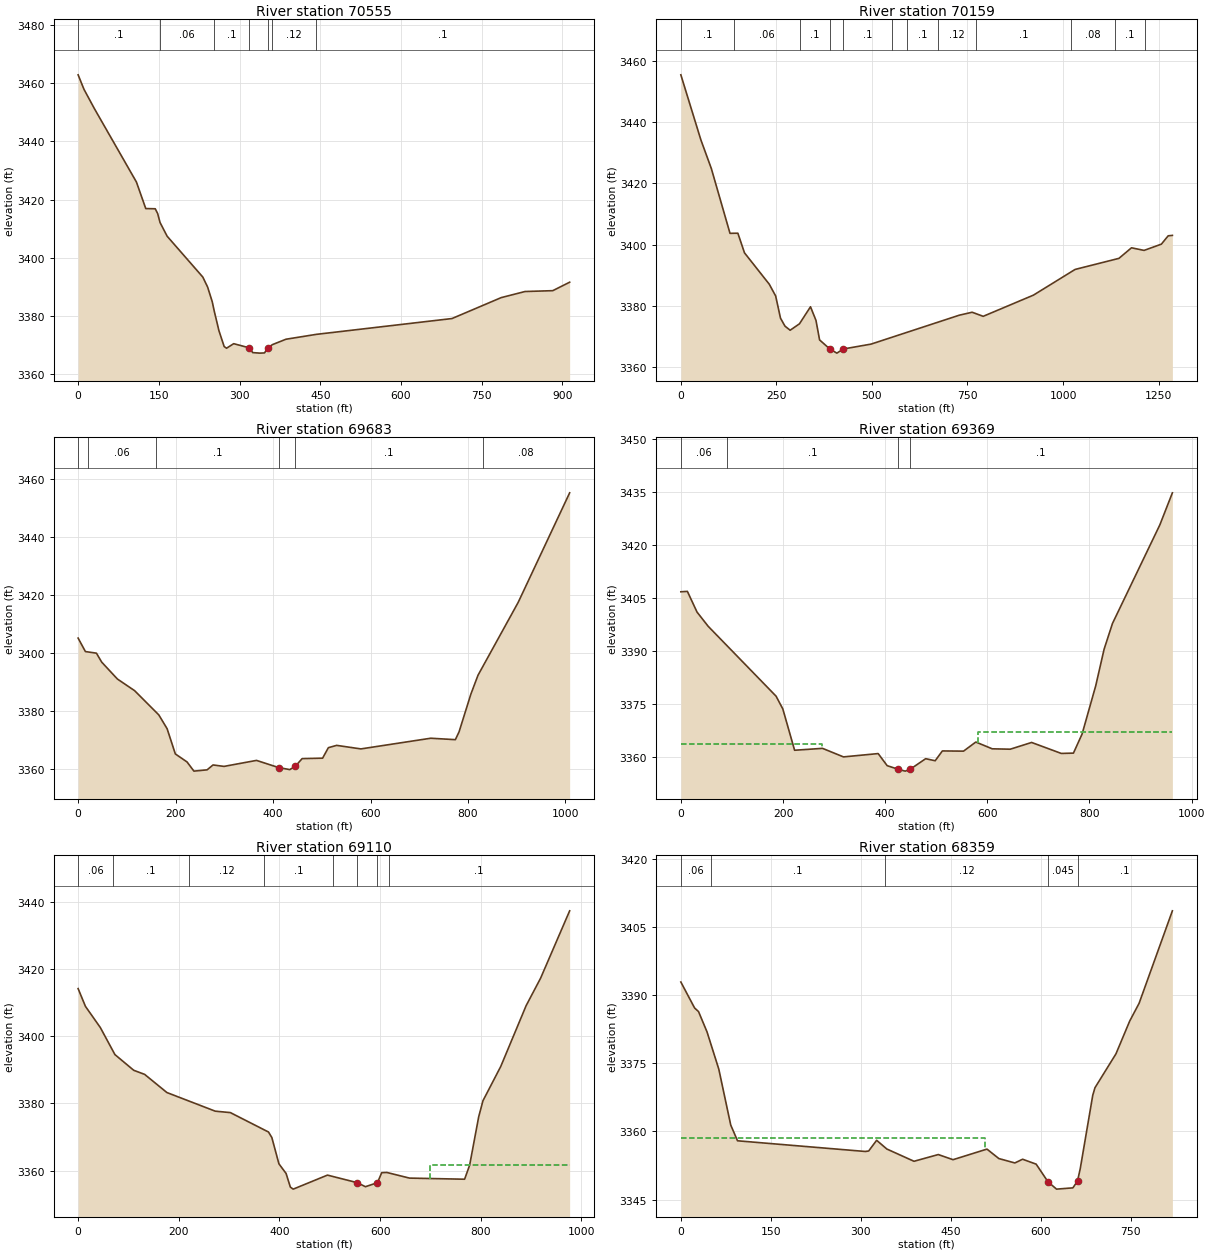
Type RM Length L Ch R = 1 ,70555   ,409.1,396.1,381.4
XS GIS Cut Line= 3
2195534.12146762454019.3134166492195758.41834587454499.260500212
2196069.53982215 454723.55737846
#Sta/Elev= 30
       0 3462.93    10.9 3457.94      30 3451.38   108.3 3426.06   125.7 3416.91
   143.3 3416.84   147.8  3415.2   152.2 3412.13   165.4  3407.4   231.7 3393.34
   240.7 3389.87   249.3 3384.81   252.7 3381.82   261.7 3374.86   271.4 3369.43
   275.8 3368.86   289.1 3370.42  318.05 3368.99   324.4 3367.35   337.6 3367.17
   346.4 3367.24     352 3368.93     361 3370.09   386.2 3371.95   442.3 3373.62
   694.7 3379.07   786.1 3386.27   830.4 3388.37   881.9 3388.66   913.3 3391.57
#Mann= 7 ,-1,0
       0      .1       0   152.2     .06       0   252.7      .1       0
  318.05    .045       0     352      .1       0     361     .12       0
   442.3      .1       0
Bank Sta=318.05,352
XS Rating Curve= 0 ,0
Exp/Cntr(USF)=0,0
Exp/Cntr=0.3,0.1

Type RM Length L Ch R = 1 ,70159   ,469.4,476.7,478.8
XS GIS Cut Line= 4
2195162.63845437454223.6215859862195300.67877786454469.322555783
2195944.04243501454899.0323716932196168.24077114454953.105403188
#Sta/Elev= 30
       0 3455.43    52.3 3434.24    79.8 3424.84   128.6 3403.71   149.2 3403.75
   166.5 3397.35   231.4  3387.1   248.1 3383.26   260.8    3376   272.5 3373.42
     286 3372.09   310.4 3374.19   339.2 3379.75   353.5 3375.32     363 3368.93
  389.61 3365.99   408.2 3364.62   425.4 3365.98   497.7 3367.56   728.6    3377
   762.2 3377.96   791.1 3376.63   922.5 3383.54  1031.6 3391.93  1146.2 3395.54
  1179.1 3398.99    1212 3398.14  1257.3 3400.18  1275.1  3402.9  1286.1 3403.04
#Mann= 12 ,-1,0
       0      .1       0     140     .06       0  311.82      .1       0
  389.61    .045       0   425.4      .1       0  551.82     .12       0
  591.82      .1       0  671.82     .12       0  771.82      .1       0
 1021.82     .08       0 1135.49      .1       0 1215.49     .08       0
Bank Sta=389.61,425.4
XS Rating Curve= 0 ,0
Exp/Cntr(USF)=0,0
Exp/Cntr=0.3,0.1

Type RM Length L Ch R = 1 ,69683   ,300.3,313.6,306.2
XS GIS Cut Line= 4
2194886.03932827454625.4186847362195010.30546435454761.710575917
2195298.92358685455046.3201133842195563.49019914455371.015501197
#Sta/Elev= 30
       0 3405.24      15  3400.6    37.6 3400.05    48.4 3396.96    80.6 3391.14
     116 3387.11   165.6 3378.76   182.6 3374.01   199.5 3365.31   223.6 3362.53
   237.6 3359.38   264.6 3359.82   276.9 3361.51   299.4 3361.01     366 3363.08
   411.6  3360.6   434.3 3359.91   445.6 3361.03   459.7  3363.7   501.7 3363.85
   513.5 3367.46   530.5 3368.26   580.3 3367.04   723.5 3370.72   774.1 3370.23
   781.7 3372.93   805.9 3385.92   820.5 3392.42   903.1 3417.591008.616 3455.33
#Mann= 6 ,-1,0
       0      .1       0      20     .06       0     160      .1       0
   411.6    .045       0   445.6      .1       0  829.78     .08       0
Bank Sta=411.6,445.6
XS Rating Curve= 0 ,0
Exp/Cntr(USF)=0,0
Exp/Cntr=0.3,0.1

Type RM Length L Ch R = 1 ,69369   ,261.1,259.5,257.9
XS GIS Cut Line= 2
2194673.34724533454761.9729131012195328.12868639455467.122157318
#Sta/Elev= 30
       0 3406.85    12.8 3406.97    31.7  3401.1    53.5 3397.08   186.4 3377.29
   199.6 3373.69   222.7 3361.97   277.3 3362.51   318.4 3360.09   386.3 3361.03
   403.9 3357.61     426 3356.56   439.2 3356.06   448.6 3356.55   479.3 3359.58
   497.9    3359     512 3361.78   553.4 3361.72   577.5  3364.3   609.6 3362.38
   644.9 3362.27   686.7 3364.18   744.8 3361.07   768.6 3361.16   785.5 3366.56
   812.2 3380.22   828.6 3390.58     845 3397.88   937.8 3425.82   962.3 3434.88
#Mann= 4 ,-1,0
       0     .06       0      90      .1       0     426    .045       0
   448.6      .1       0
#XS Ineff= 2 , 0
          275.57 3363.85  581.97         3367.26
Permanent Ineff=
       F       F
Bank Sta=426,448.6
XS Rating Curve= 0 ,0
Exp/Cntr(USF)=0,0
Exp/Cntr=0.3,0.1

Type RM Length L Ch R = 1 ,69110   ,734.7,751.1,734
XS GIS Cut Line= 4
 2194497.2065799454881.9681269592194745.73885206 455178.60341953
 2195062.4170698455455.1957869272195162.63169567455591.487678108
#Sta/Elev= 30
       0 3414.17    14.6 3408.87    44.1 3402.59    73.1 3394.54   110.5 3389.86
   132.2 3388.64   176.4 3383.24   272.4  3377.7   302.5 3377.27   378.3 3371.49
   384.9 3369.85     399 3362.02   413.2 3359.17   421.7  3355.1   427.4  3354.5
   495.4 3358.67   554.9 3356.41   570.8 3355.22   594.7 3356.41   603.2 3359.39
   613.3 3359.46   658.5 3357.78   767.9 3357.45   777.9 3361.62   795.9 3376.02
   804.4 3380.81   839.7 3390.99   890.2 3409.11   918.9 3417.27976.6215 3437.31
#Mann= 8 ,-1,0
       0     .06       0      70      .1       0     220     .12       0
     370      .1       0  506.99     .12       0   554.9    .045       0
   594.7     .12       0  616.99      .1       0
#XS Ineff= 2 , 0
                          699.42         3361.79
Permanent Ineff=
       F       F
Bank Sta=554.9,594.7
XS Rating Curve= 0 ,0
Exp/Cntr(USF)=0,0
Exp/Cntr=0.3,0.1

Type RM Length L Ch R = 1 ,68359   ,748.5,749.4,749.6
XS GIS Cut Line= 2
2194112.39110797455367.3042275552194677.15557964455961.434704519
#Sta/Elev= 30
       0  3392.9    22.9 3387.19    29.5 3386.39    43.6 3381.94    63.3 3373.72
    83.2 3361.41    94.5 3357.95   307.4  3355.6   313.2  3355.7   326.5 3358.06
   343.5 3356.14   388.8 3353.44   429.3 3354.92   453.9 3353.79   510.5 3356.12
   530.3 3354.04     557 3353.07   569.9 3353.89   592.5 3352.81   612.3 3348.92
   626.5 3347.31   653.8 3347.59   661.5  3349.1   666.1 3351.85   686.9 3367.97
   690.6 3369.63   725.6 3377.09   748.6 3384.33   764.2 3388.22   819.7 3408.57
#Mann= 5 ,-1,0
       0     .06       0      50      .1       0     340     .12       0
   612.3    .045       0   661.5      .1       0
#XS Ineff= 2 , 0
          507.04 3358.64
Permanent Ineff=
       F       F
Bank Sta=612.3,661.5
XS Rating Curve= 0 ,0
Exp/Cntr(USF)=0,0
Exp/Cntr=0.3,0.1

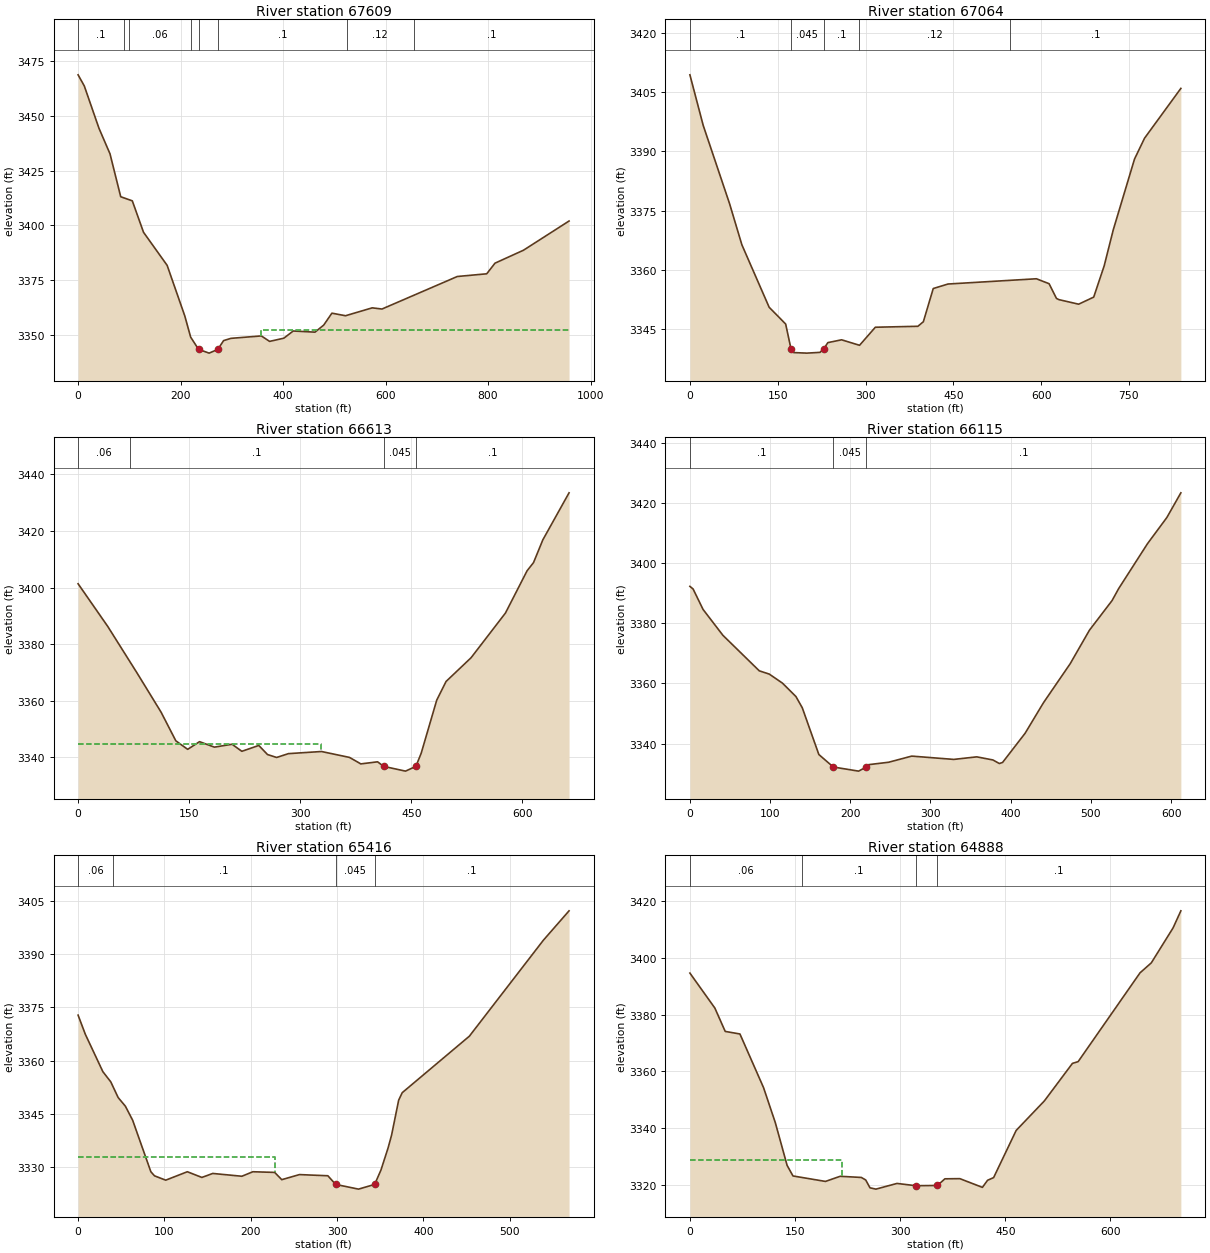
Type RM Length L Ch R = 1 ,67609   ,553.4,544.7,536.6
XS GIS Cut Line= 4
2193691.48098792  455948.2517462 2193827.7728791456080.535052346
2194040.22788594456284.9728891182194336.86317851456653.762712314
#Sta/Elev= 30
       0 3468.69    12.1 3463.62    40.7 3444.34    62.3 3432.63    83.2 3413.07
   105.8  3411.2   127.7 3396.85   173.8 3381.76   208.2  3358.7   219.7    3349
  235.143343.428   255.7 3341.72  272.643343.427     284 3347.44   298.2 3348.46
   357.6 3349.57   373.7 3347.07   401.4 3348.53   419.8 3351.81   462.3 3351.29
   479.3 3354.51   495.3 3359.95   521.9 3358.78     574 3362.38     593 3361.84
     740 3376.68   797.4 3377.91   813.6 3382.77     869 3388.65958.0595 3401.99
#Mann= 8 ,-1,0
       0      .1       0      90     .07       0     100     .06       0
  219.93      .1       0  235.14    .045       0  272.64      .1       0
  524.77     .12       0  654.77      .1       0
#XS Ineff= 2 , 0
                          356.83          3352.3
Permanent Ineff=
       F       F
Bank Sta=235.14,272.64
XS Rating Curve= 0 ,0
Exp/Cntr(USF)=0,0
Exp/Cntr=0.3,0.1

Type RM Length L Ch R = 1 ,67064   ,396.9,451.1,490.2
XS GIS Cut Line= 5
2193475.01739604456417.2561952642193535.14617156456553.548086445
 2193711.2580236456644.8494303542194033.27828724456750.645871567
2194139.32927054456860.151020843
#Sta/Elev= 30
       0 3409.34    22.7 3396.56    67.6 3376.82    88.8 3366.34   135.4 3350.54
   163.6  3346.3   172.7 3340.01   177.2 3339.08   199.7 3338.94   222.2 3339.13
228.7179 3340.06   235.7  3341.6   259.2 3342.31   289.8 3340.92   316.8 3345.49
   389.5 3345.73   398.8 3346.88   415.7 3355.28   440.9 3356.42   591.9 3357.75
   613.6  3356.5   626.2 3352.78   630.4 3352.47   664.1 3351.32   689.8 3353.11
   707.7 3361.02   723.2 3370.12   759.5 3388.03   776.7 3393.32   838.7 3405.91
#Mann= 5 ,-1,0
       0      .1       0   172.7    .045       0228.7179      .1       0
  288.97     .12       0  547.34      .1       0
Bank Sta=172.7,228.7179
XS Rating Curve= 0 ,0
Exp/Cntr(USF)=0,0
Exp/Cntr=0.3,0.1

Type RM Length L Ch R = 1 ,66613   ,500.4,498.4,497.6
XS GIS Cut Line= 4
2193326.69974976456441.3077054732193338.72550486456757.985923217
2193282.60531438456930.3550797112193230.49370892457086.689896066
#Sta/Elev= 30
       0 3401.34    39.9 3386.31    79.9 3369.66     112 3355.95     132 3345.78
     148 3342.77     164 3345.48     184 3343.55     208 3344.56   221.1 3342.07
     244 3344.14   255.8 3340.93   268.1 3339.89   284.1 3341.25   328.7    3342
   366.5 3339.91   381.8 3337.62   404.4 3338.35  412.663336.741   442.1 3335.06
  456.153336.743   463.3 3341.38   484.3 3360.18   496.9 3366.78   530.7 3375.18
   577.1 3390.99   606.3 3405.93     615 3408.83   627.6 3416.89662.9728 3433.51
#Mann= 4 ,-1,0
       0     .06       0      70      .1       0  412.66    .045       0
  456.15      .1       0
#XS Ineff= 2 , 0
          327.64 3344.55
Permanent Ineff=
       F       F
Bank Sta=412.66,456.15
XS Rating Curve= 0 ,0
Exp/Cntr(USF)=0,0
Exp/Cntr=0.3,0.1

Type RM Length L Ch R = 1 ,66115   ,699.5,698.6,699.7
XS GIS Cut Line= 4
2192925.84124628456425.2733653342192893.77256601456553.548086445
2192849.67813062456721.9086579042192821.61803538457026.561120545
#Sta/Elev= 30
       0 3392.32       4 3391.44    16.4 3384.65    41.1 3376.05    86.5 3364.21
    98.9 3363.13   115.3 3360.14   132.2 3355.66   140.1 3351.93   160.8 3336.35
  178.863332.196   210.4 3330.83  219.793332.196   222.8 3332.98   247.9 3333.79
   276.6 3335.83     329 3334.73   357.7 3335.58   377.8 3334.55   385.9 3333.36
   389.9 3333.72     418 3343.44   440.9  3353.6   474.2 3366.58   498.2 3377.73
   526.5 3387.62   534.5 3391.52   570.6 3406.53   594.7 3415.22612.2036 3423.45
#Mann= 3 ,-1,0
       0      .1       0  178.86    .045       0  219.79      .1       0
Bank Sta=178.86,219.79
XS Rating Curve= 0 ,0
Exp/Cntr(USF)=0,0
Exp/Cntr=0.3,0.1

Type RM Length L Ch R = 1 ,65416   ,523.1,528.7,532.2
XS GIS Cut Line= 4
 2192304.5105659456381.1789299522192232.35603527456597.642521827
2192188.26159989456790.0546034952192160.20150465456930.355079711
#Sta/Elev= 30
       0 3372.84     8.4 3367.45    28.7 3356.94    37.9 3354.06    46.4 3349.66
    54.8 3347.22    63.2 3343.28    84.3 3328.78    88.5 3327.64   101.5 3326.42
   126.5 3328.79   143.4 3327.19     156 3328.31   189.7 3327.52   202.4 3328.79
   227.7  3328.6   235.9 3326.56   256.4 3327.99   289.3 3327.66  298.363325.224
   324.8  3323.9   343.53325.225   350.8 3329.27     359 3335.45   363.1 3339.08
   371.3 3348.92   375.4 3351.02   453.2 3366.92   538.9 3393.91568.6516 3402.18
#Mann= 4 ,-1,0
       0     .06       0      40      .1       0  298.36    .045       0
   343.5      .1       0
#XS Ineff= 2 , 0
          227.49 3333.07
Permanent Ineff=
       F       F
Bank Sta=298.36,343.5
XS Rating Curve= 0 ,0
Exp/Cntr(USF)=0,0
Exp/Cntr=0.3,0.1

Type RM Length L Ch R = 1 ,64888   ,584.4,572.9,561.7
XS GIS Cut Line= 4
2191845.04654922456161.2278690952191774.91234545456377.474997379
2191719.38943413456523.5879218962191639.56139358456811.588863042
#Sta/Elev= 30
       0 3394.65    35.6 3382.31    50.4 3374.05    71.4 3373.15   105.1  3354.2
   121.9 3341.83   138.7 3326.77   147.1 3323.02   193.4 3321.09   214.4  3322.9
   244.7 3322.49   250.9 3321.59     257 3318.83   265.5 3318.37   295.5 3320.38
   322.3 3319.58   353.2 3319.66   363.9 3322.01   385.2 3322.07   417.4 3318.99
   424.8  3321.5   433.4 3322.44   465.6  3339.1   505.8 3349.51   545.9 3362.77
     554 3363.38   642.3 3394.73   658.4 3398.25   689.5 3410.61   700.6 3416.63
#Mann= 4 ,-1,0
       0     .06       0     160      .1       0   322.3    .045       0
   353.2      .1       0
#XS Ineff= 2 , 0
          216.74 3328.55
Permanent Ineff=
       F       F
Bank Sta=322.3,353.2
XS Rating Curve= 0 ,0
Exp/Cntr(USF)=0,0
Exp/Cntr=0.3,0.1

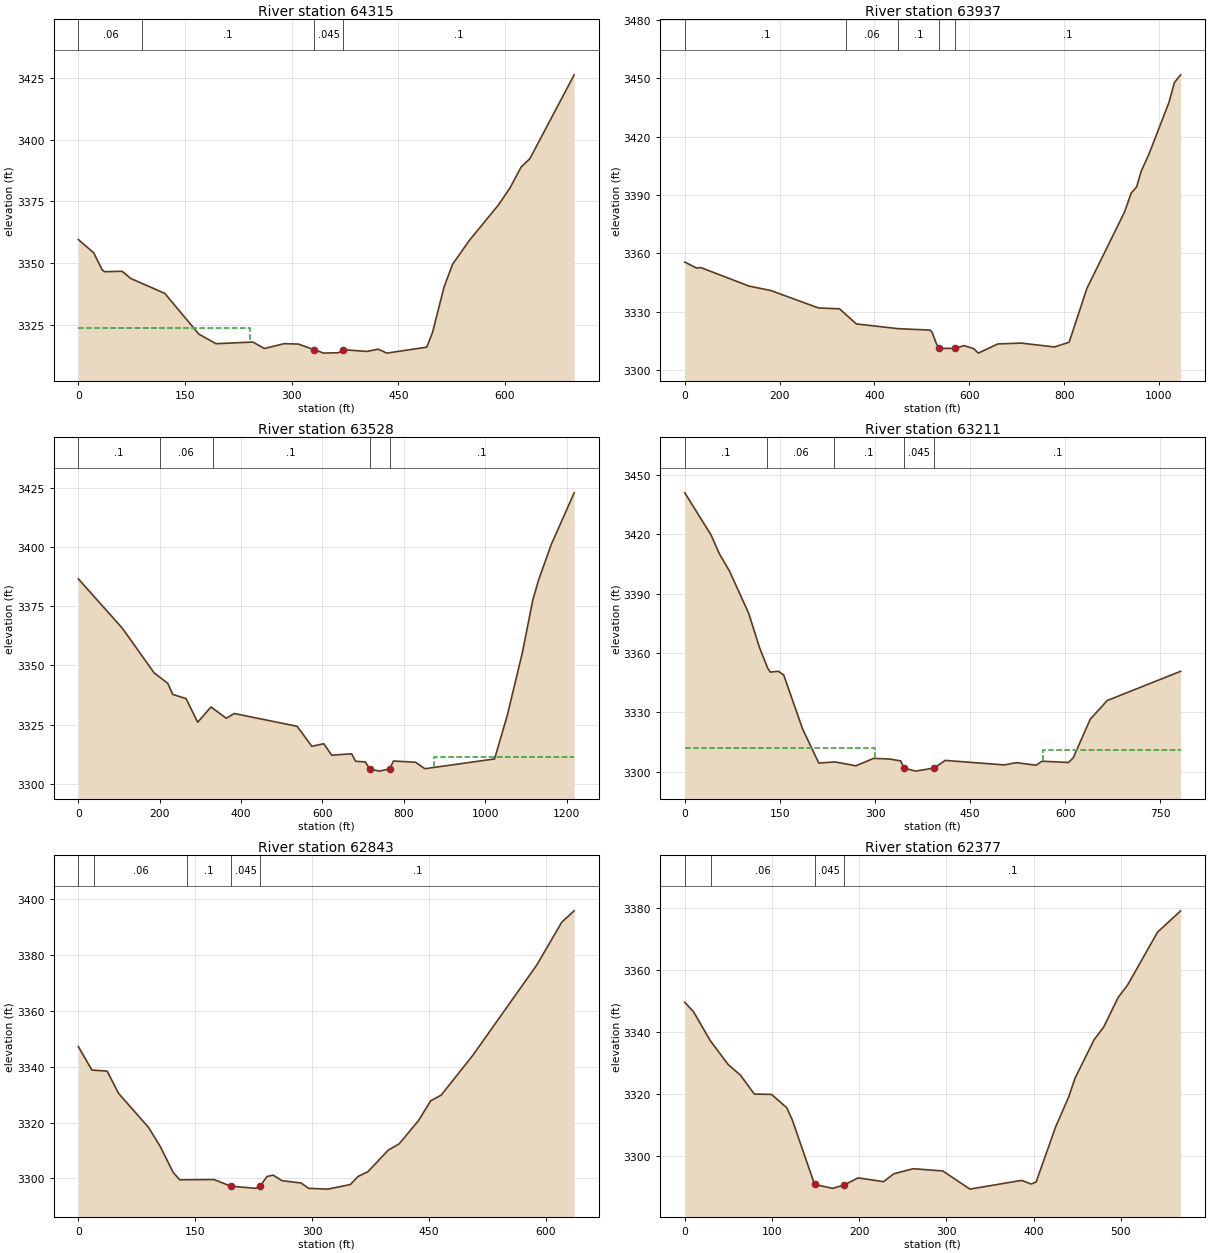
Type RM Length L Ch R = 1 ,64315   ,379.5,378,359.4
XS GIS Cut Line= 4
2191187.53838889456035.5707540122191187.53838889456319.029827573
2191199.22742286456506.0543709542191225.52774927456731.068274709
#Sta/Elev= 30
       0 3359.61    21.6 3354.25    33.6 3347.35      37 3346.61    61.6 3346.78
    73.6 3343.89   121.6 3337.83   169.6 3321.35   193.6  3317.5   245.6 3318.17
   261.6 3315.55   289.6 3317.52   309.7 3317.34   331.4 3315.09   344.9 3313.71
   365.8 3313.84   372.8 3315.08   405.8 3314.37   421.9 3315.28   433.9 3313.69
   490.1  3316.1   498.2 3322.06   514.4 3340.42   526.3 3349.55   550.2 3359.34
   590.8 3373.55   606.9 3380.35     623    3389   635.1 3392.28697.3943 3426.19
#Mann= 4 ,-1,0
       0     .06       0      90      .1       0   331.4    .045       0
   372.8      .1       0
#XS Ineff= 2 , 0
          241.75 3323.92
Permanent Ineff=
       F       F
Bank Sta=331.4,372.8
XS Rating Curve= 0 ,0
Exp/Cntr(USF)=0,0
Exp/Cntr=0.3,0.1

Type RM Length L Ch R = 1 ,63937   ,417.6,408.5,391.7
BEGIN DESCRIPTION:
new xs added per checkras comments
END DESCRIPTION:
XS GIS Cut Line= 3
2190641.86180813455910.8347659232190933.00066138456519.025354661
2191181.45947333456794.921336019
#Sta/Elev= 30
       0 3355.57    24.8 3352.47    33.5 3352.77   135.6 3343.21   181.4 3340.94
     282 3331.97   326.3 3331.53   361.8 3323.76     450 3321.32     517 3320.59
   521.5 3319.46   530.3 3313.77  536.76 3311.19   570.3 3311.17     589  3312.6
   609.3 3311.02     619 3308.74   660.3 3313.47   708.9 3313.91   779.5 3311.91
   810.5 3314.33     848 3342.03   927.3 3381.33   941.5 3391.15   952.8 3394.21
   962.5 3402.32   978.3 3410.76  1020.8 3437.55  1032.5 3447.91  1045.6 3451.88
#Mann= 5 ,-1,0
       0      .1       0     340     .06       0     450      .1       0
  536.76    .045       0   570.3      .1       0
Bank Sta=536.76,570.3
XS Rating Curve= 0 ,0
Exp/Cntr(USF)=0,0
Exp/Cntr=0.3,0.1

Type RM Length L Ch R = 1 ,63528   ,319.4,317.2,315.5
XS GIS Cut Line= 4
2190012.79047578456444.686942657 2190340.0834267456511.898887934
2190804.72252666456839.1918388512191053.11449834457034.983157703
#Sta/Elev= 30
       0 3386.64   108.3 3365.73   186.2 3346.89   219.9 3342.42   232.1 3337.74
   264.8 3335.96   293.4 3325.97     326 3332.43   363.6 3327.65   383.2 3329.65
   537.8 3324.26     574  3315.8   603.3 3316.87   622.9 3312.02   671.8 3312.61
   681.6 3309.44   705.4  3309.2  715.713306.256   739.9 3305.28  765.263306.254
   774.6 3309.56   828.9 3309.05   851.8  3306.3  1023.1 3310.44  1054.3 3328.84
  1091.5 3355.44  1117.1 3377.68  1131.3 3386.17  1162.7 3401.271218.742 3423.05
#Mann= 5 ,-1,0
       0      .1       0     200     .06       0     330      .1       0
  715.71    .045       0  765.26      .1       0
#XS Ineff= 2 , 0
                          875.01         3311.39
Permanent Ineff=
       F       F
Bank Sta=715.71,765.26
XS Rating Curve= 0 ,0
Exp/Cntr(USF)=0,0
Exp/Cntr=0.3,0.1

Type RM Length L Ch R = 1 ,63211   ,365.8,368.3,367.3
XS GIS Cut Line= 4
2190185.20372671456874.2589407352190407.29537198456953.159919974
2190638.15379271457096.350585999 2190883.6235059457219.085442593
#Sta/Elev= 30
       0 3440.97    41.4 3419.67    54.7 3410.05    70.4 3401.46   100.8 3380.05
   117.8 3362.77   130.5 3352.48   134.7 3350.35   147.5 3350.77     156 3348.87
   185.7 3321.63   211.3 3304.36   236.7 3304.95   269.7 3302.99   297.9 3306.76
   323.5 3306.37   340.3 3305.47  345.833301.865   363.8 3300.29  393.223301.865
   410.6 3305.71   503.6 3303.43     523 3304.57   553.9 3303.27   563.3 3305.31
   604.9 3304.67   612.5 3307.03   639.3 3326.55   666.1 3335.98781.7941 3350.76
#Mann= 5 ,-1,0
       0      .1       0     130     .06       0  235.69      .1       0
  345.83    .045       0  393.22      .1       0
#XS Ineff= 2 , 0
          299.56 3311.88  564.76         3310.91
Permanent Ineff=
       F       F
Bank Sta=345.83,393.22
XS Rating Curve= 0 ,0
Exp/Cntr(USF)=0,0
Exp/Cntr=0.3,0.1

Type RM Length L Ch R = 1 ,62843   ,460.3,466,469.8
XS GIS Cut Line= 4
2190193.97050218457233.6967350452190313.78310029457318.442231264
2190588.47539838457508.3890331352190708.28799648457607.745821806
#Sta/Elev= 30
       0 3347.24    17.4 3338.82      37 3338.42    51.7 3330.43    90.2 3318.23
   105.6 3311.19   121.7 3302.13   130.1 3299.47     174 3299.56  195.833297.182
   227.5 3296.42   233.8 3297.39   242.1 3300.65     250 3301.16   261.5 3299.14
   285.8 3298.34   295.6 3296.41   320.1 3296.13   349.1 3297.77   358.8 3300.63
   371.8 3302.41   397.7  3310.1   411.8 3312.36   436.6 3320.69   452.3  3327.8
   465.8 3329.85   506.6 3344.19   588.5 3376.51   620.6 3391.88636.3737 3395.89
#Mann= 5 ,-1,0
       0      .1       0      20     .06       0     140      .1       0
  195.83    .045       0   233.8      .1       0
Bank Sta=195.83,233.8
XS Rating Curve= 0 ,0
Exp/Cntr(USF)=0,0
Exp/Cntr=0.3,0.1

Type RM Length L Ch R = 1 ,62377   ,494.9,488.4,479.8
XS GIS Cut Line= 4
2189890.05561919457517.1558086062190082.92467955457698.335835006
2190205.65953615 457823.992950092190293.32729086457917.505221781
#Sta/Elev= 30
       0 3349.59      10 3346.54    29.2 3337.19    49.6 3329.49    63.8 3326.01
    79.7 3319.89    99.4 3319.78   116.9 3315.48   123.2 3311.55  148.793290.638
   169.5 3289.37   182.6 3290.44   198.7 3292.76   227.9 3291.53   239.6 3294.08
   261.9 3295.73   295.8    3295   326.9 3289.12     386 3291.95   397.2 3290.78
   402.8 3291.44   425.2  3309.3   440.1 3318.94   447.4 3325.04   469.3 3337.51
   480.3 3341.61   496.7  3351.1     508 3355.34   541.9 3372.27568.4539 3379.21
#Mann= 4 ,-1,0
       0      .1       0      30     .06       0  148.79    .045       0
   182.6      .1       0
Bank Sta=148.79,182.6
XS Rating Curve= 0 ,0
Exp/Cntr(USF)=0,0
Exp/Cntr=0.3,0.1