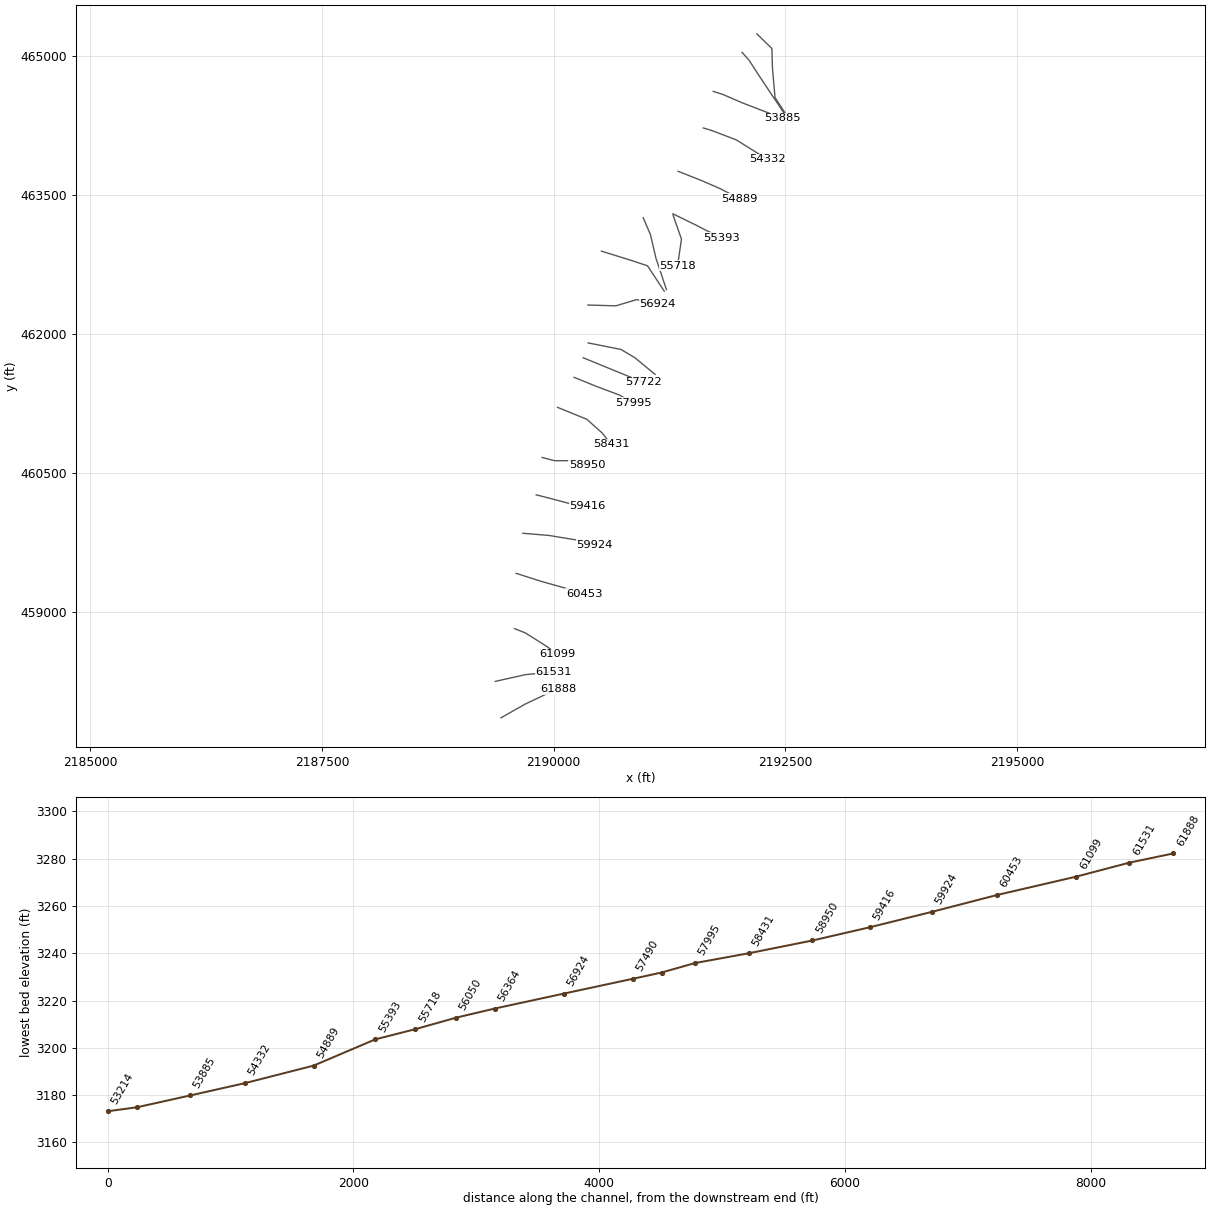
HEC-RAS study WILLIAMSRV.prj: WILLIAMSRV

--- WILLIAMSRV.g01 (geometry) --- (continued)

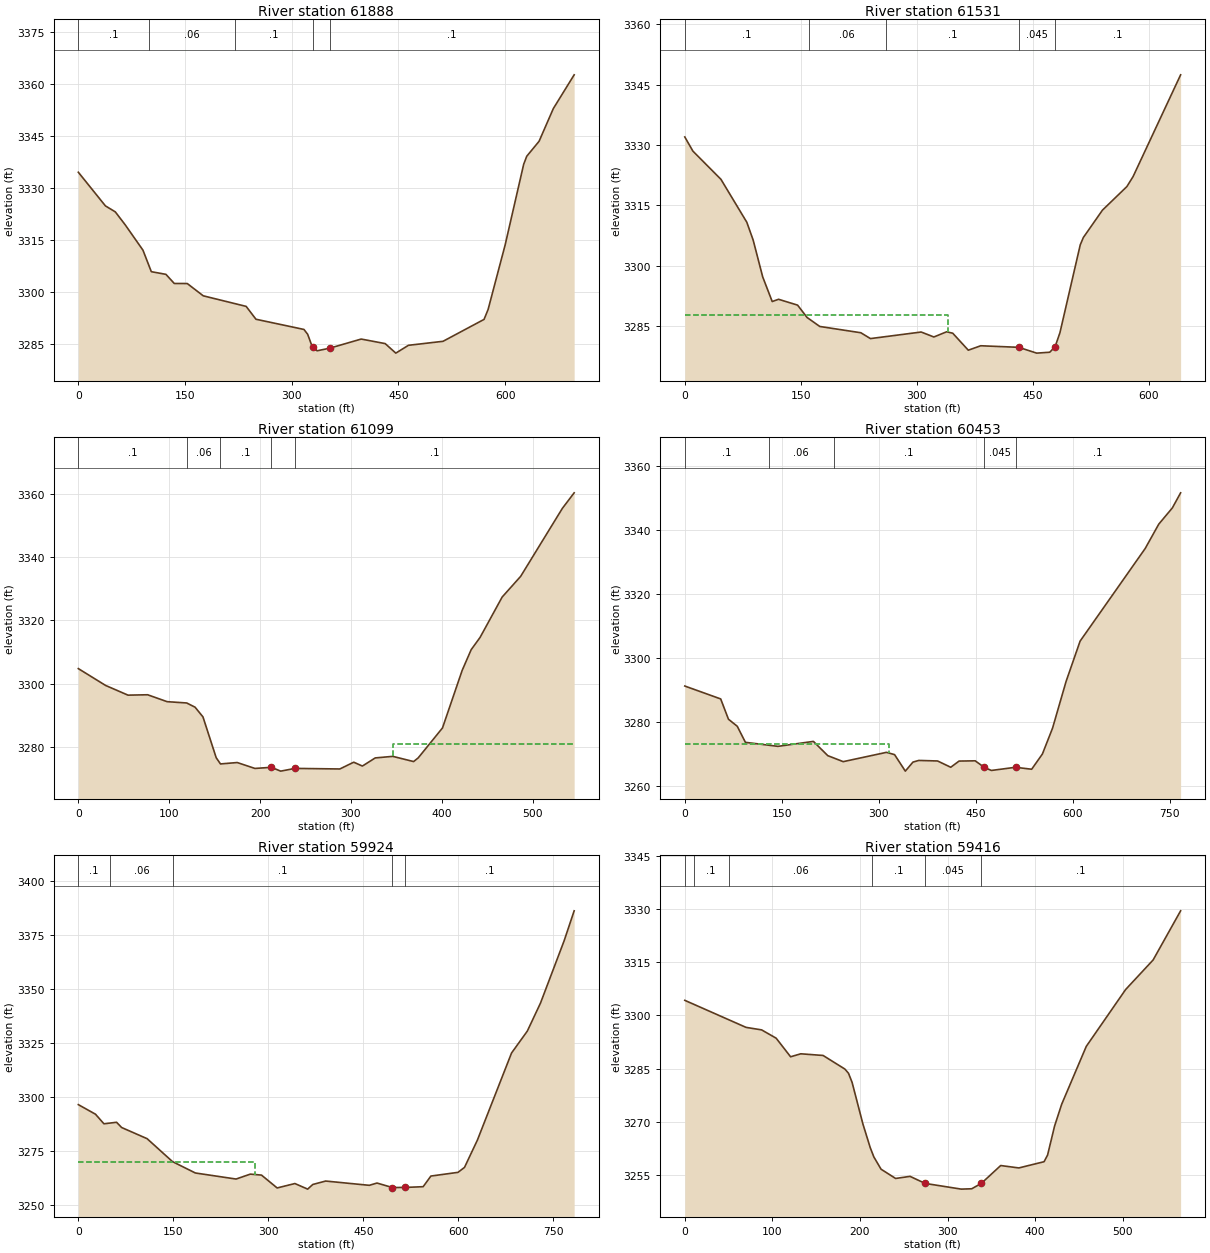
Type RM Length L Ch R = 1 ,61888   ,360.1,357.7,354.1
XS GIS Cut Line= 4
 2189430.9559854 457854.518184392189691.34204185   458002.250718
2189913.43368711458107.4520236522190053.70209465458165.897193458
#Sta/Elev= 30
       0 3334.55   38.06 3324.82   51.99 3323.08   65.79 3319.37   90.87    3312
  102.61 3305.78  123.15 3305.01  134.89 3302.37  153.17 3302.35  175.62  3298.8
  235.95 3295.74  249.74 3292.02  317.22 3289.07  322.43 3287.67  329.23 3283.87
  335.71  3282.9  353.26 3283.64  397.67 3286.29  431.35 3284.98  446.36 3282.22
  464.06 3284.48  512.75 3285.64  570.41 3291.98  576.07 3294.83  600.09 3313.55
  626.09 3336.83  630.43 3339.18  647.76  3343.5  667.83 3352.98  697.08 3362.73
#Mann= 5 ,-1,0
       0      .1       0     100     .06       0     220      .1       0
  329.23    .045       0  353.26      .1       0
Bank Sta=329.23,353.26
XS Rating Curve= 0 ,0
Exp/Cntr(USF)=0,0
Exp/Cntr=0.3,0.1

Type RM Length L Ch R = 1 ,61531   ,444.6,431.8,415
XS GIS Cut Line= 4
2189369.89360791458247.7204311872189697.18655883458320.776893446
2189907.58917013458341.2327028782190001.10144182458352.921736839
#Sta/Elev= 30
       0    3332    10.5 3328.48    46.7 3321.49    80.2 3310.81    88.4 3306.38
   100.7 3297.26     113 3291.13   121.2 3291.69   145.8 3290.24   158.1 3287.17
   174.5 3284.94   227.6 3283.38     240 3281.93   305.6 3283.56     322 3282.33
   338.5 3283.62   346.4 3283.26   366.5 3279.05   382.6 3280.15   431.7 3279.76
   454.9 3278.32   471.8 3278.54  478.753279.926     485 3283.41   511.2 3305.19
   515.2 3307.02   539.9 3313.82   571.5 3319.68   579.5 3322.15640.9821 3347.43
#Mann= 5 ,-1,0
       0      .1       0     160     .06       0     260      .1       0
   431.7    .045       0  478.75      .1       0
#XS Ineff= 2 , 0
          339.98  3287.7
Permanent Ineff=
       F       F
Bank Sta=431.7,478.75
XS Rating Curve= 0 ,0
Exp/Cntr(USF)=0,0
Exp/Cntr=0.3,0.1

Type RM Length L Ch R = 1 ,61099   ,637.3,645.4,651.9
XS GIS Cut Line= 4
2189577.37396073458817.5608368012189694.26430034458770.804700956
 2189916.3559456 458630.536293422190044.93531918 458539.94628022
#Sta/Elev= 30
       0 3304.79    30.1 3299.46    54.7 3296.41    76.3 3296.53    97.8 3294.35
   119.3 3293.94   128.5 3292.61   137.2 3289.55   151.8 3276.64   156.5 3274.69
   174.9 3275.13   194.4 3273.27   212.5 3273.62   222.8 3272.42   238.6 3273.28
   287.9  3273.1   303.2 3275.24   312.7 3274.02   326.9 3276.59   346.2 3277.08
   369.1 3275.44   374.2 3276.61   400.9 3286.05   422.6 3304.25   432.5 3310.77
   442.2  3314.6   466.6 3327.38     487 3333.93   532.9 3355.39545.8601 3360.29
#Mann= 5 ,-1,0
       0      .1       0     120     .06       0  155.89      .1       0
   212.5    .045       0   238.6      .1       0
#XS Ineff= 2 , 0
                          346.26         3280.91
Permanent Ineff=
       F       F
Bank Sta=212.5,238.6
XS Rating Curve= 0 ,0
Exp/Cntr(USF)=0,0
Exp/Cntr=0.3,0.1

Type RM Length L Ch R = 1 ,60453   ,526.5,529.6,533
XS GIS Cut Line= 4
2189594.90751167459413.7015688272189869.59980976459326.033814117
2190170.59243426459241.2883178982190328.39439274459191.609923562
#Sta/Elev= 30
       0 3291.22    55.5 3287.19    67.5 3280.85    81.1 3278.65    93.7 3273.63
   144.1 3272.38   198.8 3273.93     221 3269.48   244.9  3267.6   311.8 3270.51
   324.3 3269.79   340.9 3264.64   352.7 3267.46   361.7 3267.98   390.8 3267.81
   411.1 3265.85     424 3267.78   448.9 3267.86     463 3265.81   473.9 3264.85
   511.3 3265.84   536.2 3265.23   552.8 3269.98   568.5 3278.07   589.4 3292.65
   611.1 3305.25   711.7 3334.18   732.7 3341.79   753.7 3346.86 766.475 3351.57
#Mann= 5 ,-1,0
       0      .1       0     130     .06       0     230      .1       0
     463    .045       0   511.3      .1       0
#XS Ineff= 2 , 0
           316.3 3273.18
Permanent Ineff=
       F       F
Bank Sta=463,511.3
XS Rating Curve= 0 ,0
Exp/Cntr(USF)=0,0
Exp/Cntr=0.3,0.1

Type RM Length L Ch R = 1 ,59924   ,512,507.5,495.3
XS GIS Cut Line= 4
2189667.96397393459846.195825395  2189948.500789459822.817757472
2190269.94922293459770.2171046472190439.44021537459723.460968801
#Sta/Elev= 30
       0 3296.57    27.1 3292.14    40.4 3287.72    60.4 3288.41    68.4 3285.99
   108.6 3280.84   148.7 3270.24   184.8 3264.98   249.1 3262.18   271.6 3264.45
   289.3    3264     314 3258.06     342  3260.1   362.2 3257.52   370.3 3259.67
   390.6 3261.25   459.5 3259.28   471.7 3260.33     496 3258.26   516.6 3258.31
   544.6 3258.65   556.8 3263.56   599.6 3265.27   609.9 3267.57   630.3 3280.22
   684.2 3320.44   709.1 3330.56   729.9 3343.51   767.2 3372.26783.0548 3386.13
#Mann= 5 ,-1,0
       0      .1       0      50     .06       0     150      .1       0
     496    .045       0   516.6      .1       0
#XS Ineff= 2 , 0
          278.41 3270.06
Permanent Ineff=
       F       F
Bank Sta=496,516.6
XS Rating Curve= 0 ,0
Exp/Cntr(USF)=0,0
Exp/Cntr=0.3,0.1

Type RM Length L Ch R = 1 ,59416   ,461.4,466.4,473.6
XS GIS Cut Line= 4
2189811.15463995460261.1565310212189960.18982296460223.167170647
2190202.73727766 460158.877483862190363.46149462460144.266191408
#Sta/Elev= 30
       0 3304.25    69.9 3296.62    87.7 3295.91   104.3 3293.57   120.8 3288.32
   132.4 3289.16   157.9 3288.69   182.8 3284.85   186.9 3283.67     191 3281.11
   203.4 3269.32   211.7  3262.7   215.9 3260.03   224.1 3256.59   240.7 3253.98
   257.2 3254.57  274.343252.586   315.7 3250.97   327.6 3251.07  338.533252.586
   360.7 3257.63   381.4 3256.95   410.2 3258.71   414.2 3260.58   422.2 3268.77
   430.3 3274.92   458.4 3291.26   503.3 3307.29   534.7 3315.64566.1109 3329.51
#Mann= 6 ,-1,0
       0     .12       0      10      .1       0      50     .06       0
   213.8      .1       0  274.34    .045       0  338.53      .1       0
Bank Sta=274.34,338.53
XS Rating Curve= 0 ,0
Exp/Cntr(USF)=0,0
Exp/Cntr=0.3,0.1

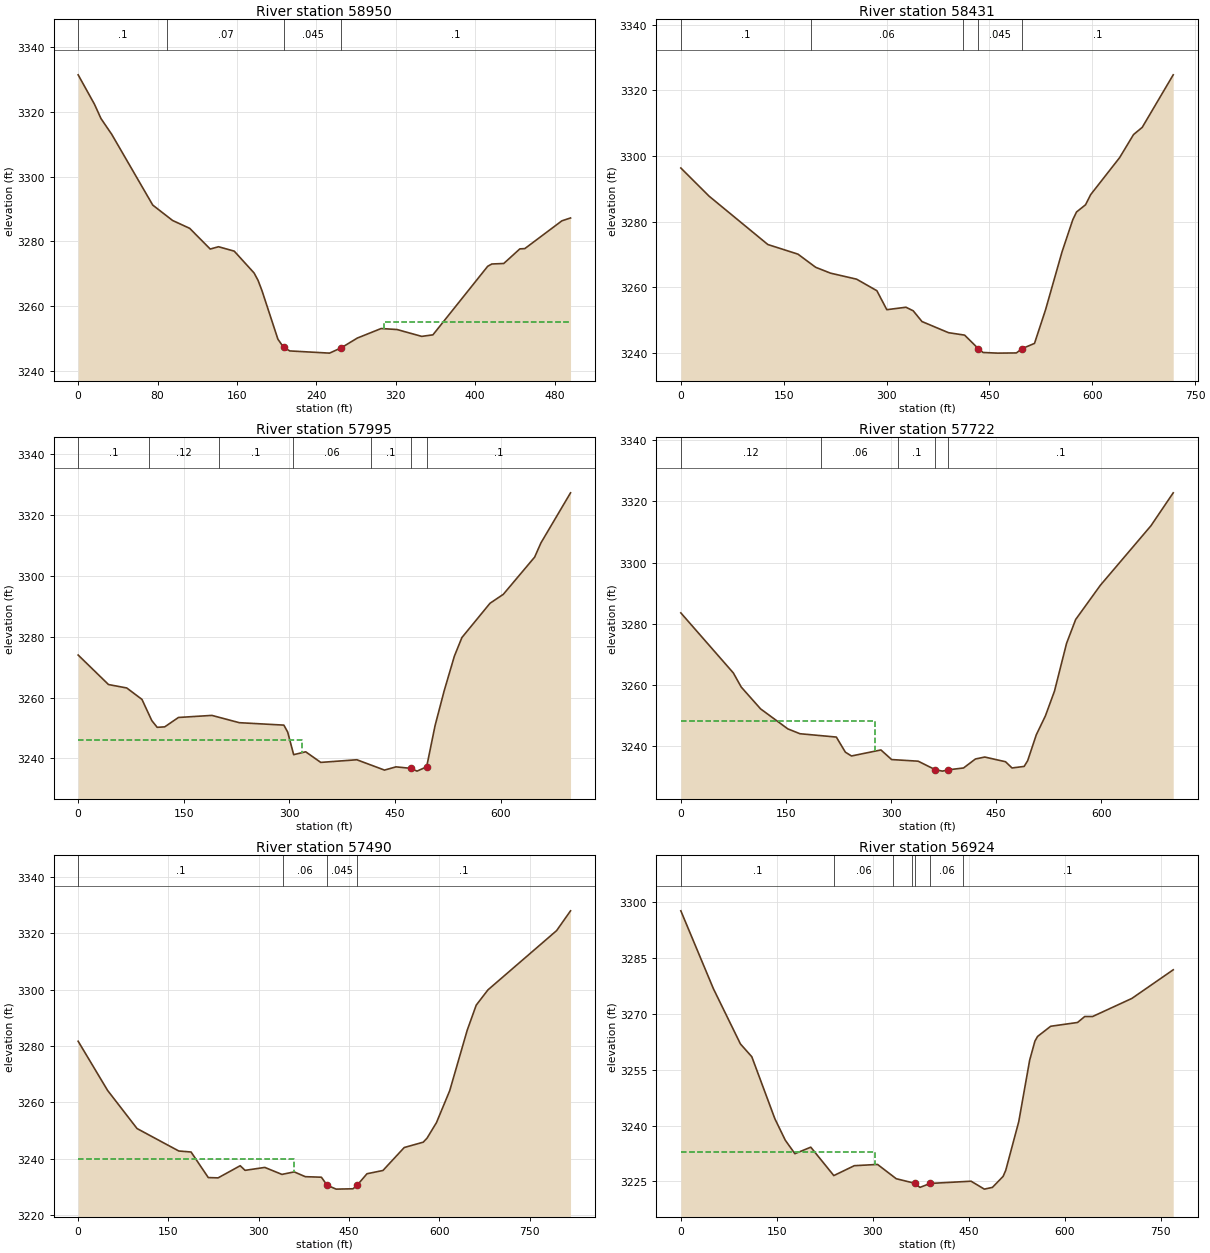
Type RM Length L Ch R = 1 ,58950   ,550,518.5,494.4
XS GIS Cut Line= 4
2189875.44432674 460664.486831072190009.86821729460629.361100802
2190193.97050218460629.3611008022190360.53923613460582.604964957
#Sta/Elev= 30
       0 3331.48   16.42 3322.39   22.98 3317.96   33.83 3313.07   75.17 3291.18
   95.09 3286.43  112.38 3283.99  133.05 3277.59  141.43  3278.3  157.24 3276.94
  177.24 3270.18  181.24  3267.9  185.24 3264.67  201.24  3249.7  207.07 3247.15
  213.24 3246.07  253.24 3245.39  265.06 3247.04  281.24 3250.05  305.24    3253
  321.24 3252.69   346.1 3250.57  357.42 3251.05  412.58 3272.25  416.73 3272.96
  428.78 3273.12     445 3277.64  449.97 3277.72  487.36 3286.32  496.05  3287.2
#Mann= 4 ,-1,0
       0      .1       0      90     .07       0  207.07    .045       0
  265.06      .1       0
#XS Ineff= 2 , 0
                          307.82         3255.15
Permanent Ineff=
       F       F
Bank Sta=207.07,265.06
XS Rating Curve= 0 ,0
Exp/Cntr(USF)=0,0
Exp/Cntr=0.3,0.1

Type RM Length L Ch R = 1 ,58431   ,424.1,436.8,450.2
XS GIS Cut Line= 4
2190042.01306069461205.0460233962190357.61697764461076.466649822
 2190521.2634531460930.3537253062190620.62024177460807.618868712
#Sta/Elev= 30
       0 3296.37    41.2 3287.79   126.9 3273.06   170.8 3270.13   196.7 3266.12
   218.3 3264.34   256.3 3262.51   285.9 3258.99   300.4 3253.21   328.3 3253.96
   338.9 3252.87   351.7  3249.6   390.3 3246.21   413.9 3245.46  433.843241.348
   440.7 3240.18   462.2 3239.98   489.4 3240.04  497.713241.348   515.8 3242.95
   531.9 3253.19   555.9  3270.8   571.6  3280.6   577.1 3282.98   590.2 3285.16
   597.7 3288.26   639.9 3299.52   660.2 3306.55   672.9 3308.75718.0847 3324.75
#Mann= 5 ,-1,0
       0      .1       0     190     .06       0  410.79      .1       0
  433.84    .045       0  497.71      .1       0
Bank Sta=433.84,497.71
XS Rating Curve= 0 ,0
Exp/Cntr(USF)=0,0
Exp/Cntr=0.3,0.1

Type RM Length L Ch R = 1 ,57995   ,275.2,272.7,275.7
XS GIS Cut Line= 4
 2190220.2708286461529.4167158222190456.97376631461432.982185641
2190714.13251346461336.5476554612190860.24543798461251.802159241
#Sta/Elev= 30
       0 3273.93    43.1 3264.25      69 3263.13    90.6 3259.38   104.5 3252.45
   112.2 3250.22   122.9 3250.37   142.4 3253.45   189.9 3254.13   228.8 3251.74
   292.1 3250.94   297.5 3248.67     306 3241.25   323.1 3242.19   344.5 3238.71
   395.7 3239.58     435 3236.19   451.3 3237.25   472.3 3236.76   481.2 3235.85
  494.853237.271   506.8 3250.79   519.6  3262.1   534.2 3273.56   544.9 3279.67
   584.8 3290.91   603.7 3293.85   648.2 3306.06   657.1 3310.71699.1495 3327.14
#Mann= 7 ,-1,0
       0      .1       0     100     .12       0     200      .1       0
  305.59     .06       0  415.59      .1       0   472.3    .045       0
  494.85      .1       0
#XS Ineff= 2 , 0
          318.39    3246
Permanent Ineff=
       F       F
Bank Sta=472.3,494.85
XS Rating Curve= 0 ,0
Exp/Cntr(USF)=0,0
Exp/Cntr=0.3,0.1

Type RM Length L Ch R = 1 ,57722   ,235.1,231.5,232
BEGIN DESCRIPTION:
new xs added per checkras comments
END DESCRIPTION:
XS GIS Cut Line= 2
2190318.91709316461740.4355565842190968.97222957461473.746269853
#Sta/Elev= 30
       0 3283.55    74.9 3263.93    86.2 3259.31   113.8 3252.18   152.7 3245.64
     170 3244.06   221.9 3242.97   234.8 3238.03   243.5 3236.79   285.5 3238.76
   300.8 3235.62   338.6 3235.09   362.9 3232.33   373.2 3231.84   381.8 3232.27
   403.4 3232.87   420.4 3235.81   433.7 3236.44   463.3 3234.91   472.6 3232.87
   489.9 3233.38   494.9 3235.25   507.2  3243.7   520.2 3249.88   533.2    3258
   550.4 3273.59   563.4 3281.39   598.7 3292.59   670.8 3312.01   702.6 3322.78
#Mann= 5 ,-1,0
       0     .12       0     200     .06       0     310      .1       0
   362.9    .045       0   381.8      .1       0
#XS Ineff= 2 , 0
          277.63 3248.34
Permanent Ineff=
       F       F
Bank Sta=362.9,381.8
XS Rating Curve= 0 ,0
Exp/Cntr(USF)=0,0
Exp/Cntr=0.3,0.1

Type RM Length L Ch R = 1 ,57490   ,545.3,566.1,597.6
XS GIS Cut Line= 4
 2190372.2282701461900.5435440932190725.82154742461830.409340326
2190877.77898892461739.8193271262191094.02611721461561.561559216
#Sta/Elev= 30
       0 3281.73    48.9 3264.27    97.8 3250.73   167.1 3242.76   187.5  3242.4
   216.1 3233.32   232.4 3233.22   269.1 3237.53   277.2 3235.89   309.9 3236.93
   338.4 3234.45   358.8 3235.34   377.2 3233.64   403.9 3233.45  413.43  3230.6
   428.4 3229.22   456.4 3229.34  463.273230.603   479.6 3234.68   506.1 3235.84
   541.5    3244     573 3245.89   579.3 3247.31     595 3252.84     617 3264.18
   646.1 3285.68     661 3294.55   680.5 3299.98   794.5 3321.02817.6404 3328.05
#Mann= 4 ,-1,0
       0      .1       0     340     .06       0  413.43    .045       0
  463.27      .1       0
#XS Ineff= 2 , 0
          357.93 3239.82
Permanent Ineff=
       F       F
Bank Sta=413.43,463.27
XS Rating Curve= 0 ,0
Exp/Cntr(USF)=0,0
Exp/Cntr=0.3,0.1

Type RM Length L Ch R = 1 ,56924   ,572,560.5,550
XS GIS Cut Line= 4
2190369.30601161462309.6597327392190670.29863611462300.892957268
2190895.31253986462368.1049025452191123.24870211 462318.42650821
#Sta/Elev= 30
       0 3297.73    50.9 3276.78    93.1 3261.94   110.9 3258.49   146.9 3241.83
   163.2 3236.05   178.2 3232.43     203 3234.18     239 3226.54     271  3229.2
   307.3 3229.54   336.5  3225.7  365.083224.489   373.6 3223.37   389.6 3224.43
   453.4 3225.03   474.2  3222.9   486.8 3223.37   503.5 3226.33   507.6 3227.96
   527.9 3241.02     545 3257.59   553.2  3262.7   557.3 3263.95   577.8 3266.69
   619.8 3267.71     631 3269.31   643.3 3269.31   704.7 3274.18769.2449 3281.87
#Mann= 7 ,-1,0
       0      .1       0     240     .06       0  331.12      .1       0
  361.12     .06       0  365.08    .045       0   389.6     .06       0
  441.12      .1       0
#XS Ineff= 2 , 0
          303.08 3232.85
Permanent Ineff=
       F       F
Bank Sta=365.08,389.6
XS Rating Curve= 0 ,0
Exp/Cntr(USF)=0,0
Exp/Cntr=0.3,0.1

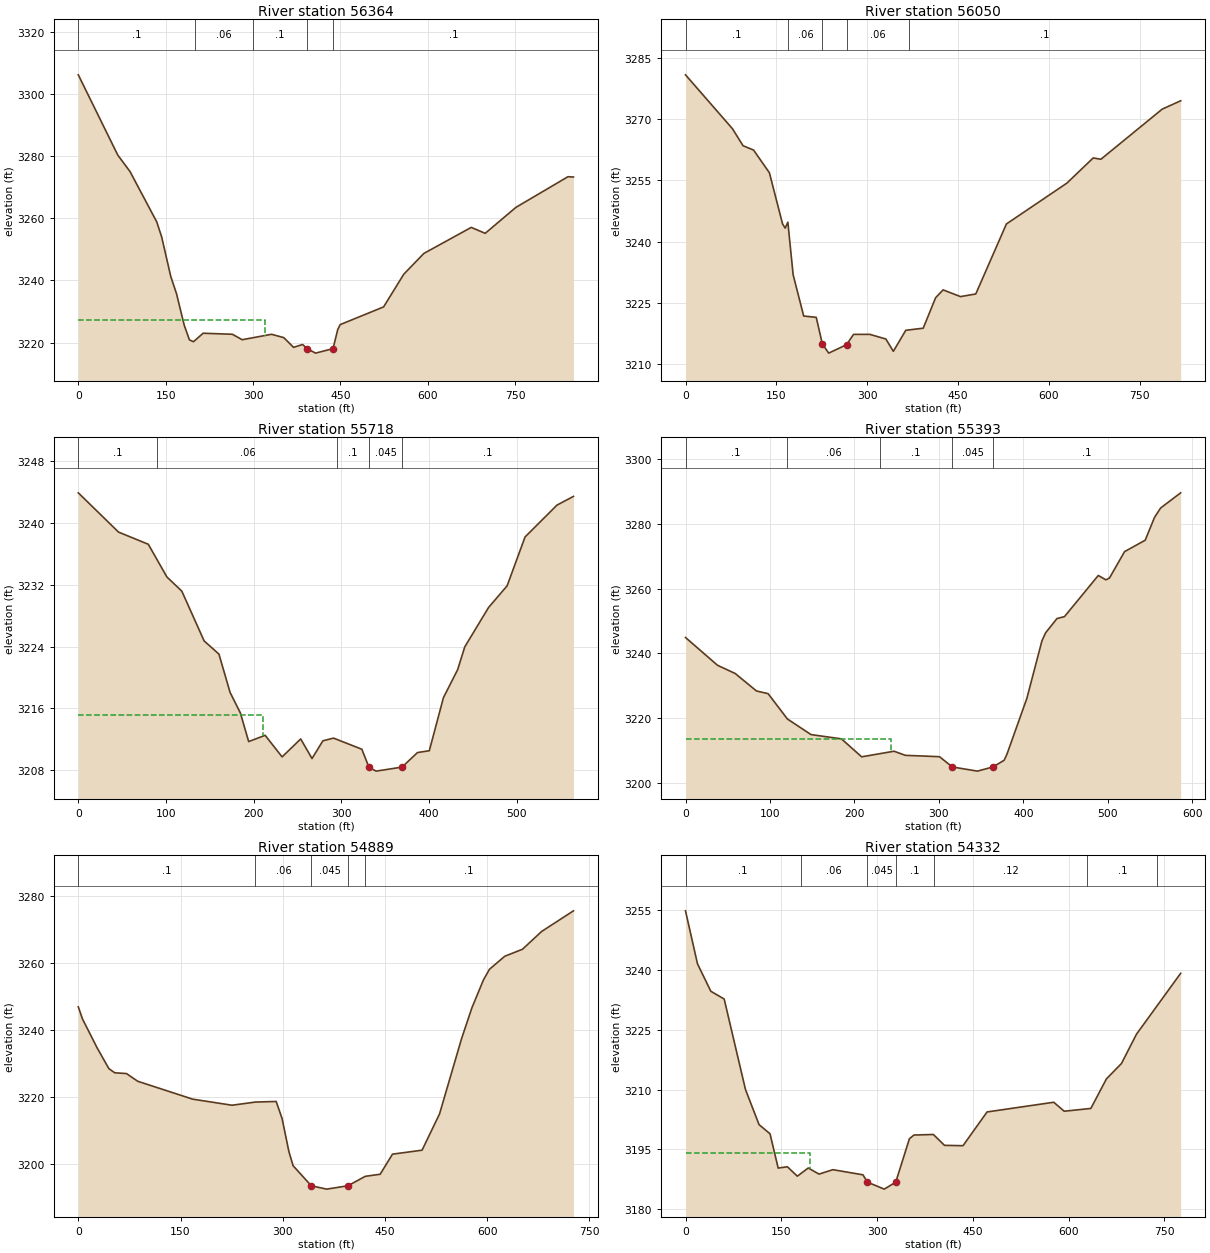
Type RM Length L Ch R = 1 ,56364   ,337.2,313.9,274.1
XS GIS Cut Line= 4
2190515.41893612462891.1891723132190816.41156062462797.676900623
2191012.20287948462733.3872138362191193.38290588462458.694915745
#Sta/Elev= 30
       0 3306.25    67.8  3280.4    88.8  3275.1   134.8 3258.85   143.2    3254
   158.8  3241.3   168.6 3235.79     182 3225.55   190.8 3220.89   197.7 3220.27
   214.4 3223.01   264.7 3222.67   281.4 3220.92   331.8 3222.67   352.8  3221.6
   369.7 3218.46   385.1 3219.38  393.253218.048   407.3  3216.6  437.473218.047
   445.4  3224.1   449.7 3225.78   524.3 3231.49   558.9 3242.01   593.4 3248.71
   674.8  3257.1   698.8 3255.19   751.5 3263.55   840.9 3273.43850.3229 3273.33
#Mann= 5 ,-1,0
       0      .1       0     200     .06       0     300      .1       0
  393.25    .045       0  437.47      .1       0
#XS Ineff= 2 , 0
          320.48 3227.27
Permanent Ineff=
       F       F
Bank Sta=393.25,437.47
XS Rating Curve= 0 ,0
Exp/Cntr(USF)=0,0
Exp/Cntr=0.3,0.1

Type RM Length L Ch R = 1 ,56050   ,339.5,331.8,316.4
XS GIS Cut Line= 4
 2190965.6622579463252.4507673852191044.34772287463069.446940223
2191102.79289268462818.132710055 2191216.7609738462476.228466687
#Sta/Elev= 30
       0 3280.84   77.58 3267.65      95  3263.5  112.41 3262.43  138.54 3256.88
  160.31 3244.35  164.66 3243.33  169.02 3244.79  177.72 3231.95  195.14 3221.83
   215.9  3221.5  225.94 3215.01  236.44 3212.75  265.92 3214.81  277.51 3217.34
  304.39 3217.34  330.89  3216.2  343.21 3213.19  363.75 3218.34  392.53 3218.85
  413.03 3226.31  425.35 3228.22   454.1 3226.58  479.31 3227.22  529.91 3244.35
  629.83 3254.35  673.26 3260.51  685.91 3260.18  787.11 3272.44  817.62 3274.49
#Mann= 5 ,-1,0
       0      .1       0     170     .06       0  225.94    .045       0
  265.92     .06       0   369.2      .1       0
Bank Sta=225.94,265.92
XS Rating Curve= 0 ,0
Exp/Cntr(USF)=0,0
Exp/Cntr=0.3,0.1

Type RM Length L Ch R = 1 ,55718   ,288.7,325.3,362.8
BEGIN DESCRIPTION:
new xs added per checkras comment
END DESCRIPTION:
XS GIS Cut Line= 3
2191288.30886721463280.5455427072191379.03656255463020.513487296
2191336.91298971462734.559233215
#Sta/Elev= 30
       0 3243.87    45.9 3238.79    79.8 3237.22     101 3232.99     118 3231.16
   143.4 3224.73   160.3 3223.02     173 3218.07   184.7 3215.42   194.2 3211.71
     213 3212.52   232.3 3209.73   253.5 3212.05   266.4 3209.52   278.8 3211.81
   290.9 3212.16   323.2 3210.72   331.3 3208.39   339.4 3207.89     369 3208.41
   386.6 3210.29   400.1 3210.53   416.2 3217.39   432.4 3221.01   440.5 3223.95
   467.6 3229.04   488.8 3231.85   509.2 3238.16   545.6 3242.28   564.4 3243.41
#Mann= 5 ,-1,0
       0      .1       0      90     .06       0  295.41      .1       0
   331.3    .045       0     369      .1       0
#XS Ineff= 2 , 0
          210.25  3215.1
Permanent Ineff=
       F       F
Bank Sta=331.3,369
XS Rating Curve= 0 ,0
Exp/Cntr(USF)=0,0
Exp/Cntr=0.3,0.1

Type RM Length L Ch R = 1 ,55393   ,497.8,504,500
XS GIS Cut Line= 4
 2191286.2804584463294.0103219142191531.99212227463174.210605201
 2191650.5693929463113.0883007562191811.93227663463034.851751066
#Sta/Elev= 30
       0 3244.89    37.9  3236.3    58.9 3233.75      84 3228.36    97.8 3227.53
   120.6 3219.71   148.6 3214.88   184.6 3213.56   208.5 3208.01   246.9 3209.74
   260.2 3208.47   300.6 3208.05  315.933204.876   345.5 3203.59  363.893204.876
   377.1 3206.94   380.4 3208.75   404.1 3226.12   421.9 3243.85   426.3 3246.35
   439.7 3250.74   448.6 3251.34   488.6 3264.05   497.7  3262.7   501.9 3263.29
   519.7 3271.42   544.1 3274.94   555.2 3282.03   562.4  3284.9586.0936 3289.59
#Mann= 5 ,-1,0
       0      .1       0     120     .06       0     230      .1       0
  315.93    .045       0  363.89      .1       0
#XS Ineff= 2 , 0
          243.83 3213.64
Permanent Ineff=
       F       F
Bank Sta=315.93,363.89
XS Rating Curve= 0 ,0
Exp/Cntr(USF)=0,0
Exp/Cntr=0.3,0.1

Type RM Length L Ch R = 1 ,54889   ,555,556.5,554.5
XS GIS Cut Line= 4
2191342.41808888463753.2554269592191593.73231905463653.898638288
2191795.36815488463566.2308835782192005.77076619463458.107319436
#Sta/Elev= 30
       0 3246.83     6.2  3243.2    27.7 3234.58    44.9 3228.39    53.5 3227.16
    70.7 3226.93    87.2 3224.63   167.9 3219.29   225.6 3217.48     260 3218.43
   290.4  3218.6   299.1 3213.49   309.1 3203.62   315.2 3199.45   341.93193.449
   364.5 3192.45  395.653193.448   421.2 3196.27     443 3196.89   461.1 3202.88
   504.5 3204.07   530.1 3214.87   562.4  3237.3   577.6 3246.52   594.5 3254.83
   603.4 3258.04   625.9 3261.93   651.9 3264.02   679.9 3269.31  726.67 3275.48
#Mann= 5 ,-1,0
       0      .1       0     260     .06       0   341.9    .045       0
  395.65     .06       0  420.24      .1       0
Bank Sta=341.9,395.65
XS Rating Curve= 0 ,0
Exp/Cntr(USF)=0,0
Exp/Cntr=0.3,0.1

Type RM Length L Ch R = 1 ,54332   ,450.3,447,445.6
XS GIS Cut Line= 4
2191614.18812848464220.8167854112191710.62265866464191.594200508
 2191970.7036643464092.2374118372192306.76339069463881.834800534
#Sta/Elev= 30
       0 3254.74    18.8 3241.47    39.7  3234.6    60.6 3232.66      94 3209.98
   115.3  3201.2   132.4 3198.93   145.2 3190.34   159.6 3190.67   175.2 3188.31
   192.3 3190.36   209.2 3188.83   230.9 3189.94     278 3188.65  285.033186.812
   311.4 3185.07  329.333186.813   350.8 3197.69   357.9 3198.61   388.3 3198.75
   405.7 3196.03   434.7 3195.94   472.4 3204.39   576.9 3206.82   593.3 3204.57
     635 3205.27   659.4 3212.67   682.9 3216.51   706.5 3223.86775.6695  3239.1
#Mann= 7 ,-1,0
       0      .1       0  180.76     .06       0  285.03    .045       0
  329.33      .1       0  389.18     .12       0  629.18      .1       0
  739.18     .06       0
#XS Ineff= 2 , 0
          194.71 3194.06
Permanent Ineff=
       F       F
Bank Sta=285.03,329.33
XS Rating Curve= 0 ,0
Exp/Cntr(USF)=0,0
Exp/Cntr=0.3,0.1

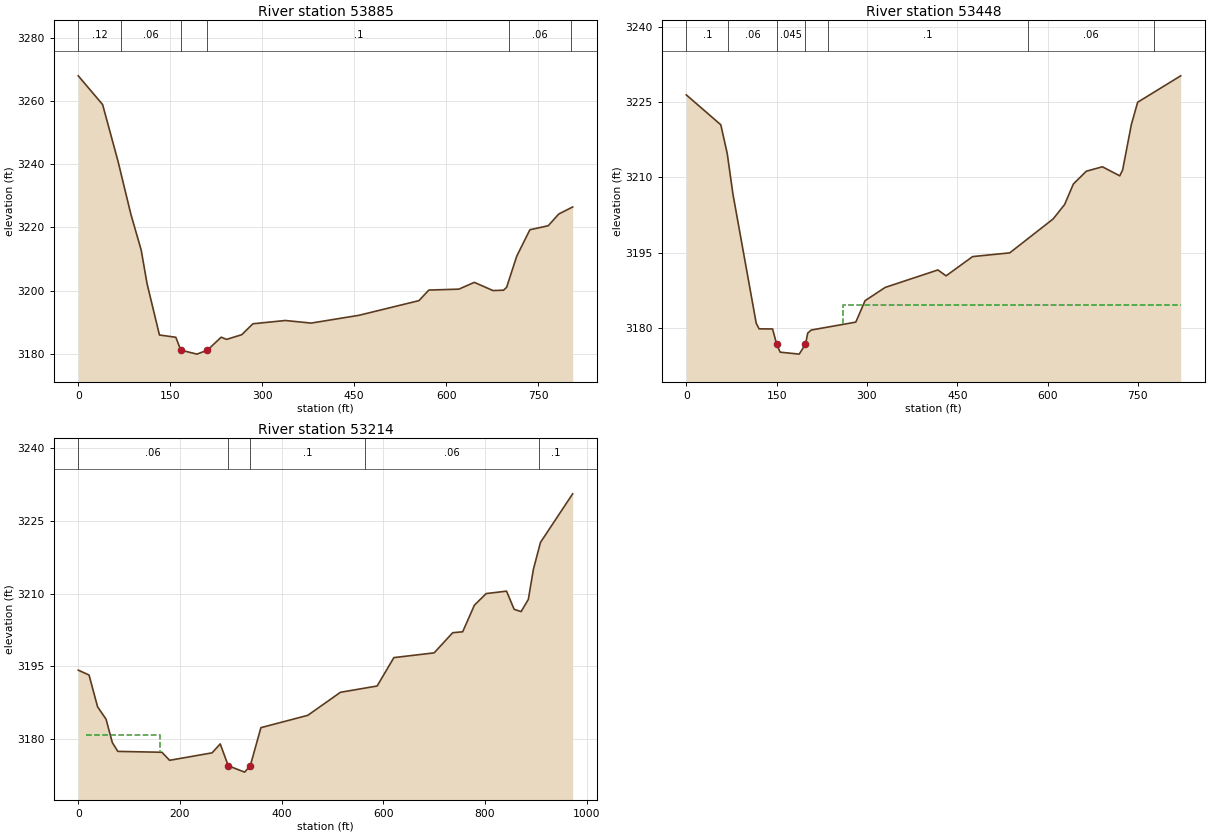
Type RM Length L Ch R = 1 ,53885   ,455,437,415.7
XS GIS Cut Line= 4
2191722.31169262464615.3216816052191824.59073979464583.176838211
2192040.83786807464489.6645665212192473.33212464464323.095832573
#Sta/Elev= 30
       0 3268.08    39.7 3258.98    64.8 3241.03    85.8  3224.2   102.6 3212.87
   112.2 3202.19   132.4 3185.92   159.1 3185.19  167.193181.127   193.6 3179.85
  210.713181.126   233.1 3185.22   241.9 3184.52   266.6 3186.01   284.9 3189.48
   337.7 3190.51   379.8 3189.69   457.8 3192.16   555.6 3196.81   571.7 3200.16
   620.7 3200.45   645.9  3202.6   676.4    3200   693.6 3200.12   698.6 3201.04
     715 3210.87   736.5 3219.28   766.5 3220.56   783.6 3224.27806.2728  3226.5
#Mann= 6 ,-1,0
       0     .12       0      70     .06       0  167.19    .045       0
  210.71      .1       0  702.81     .06       0  802.81      .1       0
Bank Sta=167.19,210.71
XS Rating Curve= 0 ,0
Exp/Cntr(USF)=0,0
Exp/Cntr=0.3,0.1

Type RM Length L Ch R = 1 ,53448   ,251.2,234.2,215.7
BEGIN DESCRIPTION:
structure xs 4
END DESCRIPTION:
XS GIS Cut Line= 4
2192033.64305744465036.0758657982192110.51695217464949.418020829
2192213.94728326464788.6816954832192499.07954736464360.983299345
#Sta/Elev= 30
       0  3226.4    57.3 3220.45      68 3214.72    77.5 3206.63   116.1 3180.97
   120.9 3179.84   143.3 3179.82  150.073176.774   155.9  3175.2   187.5 3174.81
  197.943176.775   201.7 3179.01   207.6 3179.61   281.5 3181.18   296.9 3185.45
   330.4 3188.09   417.8 3191.56   431.4 3190.39   475.5 3194.22   537.1 3194.96
   609.2 3201.71   628.3 3204.59   642.8 3208.67   664.3 3211.21     691 3212.09
   719.8 3210.29   724.6 3211.46     739 3220.45   749.5 3224.93821.0093 3230.19
#Mann= 7 ,-1,0
       0      .1       0      70     .06       0  150.07    .045       0
  197.94     .06       0  235.84      .1       0  566.98     .06       0
  776.98      .1       0
#XS Ineff= 2 , 0
                          259.91         3184.53
Permanent Ineff=
       F       F
Bank Sta=150.07,197.94
XS Rating Curve= 0 ,0
Exp/Cntr(USF)=0,0
Exp/Cntr=0.5,0.3

Type RM Length L Ch R = 1 ,53214   ,71.3,66.5,63.3
BEGIN DESCRIPTION:
structure xs 3
END DESCRIPTION:
XS GIS Cut Line= 5
2192192.98167561465235.9479920982192355.11570813465078.007081106
2192360.70653684464871.1464189212192388.66068038464549.673768229
2192506.06808324464367.971835229
#Sta/Elev= 30
       0 3194.22    21.2 3193.22      38 3186.66    54.7 3184.09      67 3179.27
    77.8 3177.45   164.5 3177.27   179.6 3175.61   263.2 3177.15   279.2    3179
  294.993174.482   327.2 3173.17   338.33174.481   359.2 3182.35   451.3 3184.89
   515.6 3189.65   587.8 3190.95   620.7 3196.81   699.9 3197.79   736.4 3201.95
     756 3202.14   779.1 3207.64   802.3 3210.03   842.3 3210.53   857.2 3206.78
   870.9 3206.31   885.1 3208.82   895.1 3215.03     909 3220.59972.3018 3230.62
#Mann= 5 ,-1,0
       0     .06       0  294.99    .045       0   338.3      .1       0
  563.28     .06       0  905.97      .1       0
#XS Ineff= 3 ,-1
   15.42  160.79 3180.92   168.5  274.23 3174.45     358972.3018 3174.53
Permanent Ineff=
       F       F       F
Bank Sta=294.99,338.3
XS Rating Curve= 0 ,0
Exp/Cntr(USF)=0,0
Exp/Cntr=0.5,0.3