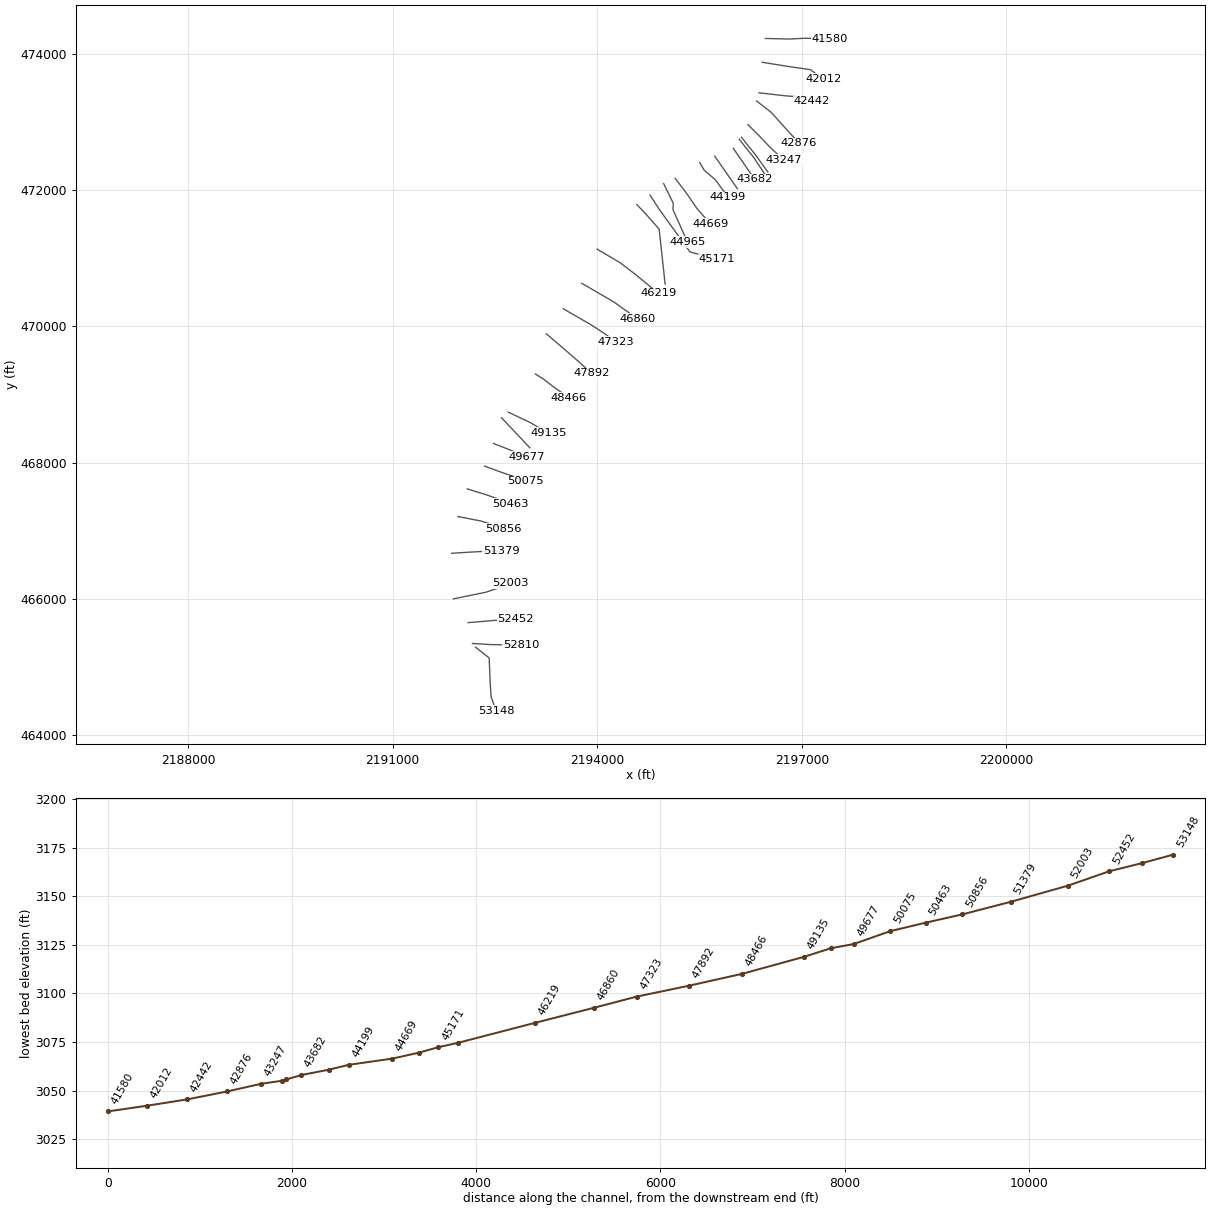
HEC-RAS study WILLIAMSRV.prj: WILLIAMSRV

--- WILLIAMSRV.g01 (geometry) --- (continued)

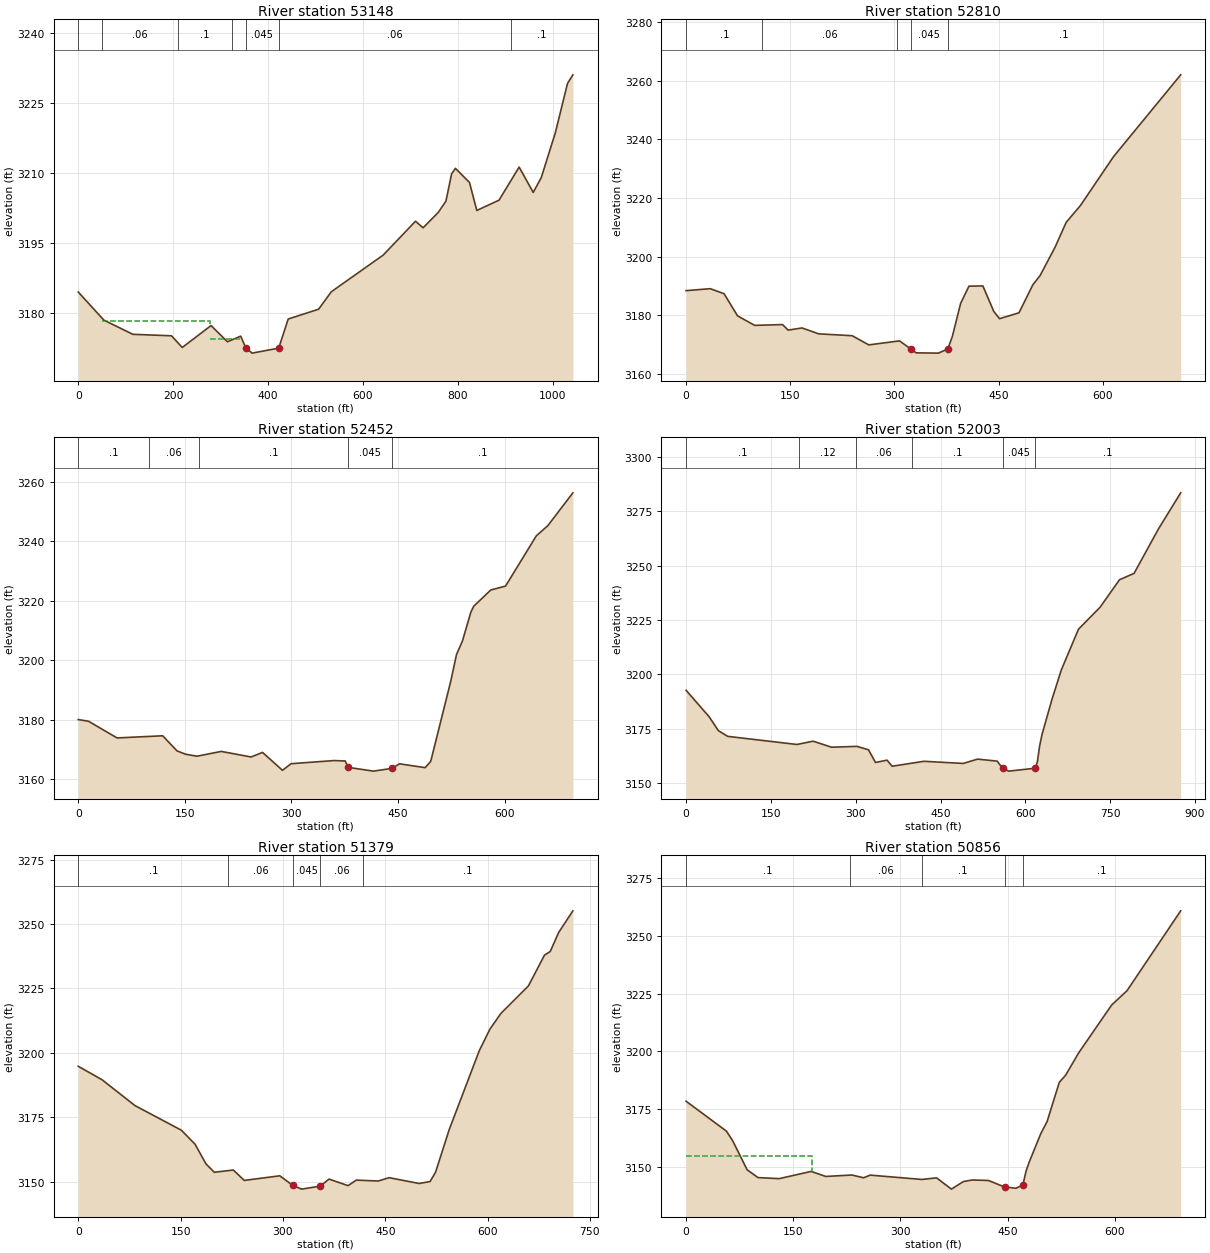
Type RM Length L Ch R = 1 ,53148   ,286.9,338.1,407.8
BEGIN DESCRIPTION:
structure xs 2
END DESCRIPTION:
XS GIS Cut Line= 6
  2192213.713987 465294.418397272192413.17336637465138.007951454
2192416.61482392465076.6093739292192429.19418851464767.716087829
 2192441.7735531464570.6393758832192515.85203348464362.381006522
#Sta/Elev= 30
       0 3184.46      54 3178.44     115 3175.41   196.5 3175.09   219.2 3172.59
   279.9 3177.28   314.4 3173.81   342.4 3175.01353.0574 3172.53   366.4 3171.38
422.5374 3172.45   442.5 3178.68   506.6 3180.78   533.3 3184.51   642.7 3192.36
   710.8 3199.61   726.9 3198.21   758.9 3201.51     775 3203.92     787 3209.76
     795 3210.93   824.6 3207.92   840.1 3201.92   886.8 3204.11   929.3  3211.2
     959 3205.78     976 3208.97  1005.7 3218.58  1031.2 3229.09  1042.6 3230.95
#Mann= 7 ,-1,0
       0      .1       0      50     .06       0     210      .1       0
  324.97     .06       0353.0574    .045       0422.5374     .06       0
  911.59      .1       0
#XS Ineff= 3 ,-1
   50.22     278 3178.27     278     345 3174.45     4301025.878 3174.53
Permanent Ineff=
       F       F       F
Bank Sta=353.0574,422.5374
XS Rating Curve= 0 ,0
Exp/Cntr(USF)=0,0
Exp/Cntr=0.5,0.3

Type RM Length L Ch R = 1 ,52810   ,354.7,358.1,362.9
XS GIS Cut Line= 4
 2192169.5312552465349.0069726322192452.17870653465331.923884914
2192579.52536043465330.3708769392192880.80890745465321.052829093
#Sta/Elev= 30
       0 3188.37    34.7 3189.04    54.7 3187.33    74.1 3179.76    98.8 3176.51
   138.9 3176.78   146.9 3174.89   166.9 3175.63     191 3173.61   239.1 3172.98
   263.1 3169.84   307.2 3171.22  323.483168.458   331.2 3167.12   363.2 3167.03
  376.74 3168.46   383.2 3172.64   395.2 3184.02   407.2  3189.9   427.2 3189.98
     443 3181.25   451.2 3178.79   479.2  3180.8   499.2 3190.39   509.4 3193.45
   531.2 3203.23   547.2 3211.73   567.6 3217.43   615.3 3234.15 711.947 3262.09
#Mann= 5 ,-1,0
       0      .1       0     110     .06       0  303.16      .1       0
  323.48    .045       0  376.74      .1       0
Bank Sta=323.48,376.74
XS Rating Curve= 0 ,0
Exp/Cntr(USF)=0,0
Exp/Cntr=0.3,0.1

Type RM Length L Ch R = 1 ,52452   ,440.4,448.7,458.7
XS GIS Cut Line= 4
2192105.79662219465654.619816388 2192446.6488525465683.024168914
2192628.91011454465699.5933745542192799.33622969465713.795550817
#Sta/Elev= 30
       0 3180.13    14.4 3179.57    54.6 3173.96   118.8 3174.68   138.9 3169.62
   150.9  3168.5     167 3167.82   201.2 3169.43   243.2 3167.56   259.3  3169.1
   287.4 3163.08   299.4  3165.3   360.1 3166.36   375.7 3166.22   379.7 3164.08
   415.4 3162.81  441.933163.745     452 3165.27   488.2 3163.98     496 3166.08
   524.3 3193.13   532.3 3201.99   540.7 3206.58   552.4 3216.15   556.4 3218.17
   580.5 3223.65   601.3 3224.97   644.7 3241.88   660.8 3245.27696.0634  3256.3
#Mann= 5 ,-1,0
       0      .1       0     100     .06       0     170      .1       0
   379.7    .045       0  441.93      .1       0
Bank Sta=379.7,441.93
XS Rating Curve= 0 ,0
Exp/Cntr(USF)=0,0
Exp/Cntr=0.3,0.1

Type RM Length L Ch R = 1 ,52003   ,629.7,623.5,615.4
XS GIS Cut Line= 4
2191888.08517429466003.4887140082192365.38739438466100.897330352
2192527.73508828 466156.095546282192729.04622873466234.022439356
#Sta/Elev= 30
       0 3192.61    40.9  3180.4    57.2 3174.01    73.6 3171.41     196 3167.67
   224.6 3169.19   257.3 3166.41   302.2  3166.8   322.6 3165.22   334.9 3159.39
   355.3 3160.46   364.3 3157.66   420.6 3159.93   490.1 3158.95   515.4 3160.94
   550.1    3160  559.463156.746   570.4 3155.41  617.453156.745   621.1 3159.66
   625.1 3166.99   629.5 3172.45   647.2 3188.66   663.4 3201.94   693.8 3220.71
     732 3230.82   766.3 3243.45   792.1  3246.4   834.9 3266.71874.4828 3283.45
#Mann= 6 ,-1,0
       0      .1       0     200     .12       0     300     .06       0
     400      .1       0  559.46    .045       0  617.45      .1       0
Bank Sta=559.46,617.45
XS Rating Curve= 0 ,0
Exp/Cntr(USF)=0,0
Exp/Cntr=0.3,0.1

Type RM Length L Ch R = 1 ,51379   ,533,523.4,507.6
XS GIS Cut Line= 4
2191865.35649714466672.3612129052192121.86585351466688.595982296
2192423.83256418466704.8307516862192589.42721197466704.830751686
#Sta/Elev= 30
       0 3194.76    34.9 3189.53      83 3179.52   151.1 3169.95   171.2 3164.52
   187.2 3156.88   199.4 3153.62   227.3  3154.5   243.3 3150.46   295.4 3152.25
  314.283148.557   327.4 3147.08   354.8 3148.25   367.5 3150.98   395.5 3148.43
   407.5 3150.58   439.6 3150.22   455.6 3151.53   499.7 3149.27   515.7 3150.03
   523.7 3153.63   543.7 3170.15   587.8 3200.81   603.4 3209.18   619.4 3215.25
   659.8 3225.95   683.4  3237.9   691.8  3239.3   704.1 3246.67725.0201  3255.1
#Mann= 5 ,-1,0
       0      .1       0     220     .06       0  314.28    .045       0
   354.8     .06       0  417.02      .1       0
Bank Sta=314.28,354.8
XS Rating Curve= 0 ,0
Exp/Cntr(USF)=0,0
Exp/Cntr=0.3,0.1

Type RM Length L Ch R = 1 ,50856   ,393.1,393,391
XS GIS Cut Line= 4
2191956.27120573467211.3555566762192290.70745518467146.416479114
2192443.31428745 467100.959124822192621.89675075  467029.5261395
#Sta/Elev= 30
       0 3178.57    56.4 3165.68    65.1 3161.61    85.5    3149   100.7 3145.62
   130.3 3145.17   175.1 3148.29   195.5 3146.12   232.2 3146.73   248.5 3145.54
   257.7 3146.69     330 3144.82   350.6 3145.51   371.4 3140.65   388.1 3143.91
   400.5 3144.59   423.3 3144.38   445.8 3141.57   461.8 3141.03  471.463142.475
   475.8 3148.33   479.9 3152.03   496.6 3164.68   505.2 3169.71   522.4 3186.71
   531.2 3189.76   549.6 3199.46   595.6 3220.03   617.2 3226.23692.2551 3260.66
#Mann= 5 ,-1,0
       0      .1       0     230     .06       0     330      .1       0
   445.8    .045       0  471.46      .1       0
#XS Ineff= 2 , 0
          176.54 3154.85
Permanent Ineff=
       F       F
Bank Sta=445.8,471.46
XS Rating Curve= 0 ,0
Exp/Cntr(USF)=0,0
Exp/Cntr=0.3,0.1

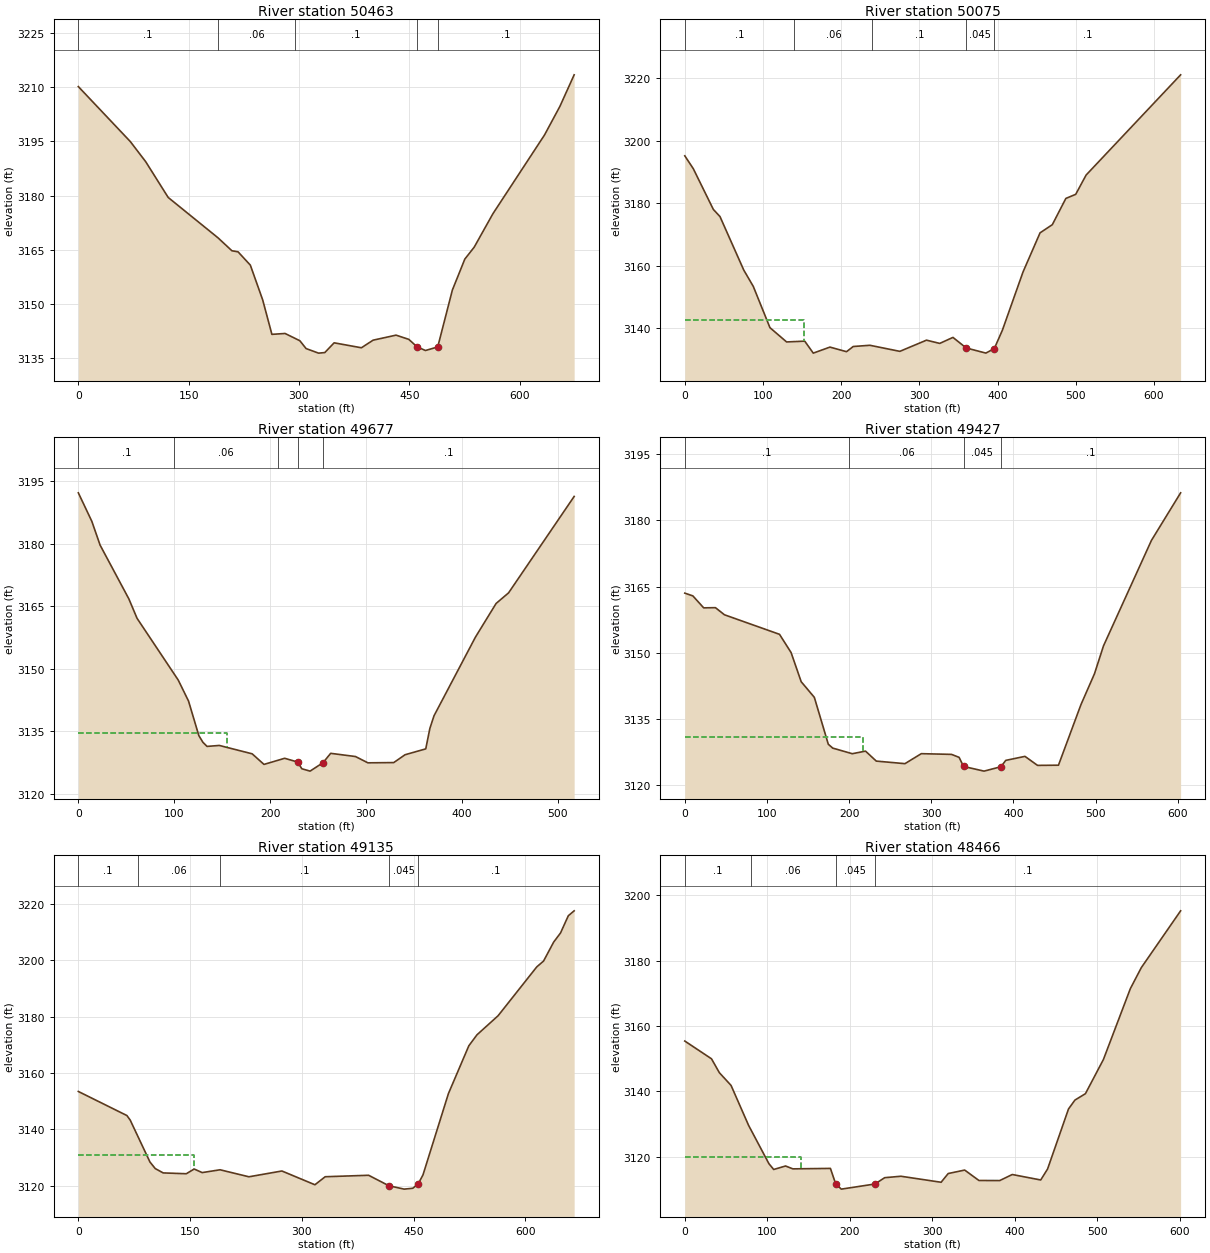
Type RM Length L Ch R = 1 ,50463   ,386.7,387.9,388.1
XS GIS Cut Line= 4
2192092.64326861467617.2247914442192355.64653274467536.050944491
2192618.64979687467445.1362359032192729.04622873467396.431927731
#Sta/Elev= 30
       0 3210.12    70.7 3194.92    91.6 3189.36   122.2 3179.47     190  3168.3
   208.8 3164.74   217.2 3164.44   233.9 3160.76   250.7 3151.14   263.2 3141.63
   281.1 3141.87   301.2 3139.87   309.7  3137.7   326.6 3136.44   335.1 3136.59
   347.8 3139.29   384.9 3137.92   400.8 3140.02     432 3141.41   449.3 3140.25
   460.3 3138.23     472 3137.16  488.693138.157   508.6 3153.88   525.5 3162.43
   538.2 3165.71   563.7 3174.97   633.9 3196.75   654.8 3204.65674.1815 3213.37
#Mann= 5 ,-1,0
       0      .1       0     190     .06       0  295.25      .1       0
   460.3    .045       0  488.69      .1       0
Bank Sta=460.3,488.69
XS Rating Curve= 0 ,0
Exp/Cntr(USF)=0,0
Exp/Cntr=0.3,0.1

Type RM Length L Ch R = 1 ,50075   ,396.5,398.3,398
XS GIS Cut Line= 4
2192345.90567111467951.6610408932192647.87238177467841.264609036
2192764.76272139467802.3011624982192940.09823081467730.868177179
#Sta/Elev= 30
       0 3195.21    10.9 3191.07    36.5 3178.05      45 3175.76    75.4 3158.64
    87.6  3153.4   108.9  3140.2   130.2 3135.63   153.4 3135.88   164.3 3132.05
   185.6 3133.98   206.8 3132.51   215.4 3134.17   236.7 3134.56     275 3132.62
   309.1  3136.2     326 3135.16   342.9 3137.08   359.8 3133.72   359.8 3133.71
     385 3132.06  395.813133.508   406.2 3139.44   432.5 3158.01   454.3 3170.55
     470 3173.17   487.3 3181.57   499.9 3182.88   513.2 3189.05634.0556 3221.13
#Mann= 5 ,-1,0
       0      .1       0     140     .06       0     240      .1       0
   359.8    .045       0  395.81      .1       0
#XS Ineff= 2 , 0
          152.64 3142.55
Permanent Ineff=
       F       F
Bank Sta=359.8,395.81
XS Rating Curve= 0 ,0
Exp/Cntr(USF)=0,0
Exp/Cntr=0.3,0.1

Type RM Length L Ch R = 1 ,49677   ,262,249.5,238.4
XS GIS Cut Line= 4
2192479.03078011468282.8503364632192654.36628953468214.664305022
2192784.24444466468162.7130429722192959.57995408468091.280057653
#Sta/Elev= 30
       0 3192.17    14.1 3185.33    22.7 3179.63    52.7 3166.74    61.3 3162.06
   104.2 3147.27     115 3142.21   125.7 3133.95     130 3132.32   134.3 3131.34
   147.1 3131.57   181.4 3129.56   193.7 3127.02   215.3 3128.49   228.8 3127.59
   233.2 3125.98   241.8 3125.41   255.3 3127.43   263.3 3129.68   289.2 3128.91
   302.1  3127.4   329.1 3127.46   340.9 3129.34   362.5 3130.75   366.8 3135.66
   371.1 3138.68   414.3 3157.54   435.9 3165.63   448.9 3168.17517.3387  3191.3
#Mann= 5 ,-1,0
       0      .1       0     100     .06       0  208.13      .1       0
   228.8    .045       0   255.3      .1       0
#XS Ineff= 2 , 0
             155 3134.67
Permanent Ineff=
       F       F
Bank Sta=228.8,255.3
XS Rating Curve= 0 ,0
Exp/Cntr(USF)=0,0
Exp/Cntr=0.3,0.1

Type RM Length L Ch R = 1 ,49427   ,284.4,292.6,299.5
BEGIN DESCRIPTION:
new xs added per checkras comment
END DESCRIPTION:
XS GIS Cut Line= 2
2192596.41878595468660.3434588392193010.03411491468220.800004783
#Sta/Elev= 30
       0  3163.5     9.8 3162.88      23 3160.17    37.3 3160.21    48.3  3158.6
   115.3 3154.18   129.4 3150.05   141.7 3143.45   157.7 3139.92   174.7  3129.3
   180.1 3128.43   203.9 3127.16     220 3127.75   233.1 3125.49     268 3124.91
   287.9 3127.17   324.7 3127.01   333.9 3126.34   339.4 3124.28   364.3 3123.22
   384.9 3124.22   390.7 3125.65   414.1 3126.56   429.4 3124.52   454.9 3124.56
   482.2 3138.24   498.7 3145.24   509.7 3151.56     568 3175.41   603.6  3186.2
#Mann= 4 ,-1,0
       0      .1       0     200     .06       0   339.4    .045       0
   384.9      .1       0
#XS Ineff= 2 , 0
          216.33 3130.96
Permanent Ineff=
       F       F
Bank Sta=339.4,384.9
XS Rating Curve= 0 ,0
Exp/Cntr(USF)=0,0
Exp/Cntr=0.3,0.1

Type RM Length L Ch R = 1 ,49135   ,672.4,669.1,662.1
XS GIS Cut Line= 4
2192693.32973607 468743.917787162193021.27207776468588.064001009
2193141.40937125 468516.631015692193284.27534189468438.704122614
#Sta/Elev= 30
       0 3153.48    65.2 3144.93    69.6 3143.33    96.2 3128.41   103.3 3126.09
   113.9 3124.56   144.9 3124.26   155.5 3125.94   166.3 3124.67   190.3 3125.67
     229 3123.18   273.3 3125.24   317.6 3120.35   331.4  3123.2   389.7 3123.72
   416.9    3120   437.4  3118.8     449 3119.11  456.323120.679   462.7 3123.88
   496.8 3152.71   524.2 3169.69   535.1 3173.58   563.5 3180.37   615.4 3197.71
   624.5 3199.78   638.1 3206.52   647.3 3209.76   657.8 3215.89665.5999 3217.62
#Mann= 5 ,-1,0
       0      .1       0      80     .06       0     190      .1       0
   416.9    .045       0  456.32      .1       0
#XS Ineff= 2 , 0
          155.73 3130.91
Permanent Ineff=
       F       F
Bank Sta=416.9,456.32
XS Rating Curve= 0 ,0
Exp/Cntr(USF)=0,0
Exp/Cntr=0.3,0.1

Type RM Length L Ch R = 1 ,48466   ,570.4,573.3,566.4
XS GIS Cut Line= 4
2193092.70506308  469302.39385422193206.34844881469230.960868881
2193358.95528109469114.0705292682193582.99509868468954.969789239
#Sta/Elev= 30
       0 3155.41    32.4 3149.97    41.9 3145.73    56.1 3141.83    77.4 3129.59
     102 3117.89   107.8 3116.11   122.2 3117.18     131  3116.3   176.6 3116.44
  183.023111.669   189.8  3110.1   230.63111.669   242.4  3113.6   262.1 3114.04
   310.8  3112.2   319.4 3114.87   339.4 3115.93   356.7 3112.74   381.9 3112.72
   397.1 3114.57   431.6  3112.9   439.9 3116.25   465.3 3134.63   473.1 3137.35
   485.8  3139.3   507.6 3149.75   540.3 3171.45   553.6 3177.88 601.244 3195.25
#Mann= 4 ,-1,0
       0      .1       0      80     .06       0  183.02    .045       0
   230.6      .1       0
#XS Ineff= 2 , 0
          141.08 3119.85
Permanent Ineff=
       F       F
Bank Sta=183.02,230.6
XS Rating Curve= 0 ,0
Exp/Cntr(USF)=0,0
Exp/Cntr=0.3,0.1

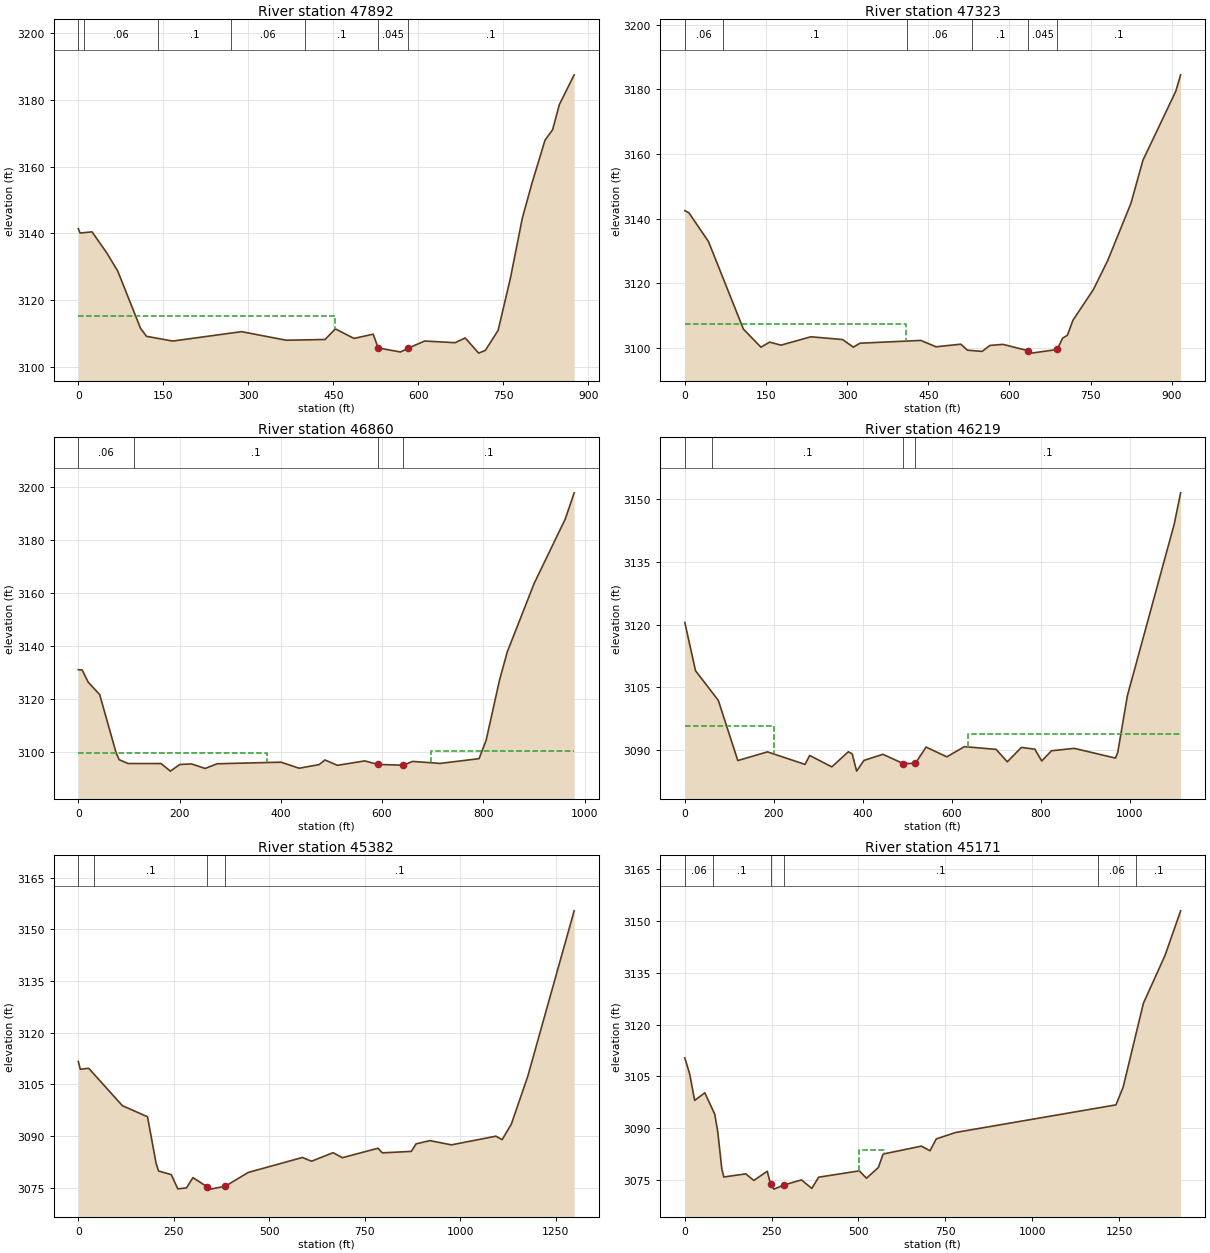
Type RM Length L Ch R = 1 ,47892   ,564.1,569.2,573.8
XS GIS Cut Line= 4
2193253.81009563469892.7782581172193594.53982358469600.151550581
2193726.82312973469483.9025845732193911.21804132469315.542013114
#Sta/Elev= 30
       0 3141.35     3.1 3140.05    24.2  3140.4    50.6 3133.98    69.5 3128.66
   109.9 3111.41   120.5 3109.06   166.6 3107.65   287.9 3110.47   366.9  3107.9
   435.3 3108.12   453.6  3111.3   486.4 3108.44   520.3 3109.72  529.133105.582
   568.6 3104.37  582.09 3105.51   611.1 3107.66     665 3107.16   682.7 3108.58
   706.4 3104.03   718.3 3104.86   740.8 3110.87   762.5 3126.54   783.5 3144.53
   800.8 3155.16   823.5  3167.9   836.9 3171.02   848.8 3178.57 874.938  3187.5
#Mann= 7 ,-1,0
       0      .1       0      10     .06       0     140      .1       0
     270     .06       0     400      .1       0  529.13    .045       0
  582.09      .1       0
#XS Ineff= 2 , 0
          453.74 3115.15
Permanent Ineff=
       F       F
Bank Sta=529.13,582.09
XS Rating Curve= 0 ,0
Exp/Cntr(USF)=0,0
Exp/Cntr=0.3,0.1

Type RM Length L Ch R = 1 ,47323   ,464.8,463.4,462.6
XS GIS Cut Line= 4
2193498.33378274470261.5680813132193915.22662636470021.052979229
 2194127.6816332469880.7525030132194271.99069445469772.520707075
#Sta/Elev= 30
       0 3142.51     7.5 3141.86    43.7 3132.97   108.3 3105.85   140.7 3100.25
   156.8 3101.82   177.6 3100.88     233 3103.47   291.5 3102.62   311.5 3100.26
   323.8 3101.48   436.2 3102.34   464.3 3100.37   510.1 3101.18   522.3 3099.32
   549.5 3098.95   563.9 3100.79   587.9 3101.12   634.9 3099.14   640.6 3098.41
  688.243099.537   698.1 3103.03   707.1 3103.96   717.3 3108.58   755.2 3118.12
   781.7 3127.13   824.5 3144.78   846.5 3158.04   907.4 3179.49916.2841 3184.54
#Mann= 6 ,-1,0
       0     .06       0      70      .1       0     410     .06       0
   531.3      .1       0   634.9    .045       0  688.24      .1       0
#XS Ineff= 2 , 0
          409.01 3107.44
Permanent Ineff=
       F       F
Bank Sta=634.9,688.24
XS Rating Curve= 0 ,0
Exp/Cntr(USF)=0,0
Exp/Cntr=0.3,0.1

Type RM Length L Ch R = 1 ,46860   ,626,640.5,639.9
XS GIS Cut Line= 4
2193770.91756511470634.3664895452194239.92201417470361.782707182
2194408.28258563 470241.525156142194596.68608226470109.241849993
#Sta/Elev= 30
       0 3130.95     7.6 3130.85    19.3  3126.3    42.2 3121.56    74.9 3099.41
    80.8 3096.98    98.3 3095.54   163.4 3095.53   181.9 3092.67   200.4 3095.18
   223.5 3095.39   250.5 3093.68   274.4 3095.45   400.4 3096.05   436.3 3093.77
   475.8 3095.14   487.2 3096.88   511.8 3094.86     566 3096.53   591.7  3095.2
  642.023094.904   660.5 3096.34   714.8 3095.58   791.7 3097.38   805.7 3104.33
   832.3 3127.17   847.4 3137.66   900.7 3163.59     962 3187.84979.5687 3197.73
#Mann= 4 ,-1,0
       0     .06       0     110      .1       0   591.7    .045       0
  642.02      .1       0
#XS Ineff= 2 , 0
          372.41 3099.36   696.9          3100.2
Permanent Ineff=
       F       F
Bank Sta=591.7,642.02
XS Rating Curve= 0 ,0
Exp/Cntr(USF)=0,0
Exp/Cntr=0.3,0.1

Type RM Length L Ch R = 1 ,46219   ,837.9,837.2,823.3
XS GIS Cut Line= 4
2193995.39832705471135.4396188872194336.12805501 470935.01036715
2194560.60881695470762.6412106562194897.32995987470486.048843259
#Sta/Elev= 30
       0 3120.53    24.1 3108.97    75.3 3101.87   119.1 3087.46   185.9 3089.54
   270.1 3086.54   280.6 3088.68   330.4 3085.95   367.5 3089.57   376.2 3089.05
   386.1 3084.93   402.4 3087.49   445.1 3088.96   490.8 3086.74  518.243086.797
   542.1 3090.69   588.8 3088.35   628.2 3090.79   699.5 3090.14   724.7 3087.16
   756.3 3090.61   786.5 3090.18     802 3087.36     824 3089.81   875.2 3090.38
   967.7 3088.05   972.8 3089.41   994.5 3102.99  1099.7 3144.05 1114.09 3151.55
#Mann= 4 ,-1,0
       0     .06       0      60      .1       0   490.8    .045       0
  518.24      .1       0
#XS Ineff= 2 , 0
          200.79 3095.78  635.68          3093.7
Permanent Ineff=
       F       F
Bank Sta=490.8,518.24
XS Rating Curve= 0 ,0
Exp/Cntr(USF)=0,0
Exp/Cntr=0.3,0.1

Type RM Length L Ch R = 1 ,45382   ,212.1,210.9,211.1
XS GIS Cut Line= 4
2194579.68004139471788.8800343872194724.24821478471636.448600139
2194907.24690072471428.3896555832194994.40681866 470621.55629267
#Sta/Elev= 30
       0 3111.66     5.1  3109.4    27.2 3109.68   115.4 3098.84   181.2 3095.63
   203.6 3082.19   210.1  3079.9   243.5 3078.84   260.5 3074.72   283.2 3074.99
   300.2 3077.97   337.1 3075.35   345.6 3074.64   384.9 3075.47   444.8 3079.47
     587 3083.82   610.8 3082.73   667.4 3085.21   691.6 3083.75     785  3086.5
   796.2 3085.16   872.2 3085.58   884.7 3087.77   920.9  3088.7   977.2 3087.48
  1093.7 3089.99    1110 3088.98  1134.1 3093.48  1177.2 3107.35  1298.7 3155.34
#Mann= 4 ,-1,0
       0     .06       0      40      .1       0   337.1    .045       0
   384.9      .1       0
Bank Sta=337.1,384.9
XS Rating Curve= 0 ,0
Exp/Cntr(USF)=0,0
Exp/Cntr=0.3,0.1

Type RM Length L Ch R = 1 ,45171   ,226.9,206.3,187.9
XS GIS Cut Line= 4
2194773.06382379471929.139455767 2194901.3385449471728.710204029
2195358.31723887 471095.353768542195751.15857227470983.113387567
#Sta/Elev= 30
       0 3110.37    14.2 3105.68    28.4 3098.07    57.7 3100.27    86.2 3094.09
    94.9 3089.03   106.5 3078.35   112.3 3075.94   175.7 3076.84   198.7 3074.94
   237.4 3077.59   247.2 3073.77   256.5 3072.43   285.5 3073.62     336  3075.1
   365.7 3072.63   385.4 3075.88   502.6 3077.71   523.1 3075.58   557.3 3078.69
     571 3082.57   681.3 3084.86     706 3083.51   723.9 3086.94     780 3088.81
  1241.4 3096.78  1262.2 3101.95  1320.4 3126.16  1382.8 3140.01 1427.53 3152.86
#Mann= 6 ,-1,0
       0     .06       0      80      .1       0   247.2    .045       0
   285.5      .1       0 1188.97     .06       0 1298.97      .1       0
#XS Ineff= 1 ,-1
   502.2  574.45 3083.79
Permanent Ineff=
       F
Bank Sta=247.2,285.5
XS Rating Curve= 0 ,0
Exp/Cntr(USF)=0,0
Exp/Cntr=0.3,0.1

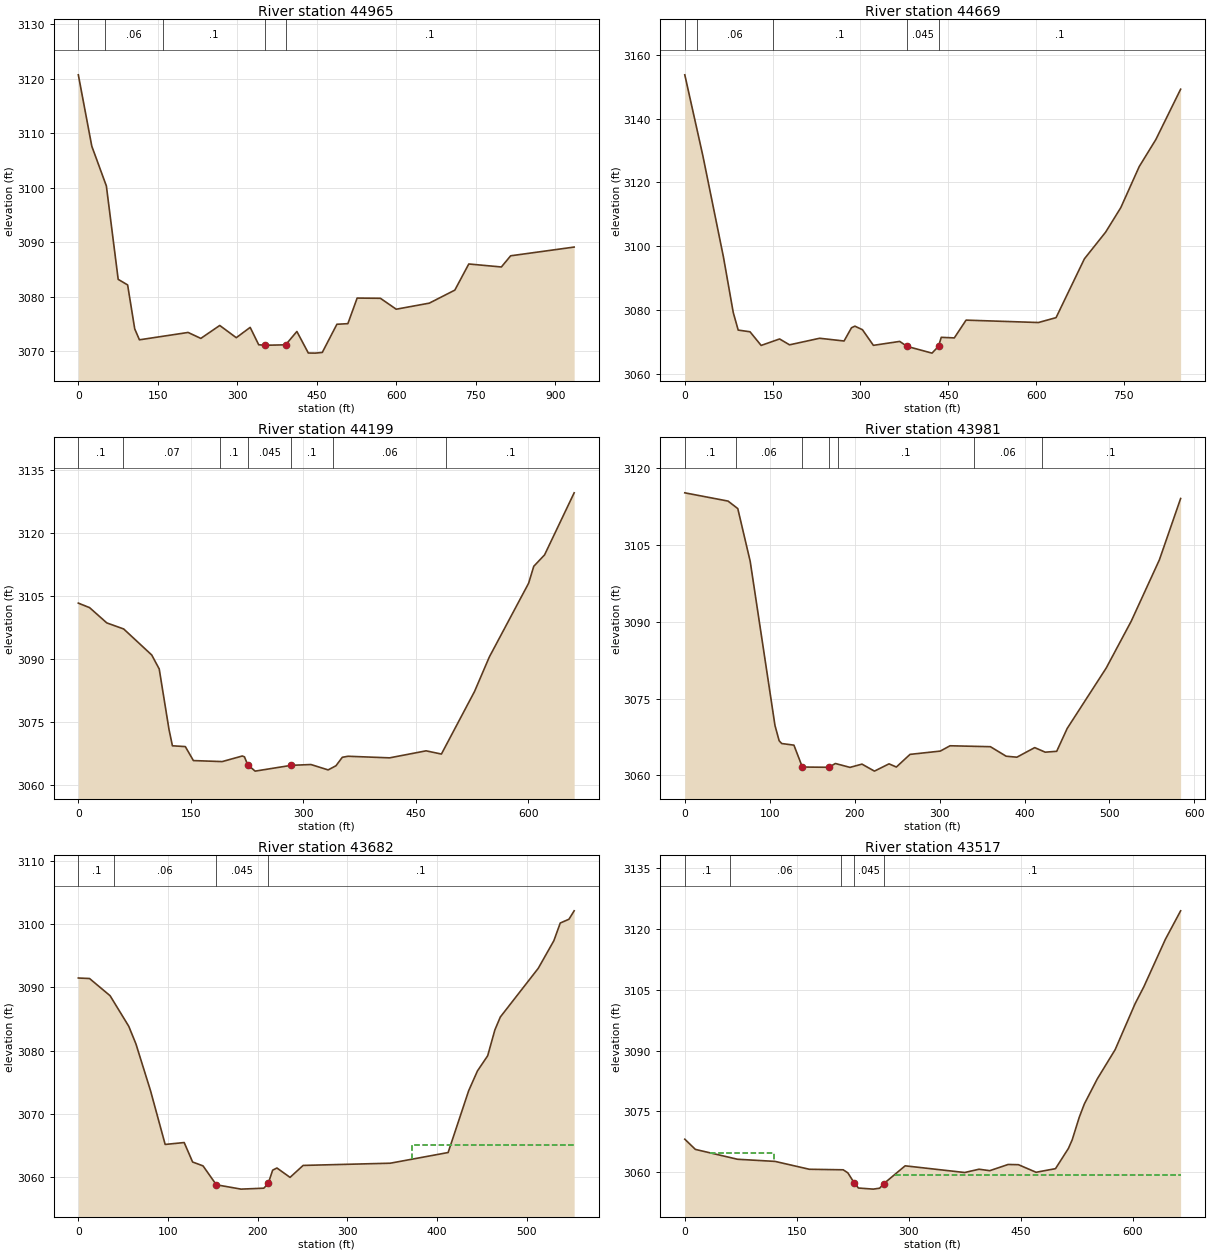
Type RM Length L Ch R = 1 ,44965   ,273.2,296.3,315.4
BEGIN DESCRIPTION:
new xs added per checkras comment
END DESCRIPTION:
XS GIS Cut Line= 4
2194973.01206124472096.6867892922195114.13514213471808.884600695
2195109.69032069471713.3209396172195323.04175007 471239.94745567
#Sta/Elev= 30
       0 3120.68    25.4  3107.6    52.9 3100.31    75.2 3083.19      93 3082.17
   106.4 3074.11   115.3 3072.11   207.1 3073.46   231.1 3072.37   266.8 3074.74
     298  3072.5   324.2 3074.39   340.3  3071.2   352.7 3071.11   391.13071.194
   412.3 3073.64   433.9 3069.69   447.1 3069.67   460.2 3069.79   487.8 3074.96
   508.5 3075.07     526 3079.76   569.9 3079.72   599.7 3077.72   662.1 3078.83
   710.3 3081.22   736.6 3086.01   798.1 3085.46   815.6 3087.51   935.4 3089.11
#Mann= 5 ,-1,0
       0      .1       0      50     .06       0     160      .1       0
   352.7    .045       0   391.1      .1       0
Bank Sta=352.7,391.1
XS Rating Curve= 0 ,0
Exp/Cntr(USF)=0,0
Exp/Cntr=0.3,0.1

Type RM Length L Ch R = 1 ,44669   ,457.1,469.2,476.2
XS GIS Cut Line= 4
2195141.85364699472173.6631428862195298.18846334471969.225306114
 2195454.5232797471740.7359591342195658.96111647471504.229442084
#Sta/Elev= 30
       0 3153.74    30.8 3128.43    66.1 3096.56    82.8 3079.22    91.2 3073.75
   111.4 3073.22   130.4 3068.94   161.9 3070.97   178.9 3069.13   230.3 3071.19
     272 3070.33   284.7 3074.48   290.5 3074.98   303.4 3073.87   322.1 3068.97
   367.1  3070.2  379.483068.654   422.2 3066.53  433.313068.651     438 3071.48
   460.3  3071.3   480.4 3076.87     604 3076.12   634.1 3077.65   682.5 3096.08
   718.7 3104.43   744.7 3112.14   776.1 3124.98   804.5 3133.46846.8343 3149.23
#Mann= 5 ,-1,0
       0      .1       0      20     .06       0     150      .1       0
  379.48    .045       0  433.31      .1       0
Bank Sta=379.48,433.31
XS Rating Curve= 0 ,0
Exp/Cntr(USF)=0,0
Exp/Cntr=0.3,0.1

Type RM Length L Ch R = 1 ,44199   ,226.6,218.8,213.1
XS GIS Cut Line= 4
2195502.62630012472406.1610749012195566.76366067472293.920693928
2195735.12423213472149.6116326772195915.51055869471897.070775489
#Sta/Elev= 30
       0 3103.35      15 3102.28      38 3098.64    60.5  3097.2    97.9 3091.01
   107.9 3087.68   120.9 3073.34   125.5  3069.4   142.7 3069.21   153.5 3065.88
   191.9 3065.64   218.7 3066.97   221.6 3066.77  225.843064.905   235.8 3063.37
     284 3064.75   310.3 3064.94   333.2 3063.66   343.6 3064.64   352.1 3066.66
   359.7 3066.91   415.2 3066.53   463.9  3068.2   484.3 3067.43   528.5 3082.33
   548.2 3090.53   600.6 3108.08   607.5 3112.12   621.9 3114.83661.3653  3129.6
#Mann= 7 ,-1,0
       0      .1       0      60     .07       0  189.27      .1       0
  225.84    .045       0     284      .1       0  339.27     .06       0
  491.02      .1       0
Bank Sta=225.84,284
XS Rating Curve= 0 ,0
Exp/Cntr(USF)=0,0
Exp/Cntr=0.3,0.1

Type RM Length L Ch R = 1 ,43981   ,299.8,298.4,308.1
XS GIS Cut Line= 2
2195720.43258423472500.2908768172196054.46610721472021.549690449
#Sta/Elev= 30
       0 3115.17    50.9 3113.56    62.4 3112.09      77  3101.8   106.2 3069.74
   111.1 3066.77   114.1 3066.23   128.5 3065.91   138.43061.638   169.6 3061.59
   177.3 3062.33   194.5 3061.57   208.6 3062.21   223.3 3060.84   240.5 3062.26
   249.1 3061.64   265.2 3064.11   300.8 3064.75   312.3 3065.79   359.8 3065.61
   378.4 3063.75     391 3063.56     412 3065.43   424.4 3064.54   437.9 3064.71
   450.2 3069.16   496.2 3080.97   525.7 3090.13   558.8 3102.09   583.8 3114.06
#Mann= 7 ,-1,0
       0      .1       0      60     .06       0   138.4    .045       0
   169.6     .06       0     180      .1       0     340     .06       0
     420      .1       0
Bank Sta=138.4,169.6
XS Rating Curve= 0 ,0
Exp/Cntr(USF)=0,0
Exp/Cntr=0.3,0.1

Type RM Length L Ch R = 1 ,43682   ,162.2,165.1,166.3
BEGIN DESCRIPTION:
structure xs 4
END DESCRIPTION:
XS GIS Cut Line= 2
2195993.21984014 472615.486163122196306.85900387472160.415620364
#Sta/Elev= 30
       0 3091.49    12.5 3091.41    35.4 3088.69    56.2 3083.86    64.2 3081.07
    80.5 3073.65    96.8 3065.16     118 3065.46   127.4 3062.38     139 3061.77
   153.8 3058.78   181.4 3058.09   206.8 3058.24   211.7    3059   216.6 3061.09
   221.4 3061.43     236 3059.95   250.6 3061.84   347.7 3062.19   412.2 3063.88
   435.1 3073.65   444.9 3076.79   456.3 3079.19   464.3 3083.27   470.4 3085.32
   512.7 3093.03   530.1  3097.4   537.2 3100.19   546.9 3100.79   552.7 3102.12
#Mann= 4 ,-1,0
       0      .1       0      40     .06       0   153.8    .045       0
   211.7      .1       0
#XS Ineff= 2 , 0
                          372.28          3065.1
Permanent Ineff=
       F       F
Bank Sta=153.8,211.7
XS Rating Curve= 0 ,0
Exp/Cntr(USF)=0,0
Exp/Cntr=0.5,0.3

Type RM Length L Ch R = 1 ,43517   ,44.8,44.3,45
BEGIN DESCRIPTION:
structure xs 3
END DESCRIPTION:
XS GIS Cut Line= 4
 2196080.5758294472748.3103553052196178.87321213472623.204595465
2196290.57478342472484.694647071 2196471.5313289472212.142813135
#Sta/Elev= 30
       0 3068.13    14.2 3065.61    70.6 3063.18     121 3062.65   166.8 3060.71
   212.2 3060.58   218.4 3059.83   226.9 3057.38   232.6 3056.08   252.5 3055.81
     261 3056.04   266.7 3057.18   295.2 3061.56   374.9 3059.91   394.1 3060.72
   408.5 3060.36   433.1 3061.89   446.9 3061.84   470.6 3059.97   496.6 3060.86
   513.9 3065.86   518.9 3067.95   528.5 3073.59   535.2 3076.81   552.5 3082.99
   576.5 3090.23   603.3  3101.6   614.9 3105.73   643.7 3117.42   664.2 3124.48
#Mann= 5 ,-1,0
       0      .1       0      60     .06       0   209.1      .1       0
   226.9    .045       0   266.7      .1       0
#XS Ineff= 3 ,-1
   33.32     120 3064.72     120     215  3059.4     281   664.2  3059.4
Permanent Ineff=
       F       F       F
Bank Sta=226.9,266.7
XS Rating Curve= 0 ,0
Exp/Cntr(USF)=0,0
Exp/Cntr=0.5,0.3

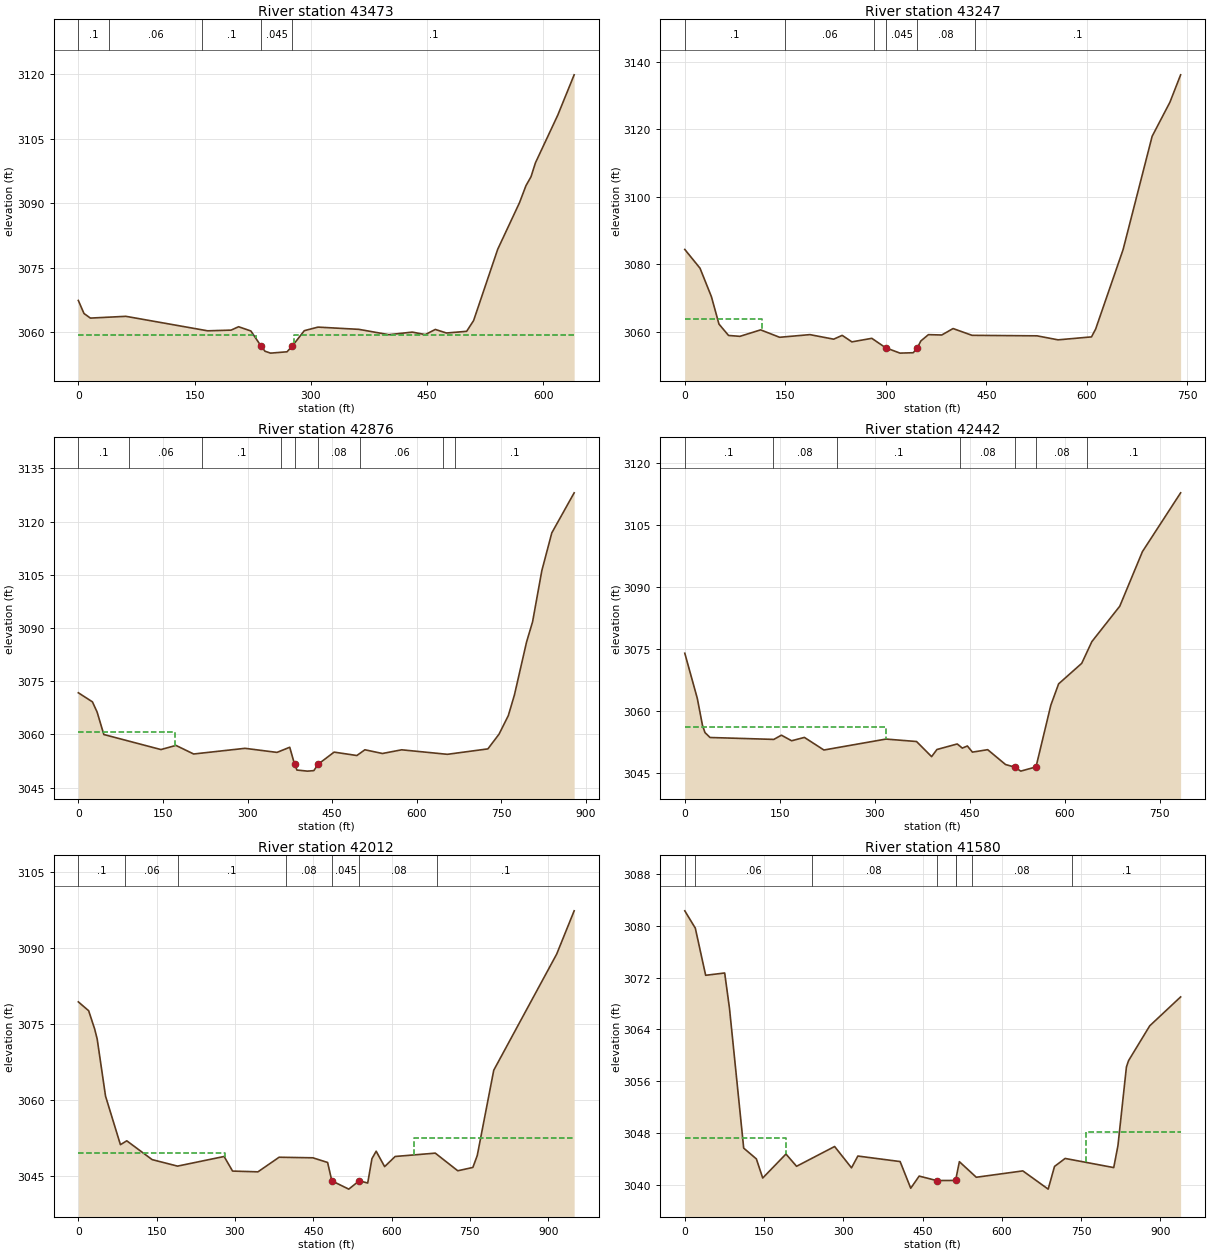
Type RM Length L Ch R = 1 ,43473   ,223.4,225.4,228
BEGIN DESCRIPTION:
structure xs 2
END DESCRIPTION:
XS GIS Cut Line= 4
2196114.08630078472777.3527638392196230.25593492472629.906689743
 2196315.1491291472524.9072127342196500.57373743472267.993598777
#Sta/Elev= 30
       0 3067.41     7.3 3064.38    15.5 3063.31    61.3 3063.72   166.8 3060.35
   197.1 3060.51   206.7  3061.3   222.6 3060.31   235.3 3056.91   240.8  3055.6
     248 3055.16   269.2 3055.47   276.1 3056.83   291.5 3060.38   309.1 3061.21
   361.9 3060.69   400.6 3059.45   430.9 3060.05   447.5 3059.47   460.5 3060.67
   474.9 3059.84   500.9 3060.23   509.9 3062.74     541 3079.32   569.1 3090.15
   577.4  3094.1   583.9 3096.17   589.7 3099.44   618.4 3110.49   639.6 3119.89
#Mann= 5 ,-1,0
       0      .1       0      40     .06       0     160      .1       0
   235.3    .045       0   276.1      .1       0
#XS Ineff= 2 , 0
          228.96 3059.33     278         3059.33
Permanent Ineff=
       F       F
Bank Sta=235.3,276.1
XS Rating Curve= 0 ,0
Exp/Cntr(USF)=0,0
Exp/Cntr=0.5,0.3

Type RM Length L Ch R = 1 ,43247   ,372.1,371.6,371.5
XS GIS Cut Line= 4
2196208.13726623 472963.354394732196372.48925266472799.002408306
2196524.81548398472638.6590069162196733.26190578472442.238340214
#Sta/Elev= 30
       0 3084.37    22.7 3078.81    39.7 3070.38      51 3062.23    65.3 3058.85
    82.3 3058.59   113.2 3060.51   141.5 3058.31   186.7  3059.1   222.2 3057.75
   234.9 3058.88   249.4 3056.95   279.1    3058  299.743055.209   321.2 3053.61
     341 3053.73  347.063055.207   352.3 3057.22   363.6 3059.09   383.5 3058.99
   400.4  3060.9   428.7 3058.89   525.7 3058.74   557.1 3057.55     607 3058.43
   613.2 3060.76   654.1  3084.3   697.5 3117.95     724 3128.04740.0028 3136.18
#Mann= 6 ,-1,0
       0      .1       0     150     .06       0  282.43      .1       0
  299.74    .045       0  347.06     .08       0  432.43      .1       0
#XS Ineff= 2 , 0
          115.42 3063.64
Permanent Ineff=
       F       F
Bank Sta=299.74,347.06
XS Rating Curve= 0 ,0
Exp/Cntr(USF)=0,0
Exp/Cntr=0.3,0.1

Type RM Length L Ch R = 1 ,42876   ,410.2,433.8,451.6
XS GIS Cut Line= 4
2196336.41198734473308.0927077182196548.86699418473143.740721294
2196721.23615068472951.3286396262196957.74266773472690.770612368
#Sta/Elev= 30
       0 3071.74      25 3069.18    33.3  3066.3    45.2 3059.97   146.4 3055.73
     173  3056.9   204.4 3054.48   295.4 3056.08   352.1 3054.93   374.7 3056.38
  383.183051.636   387.5 3049.95   406.3 3049.65   417.4 3049.79  425.313051.637
   453.4 3055.01   493.7 3054.05   507.9 3055.67     539 3054.62   573.1 3055.66
   654.1 3054.39   725.9 3055.92   745.6 3060.05   762.1  3065.3   772.9 3071.09
   794.5 3086.08   805.1 3091.72   821.5 3106.15   839.2 3116.82878.8224 3128.11
#Mann= 9 ,-1,0
       0      .1       0      90     .06       0     220      .1       0
  358.61     .08       0  383.18    .045       0  425.31     .08       0
  498.61     .06       0  646.93     .08       0  666.93      .1       0
#XS Ineff= 2 , 0
          171.81 3060.76
Permanent Ineff=
       F       F
Bank Sta=383.18,425.31
XS Rating Curve= 0 ,0
Exp/Cntr(USF)=0,0
Exp/Cntr=0.3,0.1

Type RM Length L Ch R = 1 ,42442   ,430.9,429.3,425.1
XS GIS Cut Line= 4
2196372.48925265473428.3502587612196765.33058606473384.255823378
2197017.87144325473364.2128982052197138.12899429473304.084122684
#Sta/Elev= 30
       0 3074.04    19.8 3063.11    27.9 3056.64    31.9 3054.87    39.9 3053.69
   140.6 3053.23   152.6 3054.25   168.7  3052.9   188.9 3053.71   219.7 3050.67
   317.7 3053.31     366 3052.72   389.8 3049.07   398.2 3050.79   430.3 3052.13
   438.3 3051.13   446.3 3051.64   454.3 3050.16   478.4 3050.75   506.5 3047.17
   521.5 3046.51   530.6 3045.57   554.7 3046.59   578.1 3061.49   590.4 3066.64
   626.9  3071.6   642.9 3076.84     687  3085.4   722.8 3098.58783.0953 3112.77
#Mann= 7 ,-1,0
       0      .1       0     140     .08       0     240      .1       0
  435.31     .08       0   521.5    .045       0   554.7     .08       0
  635.31      .1       0
#XS Ineff= 2 , 0
          317.75 3056.28
Permanent Ineff=
       F       F
Bank Sta=521.5,554.7
XS Rating Curve= 0 ,0
Exp/Cntr(USF)=0,0
Exp/Cntr=0.3,0.1

Type RM Length L Ch R = 1 ,42012   ,426.6,432.2,437.7
XS GIS Cut Line= 4
2196416.58368804473877.3117826522196789.38209627473817.183007131
2197122.09465415473769.0799867142197314.50673582473632.788095532
#Sta/Elev= 30
       0 3079.31    19.8 3077.56    31.2 3073.98    36.1 3071.99    52.1 3060.72
    80.6 3051.14    92.8  3051.9   141.4 3048.19     190 3046.91   279.2 3048.81
   295.4 3045.93     344 3045.78   384.5 3048.66   449.1 3048.55   477.4 3047.63
   485.5    3044   517.9 3042.37   538.1 3044.02   554.2 3043.57   562.3 3048.38
   570.4 3049.85   586.6 3046.81   606.8 3048.81   683.6 3049.47   726.7 3045.99
   755.6 3046.65     764    3049   795.6 3065.83   916.1 3088.73949.5803 3097.27
#Mann= 7 ,-1,0
       0      .1       0      90     .06       0     190      .1       0
  397.62     .08       0   485.5    .045       0   538.1     .08       0
  687.62      .1       0
#XS Ineff= 2 , 0
          279.95 3049.51  643.38         3052.36
Permanent Ineff=
       F       F
Bank Sta=485.5,538.1
XS Rating Curve= 0 ,0
Exp/Cntr(USF)=0,0
Exp/Cntr=0.3,0.1

Type RM Length L Ch R = 1 ,41580   ,723.9,717.3,702.2
XS GIS Cut Line= 4
2196464.68670845474226.0586806742196817.44219151474218.041510605
 2197057.9572936474230.0672657092197402.69560658474218.041510605
#Sta/Elev= 30
       0 3082.29    19.9 3079.62    39.5 3072.35    75.5 3072.71    84.6 3067.26
   111.5 3045.71   135.5 3044.05   147.5  3041.1   191.5  3044.8   211.6 3042.91
   283.6 3045.96   315.6 3042.67   327.6 3044.49   407.6 3043.64   427.7 3039.53
   443.7  3041.4   476.7 3040.71   512.6 3040.73   519.8 3043.62   551.8 3041.22
   639.9  3042.2   687.9 3039.39   699.9 3042.89     720 3044.12     812 3042.71
     820 3046.12     836 3058.22     840 3059.19   880.1 3064.56938.6101 3069.02
#Mann= 8 ,-1,0
       0      .1       0      20     .06       0     240     .08       0
   476.7    .045       0   512.6     .08       0  512.85     .07       0
  542.85     .08       0  733.66      .1       0
#XS Ineff= 2 , 0
          191.63 3047.27  758.81         3048.27
Permanent Ineff=
       F       F
Bank Sta=476.7,512.6
XS Rating Curve= 0 ,0
Exp/Cntr(USF)=0,0
Exp/Cntr=0.3,0.1