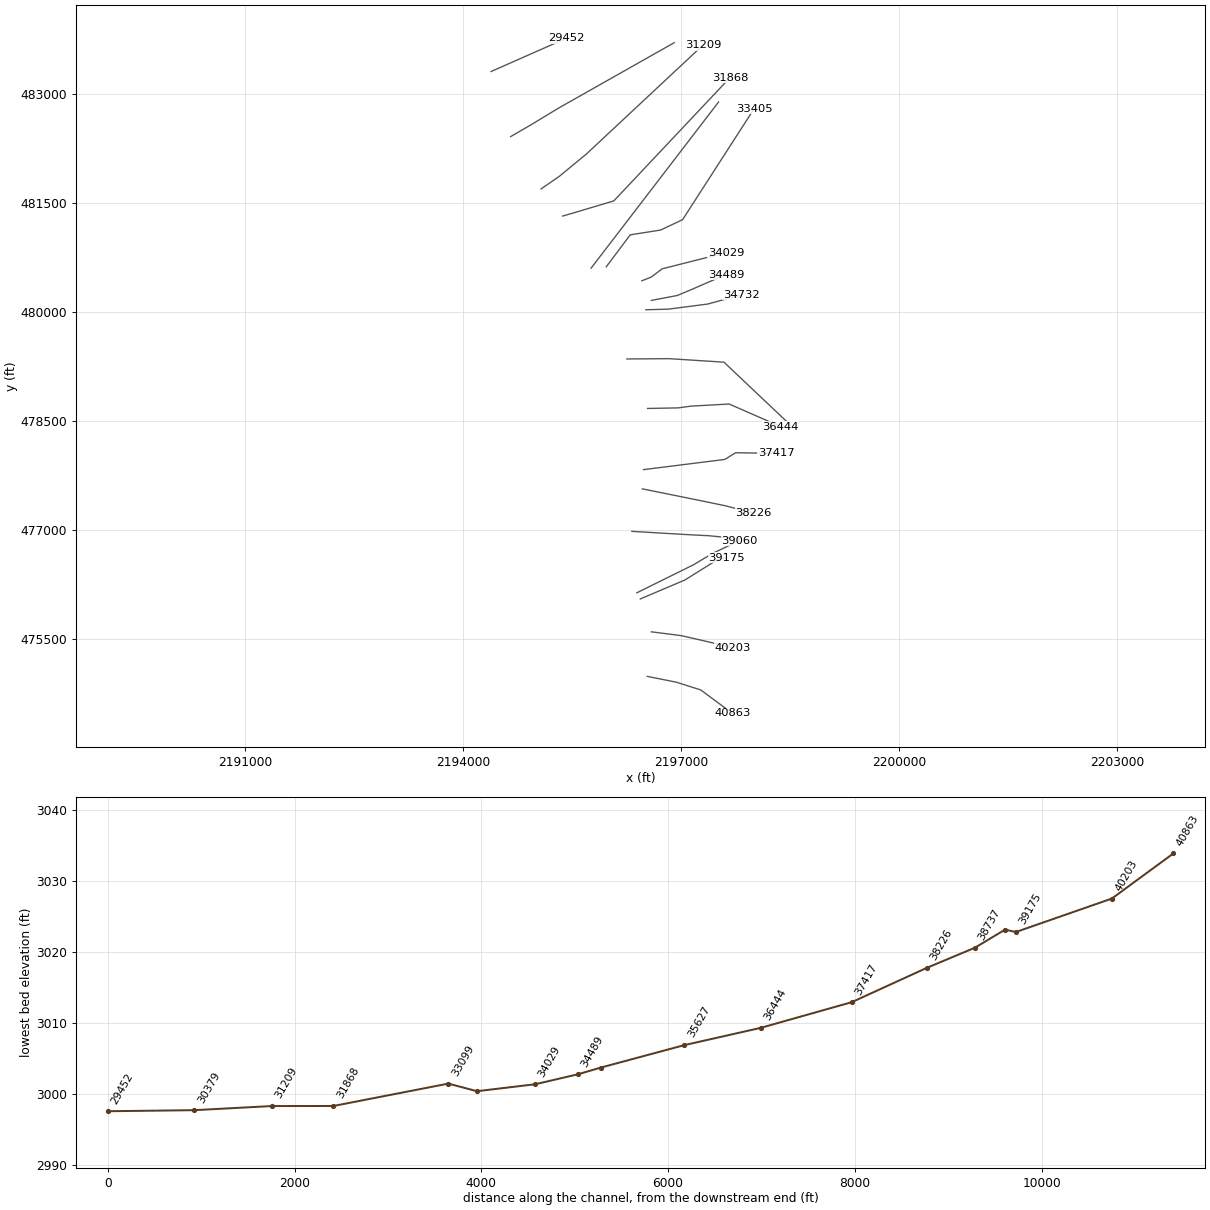
HEC-RAS study WILLIAMSRV.prj: WILLIAMSRV

--- WILLIAMSRV.g01 (geometry) --- (continued)

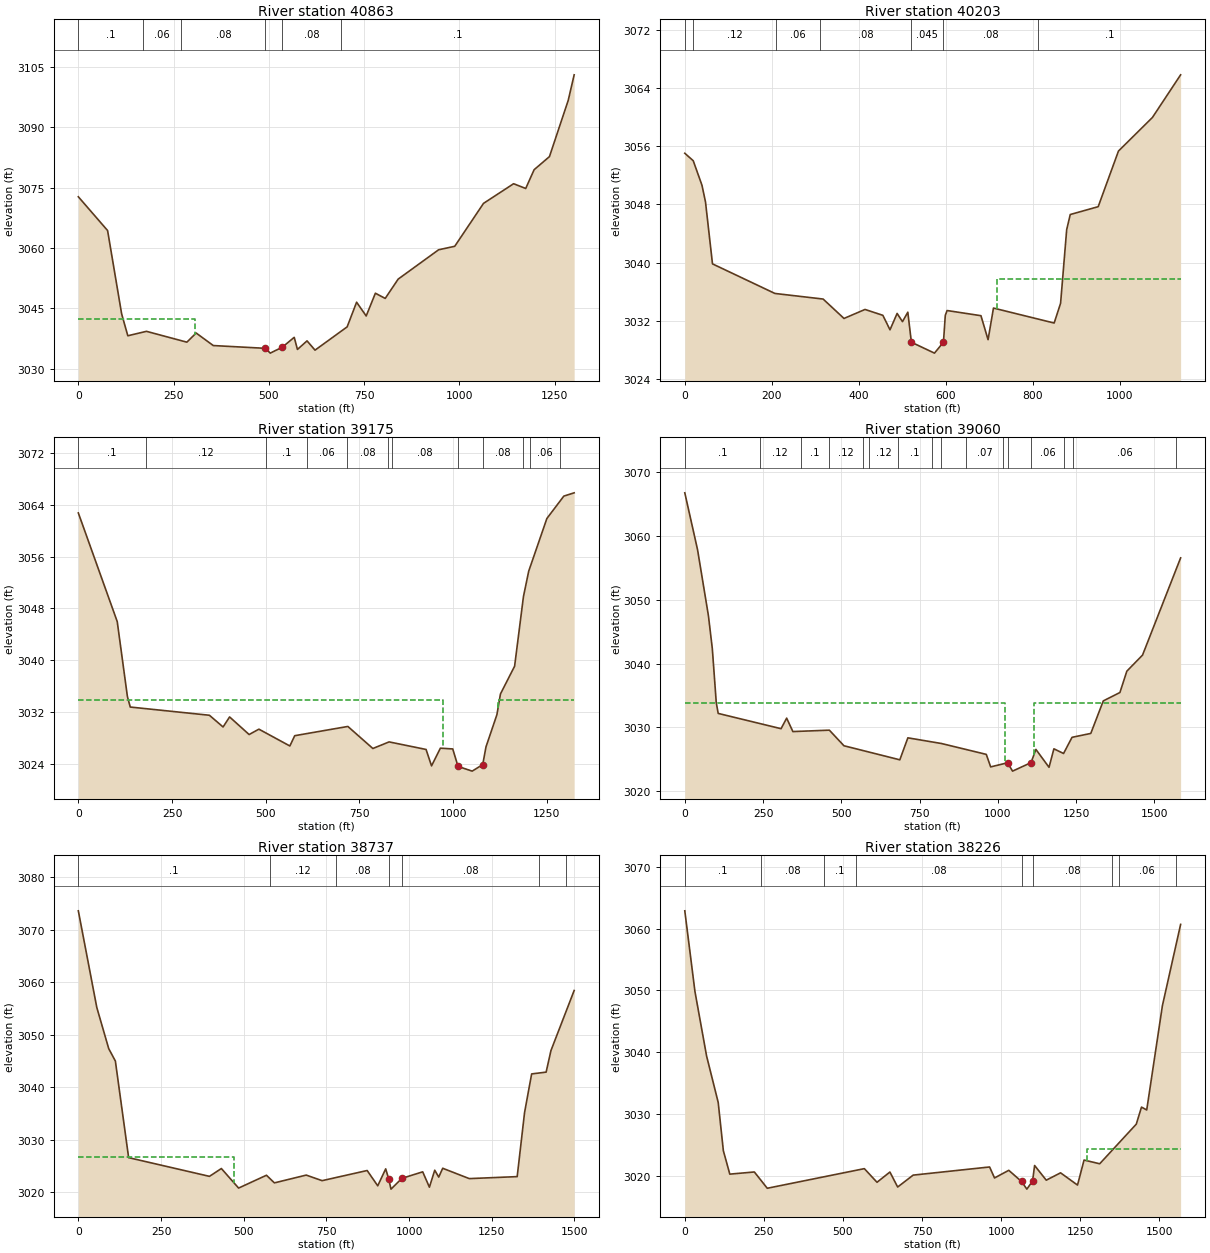
Type RM Length L Ch R = 1 ,40863   ,656.5,659.9,658.8
XS GIS Cut Line= 4
2196536.84123908474979.6726672062196937.69974255474899.500966511
2197271.76441251474793.2686879742197707.34806922474470.582367794
#Sta/Elev= 30
       0 3072.71    76.8 3064.33   113.7 3043.63   129.9 3038.21   178.8 3039.31
   284.9 3036.62   309.3 3038.89   354.2 3035.78   491.1 3035.09   503.7  3033.9
   535.3 3035.37   566.7 3037.82   575.1 3034.81   600.3 3036.94   621.3 3034.64
   705.6 3040.42   730.4 3046.54   755.6 3043.12   779.7 3048.77   805.5 3047.48
   839.5 3052.27   945.6 3059.55     988 3060.42  1063.5 3071.07  1142.5 3075.95
  1174.3 3074.77  1196.3 3079.42  1236.6 3082.68  1285.9 3096.651301.434 3102.98
#Mann= 6 ,-1,0
       0      .1       0     170     .06       0     270     .08       0
   491.1    .045       0   535.3     .08       0   688.8      .1       0
#XS Ineff= 2 , 0
          305.24 3042.46
Permanent Ineff=
       F       F
Bank Sta=491.1,535.3
XS Rating Curve= 0 ,0
Exp/Cntr(USF)=0,0
Exp/Cntr=0.3,0.1

Type RM Length L Ch R = 1 ,40203   ,1001.1,1027.9,1064.5
BEGIN DESCRIPTION:
structure xs 4
END DESCRIPTION:
XS GIS Cut Line= 4
2196592.96142957475592.9861775222197001.83710311 475540.87457207
 2197266.4037154475480.7457965492197711.35665426475376.522585646
#Sta/Elev= 30
       0 3055.04    19.4 3054.01    39.5 3050.64    47.6 3048.35    63.7 3039.82
   207.3 3035.75   318.2 3034.98   366.2 3032.31   414.6 3033.55   455.6 3032.74
     472 3030.75   488.4    3033   500.7 3031.87     513 3033.17  521.183029.039
   574.3 3027.54  594.973029.041   599.2 3032.74   603.3  3033.4   681.2 3032.69
   697.6 3029.39     710 3033.74   849.6 3031.68   864.4  3034.4   878.4 3044.52
   886.6 3046.61   950.9 3047.69   997.5 3055.34  1075.6 3059.961140.493 3065.83
#Mann= 7 ,-1,0
       0      .1       0      20     .12       0     210     .06       0
     310     .08       0  521.18    .045       0  594.97     .08       0
   813.5      .1       0
#XS Ineff= 2 , 0
                          717.62          3037.8
Permanent Ineff=
       F       F
Bank Sta=521.18,594.97
XS Rating Curve= 0 ,0
Exp/Cntr(USF)=0,0
Exp/Cntr=0.5,0.3

Type RM Length L Ch R = 1 ,39175   ,117.2,114.9,116.5
BEGIN DESCRIPTION:
structure xs 3
END DESCRIPTION:
XS GIS Cut Line= 4
2196440.63519825476045.9562864482197053.94870856476306.514313706
2197502.91023245476587.1152661382197627.17636853476615.175361382
#Sta/Elev= 30
       0 3062.76   103.8 3045.96     131 3034.36   138.6 3032.74   349.8 3031.47
   386.3 3029.66   403.7 3031.21   455.8 3028.49   481.9 3029.32   564.5 3026.72
   577.5 3028.31   719.3 3029.74     786 3026.33   829.4 3027.35     928 3026.18
   942.6 3023.64   966.2 3026.38   999.2 3026.26  1013.3 3023.56  1051.1 3022.83
  1079.2 3023.84  1087.9 3026.58  1117.1 3031.57  1126.5 3034.76  1164.3 3039.06
  1187.9 3049.83  1201.9 3053.75  1250.4  3061.9  1295.6 3065.361323.198 3065.87
#Mann= 12 ,-1,0
       0      .1       0     180     .12       0     500      .1       0
     610     .06       0  716.37     .08       0  826.37     .06       0
  836.37     .08       0  1013.3    .045       0  1079.2     .08       0
 1186.37      .1       0  1205.8     .06       0  1285.8      .1       0
#XS Ineff= 2 , 0
             973  3033.8    1120          3033.8
Permanent Ineff=
       F       F
Bank Sta=1013.3,1079.2
XS Rating Curve= 0 ,0
Exp/Cntr(USF)=0,0
Exp/Cntr=0.5,0.3

Type RM Length L Ch R = 1 ,39060   ,337.7,323.1,291.9
BEGIN DESCRIPTION:
structure xs 2
END DESCRIPTION:
XS GIS Cut Line= 4
2196392.53217783476130.1365721782197170.19767457476514.960735513
 2197438.7728719476675.3041369032197803.55411006476847.673293397
#Sta/Elev= 30
       0 3066.72    40.8 3057.81    75.5 3047.49      88  3042.3   100.5 3033.89
   106.7  3032.2   307.5 3029.81   325.4 3031.46   345.3 3029.36   461.8 3029.58
   508.4 3027.14   686.9 3024.94   712.6 3028.38     820 3027.49   963.1 3025.79
   977.1 3023.83  1031.2 3024.48    1047 3023.17  1106.1  3024.5  1121.6 3026.57
  1163.5 3023.77  1179.1 3026.66    1210 3025.93    1237 3028.46    1297 3029.07
  1336.9 3034.16    1390 3035.47  1412.1 3038.81  1462.3 3041.331583.925 3056.54
#Mann= 16 ,-1,0
       0      .1       0     240     .12       0     370      .1       0
     460     .12       0     570      .1       0     590     .12       0
     680      .1       0     790     .06       0     820     .12       0
  897.67     .07       0 1017.67     .06       0  1031.2    .045       0
  1106.1     .06       0 1210.47     .08       0 1240.47     .06       0
 1570.47      .1       0
#XS Ineff= 2 , 0
            1022  3033.8    1115          3033.8
Permanent Ineff=
       F       F
Bank Sta=1031.2,1106.1
XS Rating Curve= 0 ,0
Exp/Cntr(USF)=0,0
Exp/Cntr=0.5,0.3

Type RM Length L Ch R = 1 ,38737   ,513.9,511.2,502.3
XS GIS Cut Line= 4
2196324.38623224476975.9480145082197142.13757933476927.844994091
2197386.66126645476915.819238987 2197819.5884502476871.724803605
#Sta/Elev= 30
       0 3073.57    55.9 3055.17    91.9 3047.35     112 3044.99   152.1 3026.61
   396.5 3023.05   432.5 3024.54   484.6 3020.82   568.8 3023.26   592.8 3021.81
     689 3023.29   737.1 3022.23   873.3 3024.16   905.3 3021.25   929.3 3024.48
   938.2  3022.6   945.4 3020.62   978.3 3022.67  1041.2 3023.91  1061.5 3020.99
  1077.6 3024.22  1089.7 3022.91  1101.7 3024.59  1182.1 3022.62  1326.9    3023
  1349.2 3035.19  1370.6 3042.54  1414.4 3042.88    1429 3046.981499.151 3058.41
#Mann= 7 ,-1,0
       0      .1       0     580     .12       0     780     .08       0
   938.2    .045       0   978.3     .08       0 1393.98     .06       0
 1473.98      .1       0
#XS Ineff= 2 , 0
          469.89 3026.76
Permanent Ineff=
       F       F
Bank Sta=938.2,978.3
XS Rating Curve= 0 ,0
Exp/Cntr(USF)=0,0
Exp/Cntr=0.3,0.1

Type RM Length L Ch R = 1 ,38226   ,770.3,808.6,829.4
XS GIS Cut Line= 4
2196468.69529349477561.2014295812197318.51532085477388.832273087
2197607.13344336477328.7034975662197999.97477676477228.488871697
#Sta/Elev= 30
       0 3062.91    32.1 3049.83    68.9 3039.38   105.6 3031.86   121.9 3024.03
   142.3 3020.24   219.9 3020.59   260.7 3017.95   567.6 3021.13   607.6 3018.92
   648.4 3020.58   672.9 3018.15   721.9 3020.08   963.5  3021.4   979.1 3019.62
  1024.1 3020.86  1064.4 3019.05  1081.3 3017.81 1099.42 3019.13  1105.8 3021.64
  1142.6 3019.26  1187.8 3020.45  1241.4 3018.47  1262.1 3022.52  1311.6 3021.92
  1427.2 3028.34  1443.7  3031.1  1460.2 3030.64  1509.8 3047.551567.362 3060.71
#Mann= 9 ,-1,0
       0      .1       0     240     .08       0     440      .1       0
     540     .08       0  1064.4    .045       0 1099.42     .08       0
 1351.94      .1       0 1371.94     .06       0 1551.94      .1       0
#XS Ineff= 2 , 0
                         1272.25         3024.27
Permanent Ineff=
       F       F
Bank Sta=1064.4,1099.42
XS Rating Curve= 0 ,0
Exp/Cntr(USF)=0,0
Exp/Cntr=0.3,0.1

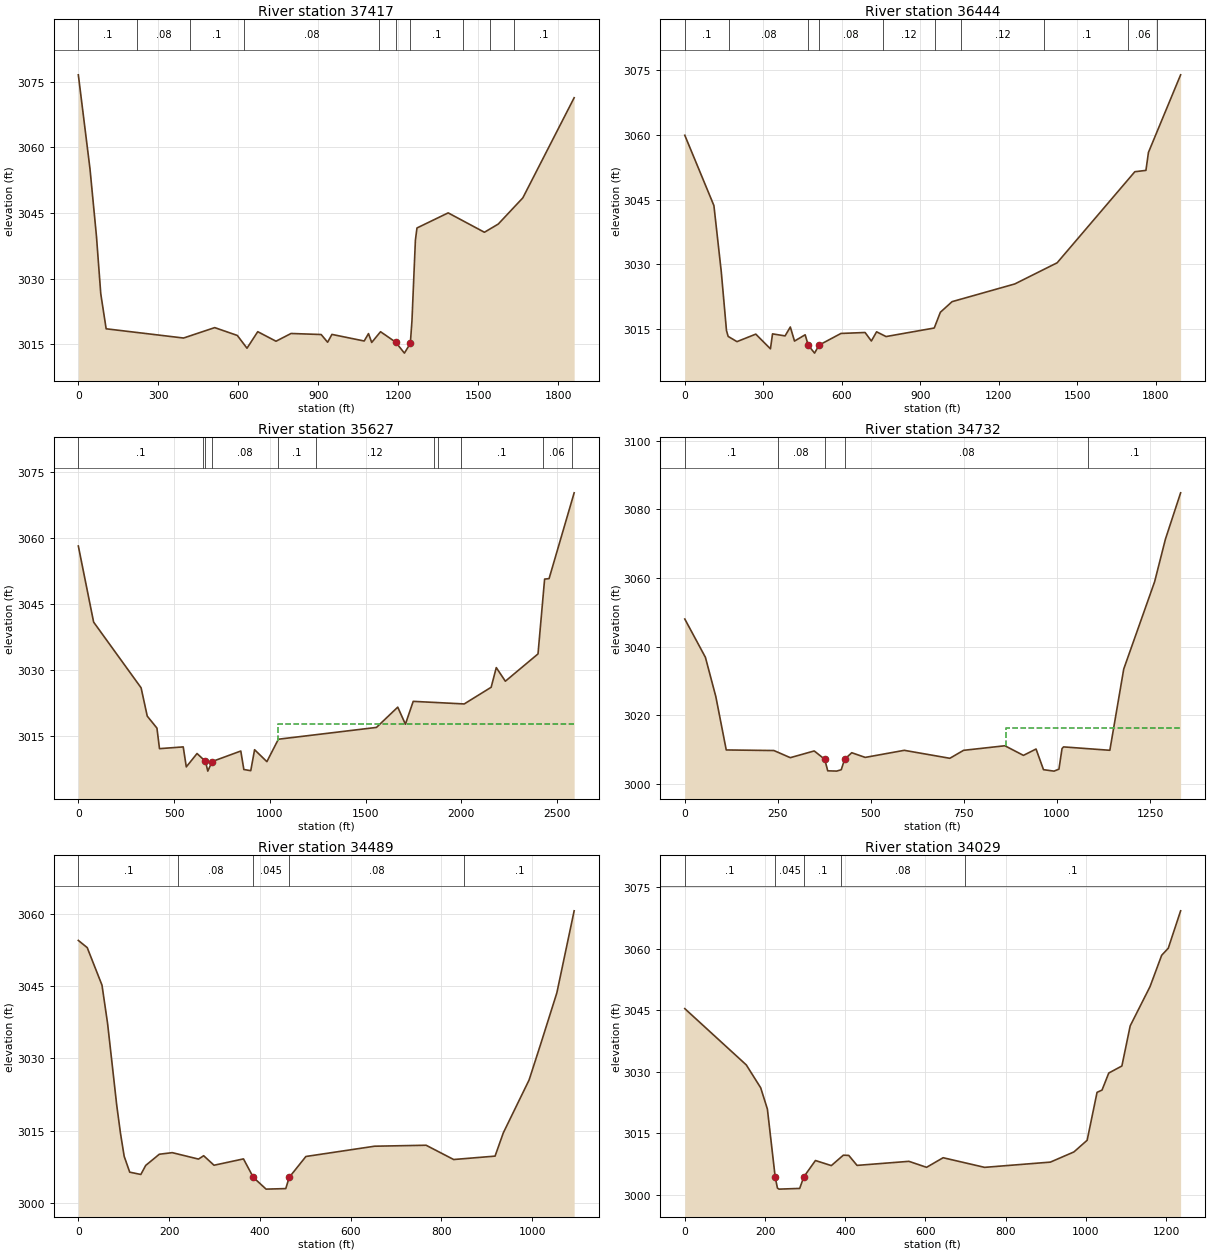
Type RM Length L Ch R = 1 ,37417   ,979.4,973.7,957
XS GIS Cut Line= 4
2196484.72963363477825.7680418742197603.12485832 477966.06851809
2197751.44250461478058.2659738892198308.63582444 478050.24880382
#Sta/Elev= 30
       0 3076.55    43.8 3055.02      68 3039.63    84.1 3026.53   104.3 3018.51
   394.5  3016.4   511.4 3018.78   596.1 3016.99   632.4 3014.07   672.7 3017.85
   741.2 3015.67   797.6 3017.44   910.5  3017.2   934.7 3015.44   950.8 3017.23
  1071.8 3015.72  1087.9 3017.41    1100 3015.39  1133.1 3017.84  1189.6 3015.47
  1222.6 3012.95 1244.763015.172  1250.9 3020.32  1263.8 3038.75  1269.7 3041.55
  1386.7    3045  1522.6 3040.57  1574.6 3042.45  1666.6 3048.43 1859.05 3071.31
#Mann= 10 ,-1,0
       0      .1       0     220     .08       0     420      .1       0
     620     .08       0 1127.16      .1       0  1189.6    .045       0
 1244.76      .1       0  1441.8     .06       0  1541.8     .07       0
  1631.8      .1       0
Bank Sta=1189.6,1244.76
XS Rating Curve= 0 ,0
Exp/Cntr(USF)=0,0
Exp/Cntr=0.3,0.1

Type RM Length L Ch R = 1 ,36444   ,815.8,817.2,804
XS GIS Cut Line= 5
2196540.84982411 478667.570899172196961.75125276 478675.58806924
2197136.00473369478699.4572712282197663.25363384478728.830623447
2198368.76459996478419.038627016
#Sta/Elev= 30
       0 3059.93   111.3  3043.6   139.4 3028.26   159.4 3014.56   165.8 3013.22
   199.4 3012.01   271.4 3013.75   327.4 3010.34   335.4 3013.81   383.4 3013.34
   403.4 3015.41   419.4 3012.14   460.1  3013.6   471.9 3011.18   496.1 3009.34
   513.3  3011.2     597 3013.91   689.2 3014.13   713.2 3012.15   733.2 3014.29
   769.4 3013.19   953.6 3015.17     977 3018.83  1021.7 3021.29  1261.4  3025.4
  1423.4 3030.31  1720.4 3051.46  1762.8 3051.77  1772.5 3055.951895.455 3073.96
#Mann= 10 ,-1,0
       0      .1       0     170     .08       0   471.9    .045       0
   513.3     .08       0  756.86     .12       0  956.86      .1       0
 1056.86     .12       0 1374.92      .1       0 1694.92     .06       0
 1804.92      .1       0
Bank Sta=471.9,513.3
XS Rating Curve= 0 ,0
Exp/Cntr(USF)=0,0
Exp/Cntr=0.3,0.1

Type RM Length L Ch R = 1 ,35627   ,878.5,894.2,896.6
XS GIS Cut Line= 4
2196256.24028665479349.0303550762196837.48511669479353.038940111
2197591.09910322479304.935919694 2198501.0479061478443.090137224
#Sta/Elev= 30
       0 3058.21    79.9 3040.87   327.9 3025.89   359.9 3019.45   410.6 3016.71
   423.9 3012.03   547.9 3012.43   563.9 3007.87     620 3010.92   664.1 3009.14
   676.1 3006.91  699.16  3009.1   848.5 3011.49   864.5 3007.28   900.6 3007.01
   920.6 3011.79   984.8 3009.07  1044.9 3014.18  1557.1 3016.87  1668.4 3021.49
  1708.3  3017.6  1749.1 3022.81  2015.5 3022.22  2156.2 3026.02    2183  3030.5
  2230.4  3027.4  2400.9 3033.62  2435.4 3050.67  2458.7 3050.782589.716 3070.33
#Mann= 11 ,-1,0
       0      .1       0  651.26     .08       0   664.1    .045       0
  699.16     .08       0 1041.26      .1       0 1241.26     .12       0
 1856.41      .1       0 1876.41     .12       0 1996.41      .1       0
 2426.41     .06       0 2576.41      .1       0
#XS Ineff= 2 , 0
                         1040.75         3017.58
Permanent Ineff=
       F       F
Bank Sta=664.1,699.16
XS Rating Curve= 0 ,0
Exp/Cntr(USF)=0,0
Exp/Cntr=0.3,0.1

Type RM Length L Ch R = 1 ,34732   ,212.5,243.7,258.8
XS GIS Cut Line= 4
2196516.79831391480026.4812259482196825.45936158480034.498396018
2197366.74260601480104.8825031582197827.60562027 480230.91906272
#Sta/Elev= 30
       0 3048.07    55.4 3036.91    83.4 3025.46   111.4 3009.92   239.5 3009.75
   283.5 3007.67   347.8 3009.63     376  3007.2   384.1 3003.84   408.3 3003.76
   420.4 3004.16   429.4 3007.17   448.6 3009.11   484.9 3007.75   589.8 3009.81
   712.2 3007.49   749.1 3009.81   860.2 3011.14     910 3008.34   943.9 3010.19
   963.9 3004.17   992.2 3003.75  1005.4 3004.33  1013.7 3010.31  1017.8 3010.81
  1142.2 3009.82  1179.5 3033.49  1262.5 3058.93  1291.5 3071.321332.392 3084.84
#Mann= 5 ,-1,0
       0      .1       0     250     .08       0     376    .045       0
   429.4     .08       0 1084.61      .1       0
#XS Ineff= 2 , 0
                          863.66         3016.33
Permanent Ineff=
       F       F
Bank Sta=376,429.4
XS Rating Curve= 0 ,0
Exp/Cntr(USF)=0,0
Exp/Cntr=0.3,0.1

Type RM Length L Ch R = 1 ,34489   ,441.2,460.1,467.5
XS GIS Cut Line= 4
2196592.96142957 480154.755947062196949.72549766480222.901892651
 2197150.1547494 480307.082178382197619.15919846480511.520015152
#Sta/Elev= 30
       0 3054.56    19.6 3053.06    52.1 3045.26    64.4 3037.32    84.7 3020.18
    92.9 3014.41     101 3009.64   113.2 3006.34   137.7 3005.86   148.4 3007.74
   178.4 3010.07   206.9  3010.4   264.7 3009.06   276.1 3009.76   298.9 3007.78
   363.8  3009.1  385.543005.249   413.6 3002.81     457 3002.92  464.453005.247
   501.3  3009.6   652.6 3011.74   766.1 3011.94   826.8 3008.97     918 3009.68
   936.2 3014.53     993 3025.53  1018.3 3032.94  1054.1 3043.651092.229 3060.72
#Mann= 5 ,-1,0
       0      .1       0     220     .08       0  385.54    .045       0
  464.45     .08       0   850.6      .1       0
Bank Sta=385.54,464.45
XS Rating Curve= 0 ,0
Exp/Cntr(USF)=0,0
Exp/Cntr=0.3,0.1

Type RM Length L Ch R = 1 ,34029   ,646.5,623.3,602.2
XS GIS Cut Line= 4
2196461.49743641 480425.195218912196587.96856919480474.683923043
2196742.52984209480590.0472463722197622.08597869480812.911894439
#Sta/Elev= 30
       0 3045.43   153.4 3031.69   189.2 3026.12   205.9 3020.93  225.283004.397
   230.9 3001.66   234.9  3001.4   286.4 3001.57   296.73004.396   325.7 3008.38
   365.3 3007.14   395.2 3009.68   408.8 3009.62   429.4 3007.19   558.7 3008.18
   602.7 3006.72     644 3009.06   747.4 3006.71   911.4 3007.99     970 3010.47
    1003 3013.32  1027.7 3025.01  1040.1 3025.56  1056.9 3029.72  1089.6 3031.44
  1110.3 3041.22  1159.8 3050.81  1188.8 3058.45  1205.2 3060.161236.029 3069.29
#Mann= 5 ,-1,0
       0      .1       0  225.28    .045       0   296.7      .1       0
  388.68     .08       0  698.68      .1       0
Bank Sta=225.28,296.7
XS Rating Curve= 0 ,0
Exp/Cntr(USF)=0,0
Exp/Cntr=0.3,0.1

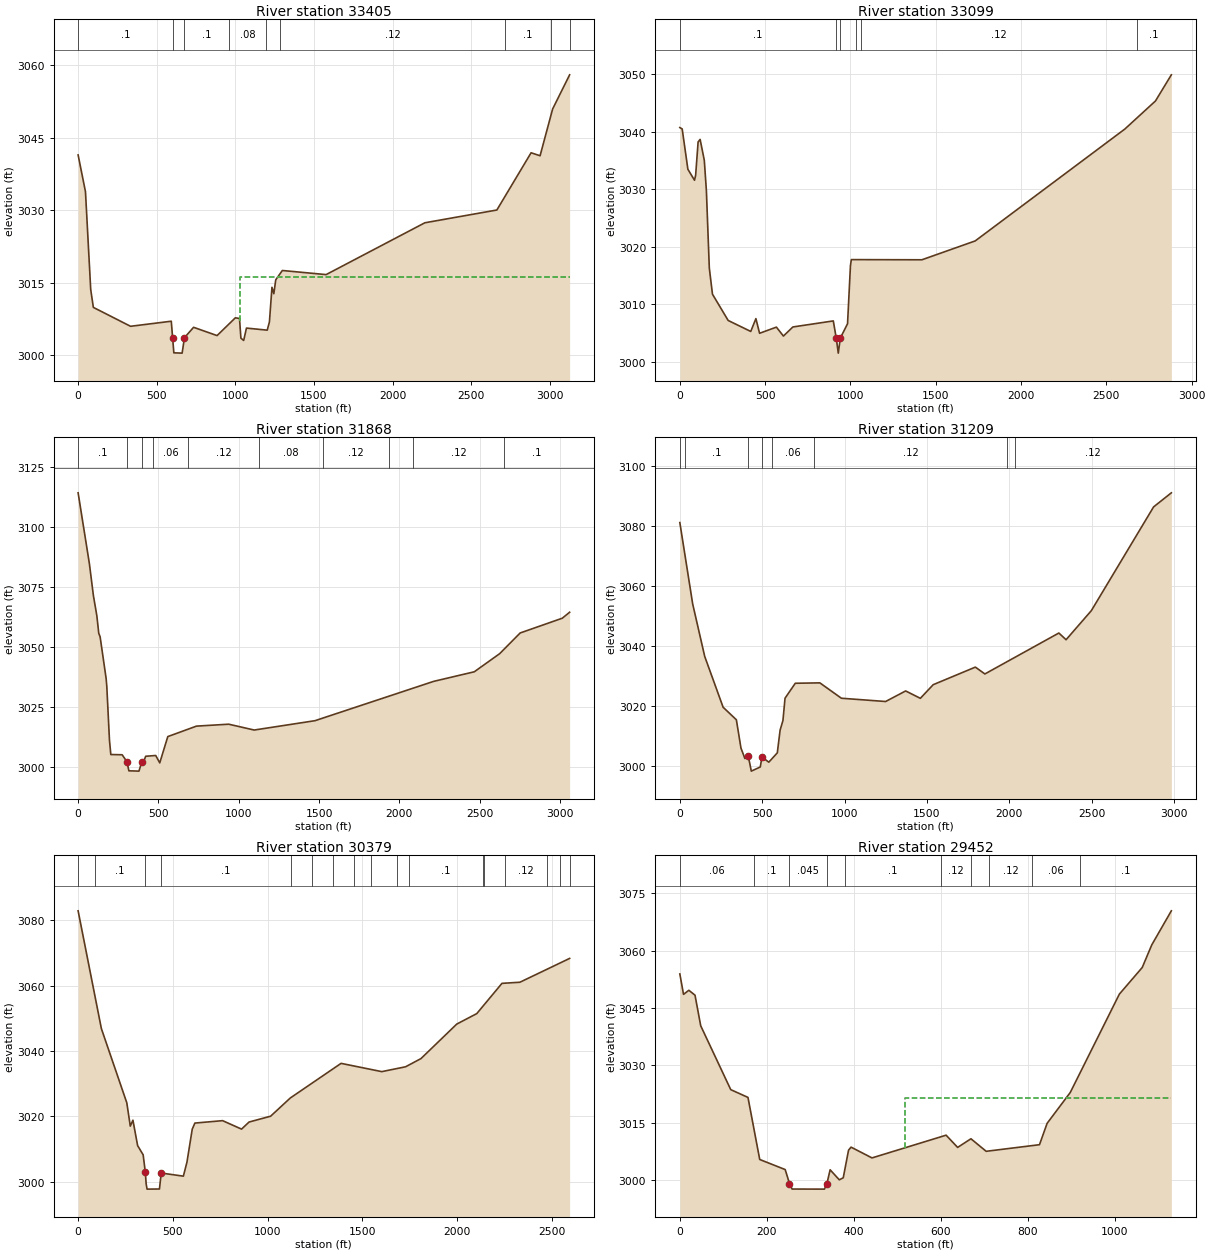
Type RM Length L Ch R = 1 ,33405   ,286.6,306,321.5
XS GIS Cut Line= 5
2195972.10913999480617.6512905372196302.03383421481057.550882827
2196719.93844688481123.5358216712197022.36941658481266.503189165
2198006.64475433482795.154272373
#Sta/Elev= 30
       0 3041.41    46.8 3033.81    80.1 3013.58    96.9 3009.88   333.4 3005.97
   592.5 3007.02  601.163003.528   608.7 3000.48   661.4 3000.42  676.34 3003.62
   734.3 3005.76   883.7 3004.05   999.8 3007.72  1026.3 3007.59  1035.2 3003.51
  1052.9 3003.04  1070.5  3005.6  1202.7 3005.17  1216.6 3006.88  1232.7 3014.03
  1244.7 3012.71  1256.8 3015.58  1298.8 3017.51  1577.1 3016.66  2205.1 3027.38
  2662.9 3030.02  2880.6 3041.86  2937.7 3041.24  3017.6 3050.92  3125.6 3057.98
#Mann= 9 ,-1,0
       0      .1       0  601.16    .045       0  676.34      .1       0
  959.87     .08       0 1192.96     .06       0 1282.96     .12       0
 2717.48      .1       0 3007.48     .12       0  3125.6      .1       0
#XS Ineff= 2 , 0
                         1027.32         3016.21
Permanent Ineff=
       F       F
Bank Sta=601.16,676.34
XS Rating Curve= 0 ,0
Exp/Cntr(USF)=0,0
Exp/Cntr=0.3,0.1

Type RM Length L Ch R = 1 ,33099   ,1276.5,1231.1,1144.6
XS GIS Cut Line= 2
2195763.78772687480599.3237818452197516.83180373 482885.49816147
#Sta/Elev= 30
       0 3040.71    13.8 3040.47    47.2 3033.46    86.1 3031.55    92.7 3032.43
   107.2 3038.22     119 3038.65   143.5 3035.01   155.7 3029.72   172.8 3016.28
   191.3 3011.74   283.3 3007.17   415.7 3005.26   445.9 3007.49   467.4 3004.94
     566 3006.01   607.2 3004.46   662.7 3006.04   899.6 3007.09  916.63 3004.12
   928.8 3001.49   940.7 3004.11     983  3006.6  1000.1 3016.73  1005.4 3017.75
  1418.8 3017.72  1731.3    3021  2608.3 3040.45  2787.8 3045.33  2880.9 3049.88
#Mann= 6 ,-1,0
       0      .1       0  916.63    .045       0   940.7      .1       0
    1030     .06       0    1060     .12       0    2680      .1       0
Bank Sta=916.63,940.7
XS Rating Curve= 0 ,0
Exp/Cntr(USF)=0,0
Exp/Cntr=0.3,0.1

Type RM Length L Ch R = 1 ,31868   ,634.1,659.3,676.4
XS GIS Cut Line= 4
2195372.74594549481315.9918932982195598.19448654481381.976832141
2196076.58529316481524.9441996352197671.22131521483218.557629952
#Sta/Elev= 30
       0 3114.23    70.3  3084.7    95.3 3071.38   116.6 3063.06   128.6 3055.71
   136.9 3054.33   174.5 3036.89   178.6 3033.65   195.3 3011.18   203.6 3005.25
   274.4 3005.15   303.8 3002.25   316.2 2998.47   378.9 2998.34   395.6 3002.02
     404 3001.55   420.7 3004.53   483.2 3004.85   508.3 3001.77   558.4 3012.72
   736.9 3017.08   937.8 3017.88  1096.3 3015.45  1474.7 3019.34    2214 3035.72
  2466.6  3039.7  2624.5 3047.23  2752.5 3055.87  3014.8 3062.02  3060.4 3064.51
#Mann= 10 ,-1,0
       0      .1       0   303.8    .045       0   395.6      .1       0
  464.91     .06       0  684.91     .12       0  1124.2     .08       0
  1524.2     .12       0  1934.2     .08       0  2084.2     .12       0
  2654.2      .1       0
Bank Sta=303.8,395.6
XS Rating Curve= 0 ,0
Exp/Cntr(USF)=0,0
Exp/Cntr=0.3,0.1

Type RM Length L Ch R = 1 ,31209   ,835.1,830.2,820.3
XS GIS Cut Line= 4
 2195075.8137207481689.9065467442195323.25724136481860.367638757
2195697.17189481 482168.297353362197302.80540667 483669.45471205
#Sta/Elev= 30
       0 3081.15    78.2 3053.98     151 3036.56   262.7 3019.62   343.1 3015.44
     371 3006.02   394.9 3002.53   415.4 3003.29   433.9 2998.33   488.2 2999.71
   498.6 3003.04     540 3001.31   591.6 3004.42   608.6    3012   625.7 3015.17
   638.5 3022.63   700.7 3027.61   849.9 3027.74   980.6 3022.62  1248.9 3021.53
  1370.6 3025.05  1459.7 3022.59  1537.6 3027.13  1793.6 3032.99  1851.3 3030.71
  2300.3 3044.35  2344.1 3042.12  2497.5 3051.81  2875.3 3086.382982.939 3091.07
#Mann= 8 ,-1,0
       0     .06       0      30      .1       0   415.4    .045       0
   498.6      .1       0  560.48     .06       0  814.86     .12       0
 1984.86      .1       0 2034.86     .12       0
Bank Sta=415.4,498.6
XS Rating Curve= 0 ,0
Exp/Cntr(USF)=0,0
Exp/Cntr=0.3,0.1

Type RM Length L Ch R = 1 ,30379   ,930.4,926.7,916.8
XS GIS Cut Line= 4
2194657.90910802482410.242129119 2194932.8463532482569.705731324
2195323.25724136 482806.15176218 2196906.8957736483702.447181472
#Sta/Elev= 30
       0  3082.9   122.8 3046.86   256.9 3024.17   275.4 3017.03   289.3 3018.84
     314 3011.08   343.2 3008.25   354.5 3003.03   359.1 2999.38   363.8 2997.75
   429.3 2997.79   438.6 3002.67   555.5 3001.72   574.3 3005.97   602.3  3016.1
   616.3 3017.96   762.6  3018.7   862.6 3016.11   902.2 3018.28  1015.9 3020.06
    1120 3025.64  1387.7 3036.23  1602.6  3033.7  1728.1 3035.18  1809.5 3037.69
  1998.1 3048.24  2104.1 3051.46  2236.9 3060.71  2331.5 3061.05 2593.95 3068.34
#Mann= 17 ,-1,0
       0     .06       0      90      .1       0   354.5    .045       0
   438.6      .1       0 1124.26     .06       0 1234.26     .12       0
 1344.26      .1       0 1454.26     .12       0 1544.26      .1       0
 1684.26     .12       0 1744.26      .1       0 2134.26     .12       0
 2144.26      .1       0 2254.26     .12       0 2474.26      .1       0
 2544.26     .12       0 2593.95      .1       0
Bank Sta=354.5,438.6
XS Rating Curve= 0 ,0
Exp/Cntr(USF)=0,0
Exp/Cntr=0.3,0.1

Type RM Length L Ch R = 1 ,29452   ,955.3,982.5,1027.2
XS GIS Cut Line= 2
2194388.21847874483305.8709059622195421.38851806483762.398128927
#Sta/Elev= 30
       0 3053.93     8.5 3048.58    20.7 3049.65    34.9 3048.37      48 3040.36
     117 3023.64   156.6 3021.61   183.6 3005.36   242.1 3002.72     252 2999.07
     258 2997.62   332.3  2997.6  338.01 2999.04   345.4 3002.66   366.4 3000.04
   375.5 3000.56   387.7 3007.79   393.5 3008.59   441.6 3005.77   611.9 3011.72
   638.4 3008.52     669 3010.78     704  3007.5   826.5 3009.23     844 3014.82
   897.2 3022.89  1010.1 3048.65  1062.6 3055.61  1084.5 3061.53  1129.5 3070.45
#Mann= 10 ,-1,0
       0     .06       0     170      .1       0     252    .045       0
  338.01    .025       0     380      .1       0     600     .12       0
     670      .1       0     710     .12       0     810     .06       0
     920      .1       0
#XS Ineff= 2 , 0
                          518.28         3021.55
Permanent Ineff=
       F       F
Bank Sta=252,338.01
XS Rating Curve= 0 ,0
Exp/Cntr(USF)=0,0
Exp/Cntr=0.3,0.1