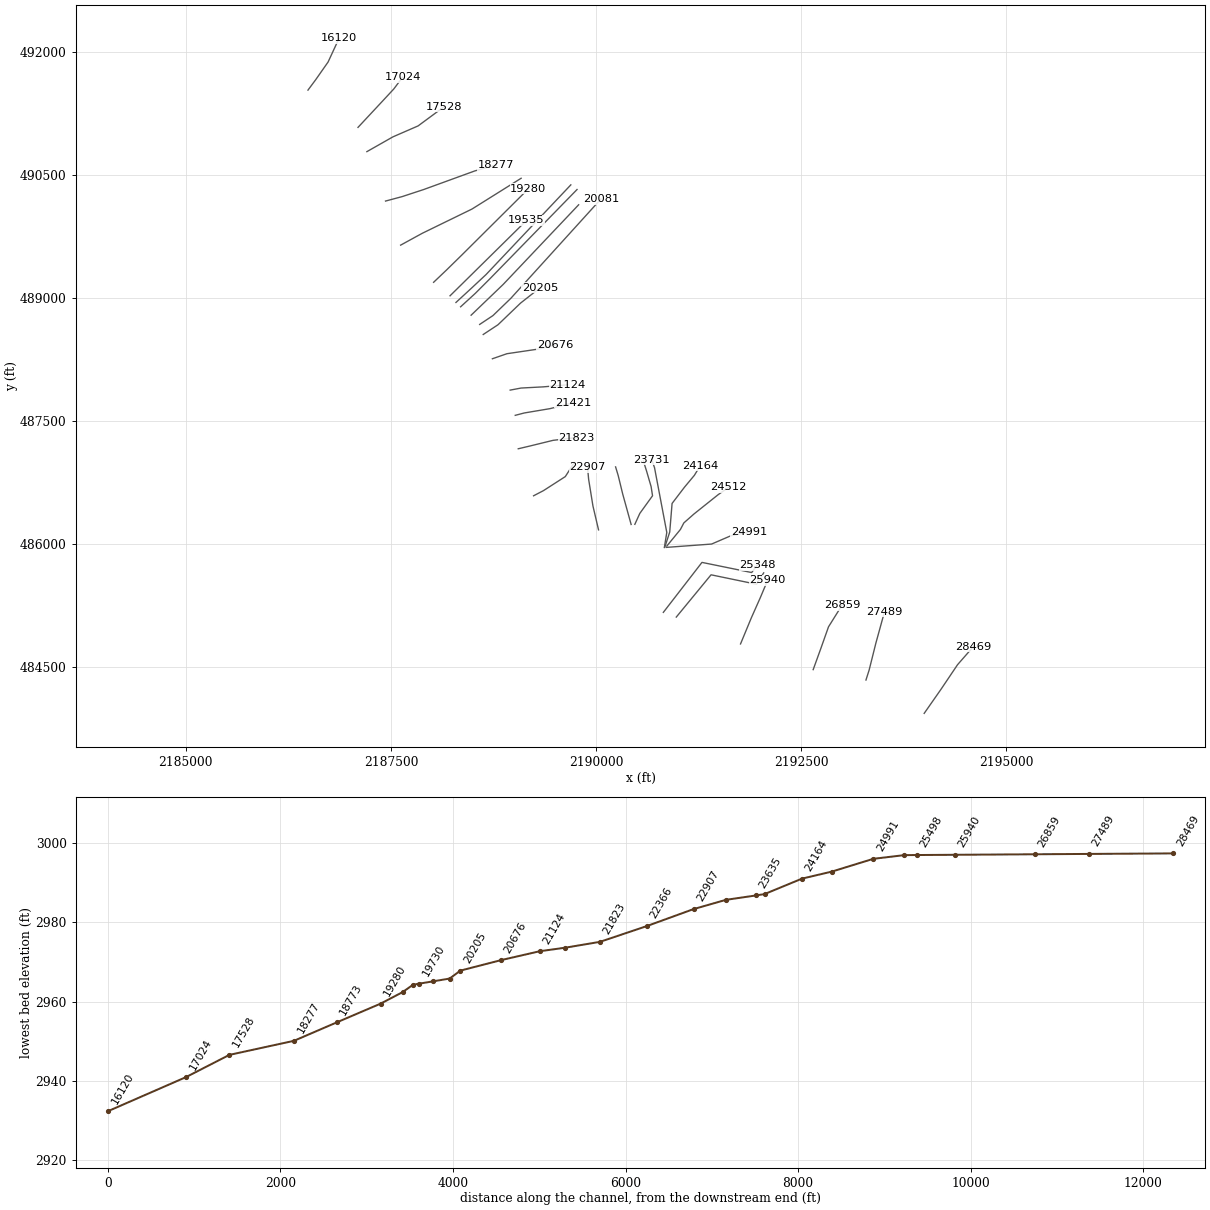
HEC-RAS study WILLIAMSRV.prj: WILLIAMSRV

--- WILLIAMSRV.g01 (geometry) --- (continued)

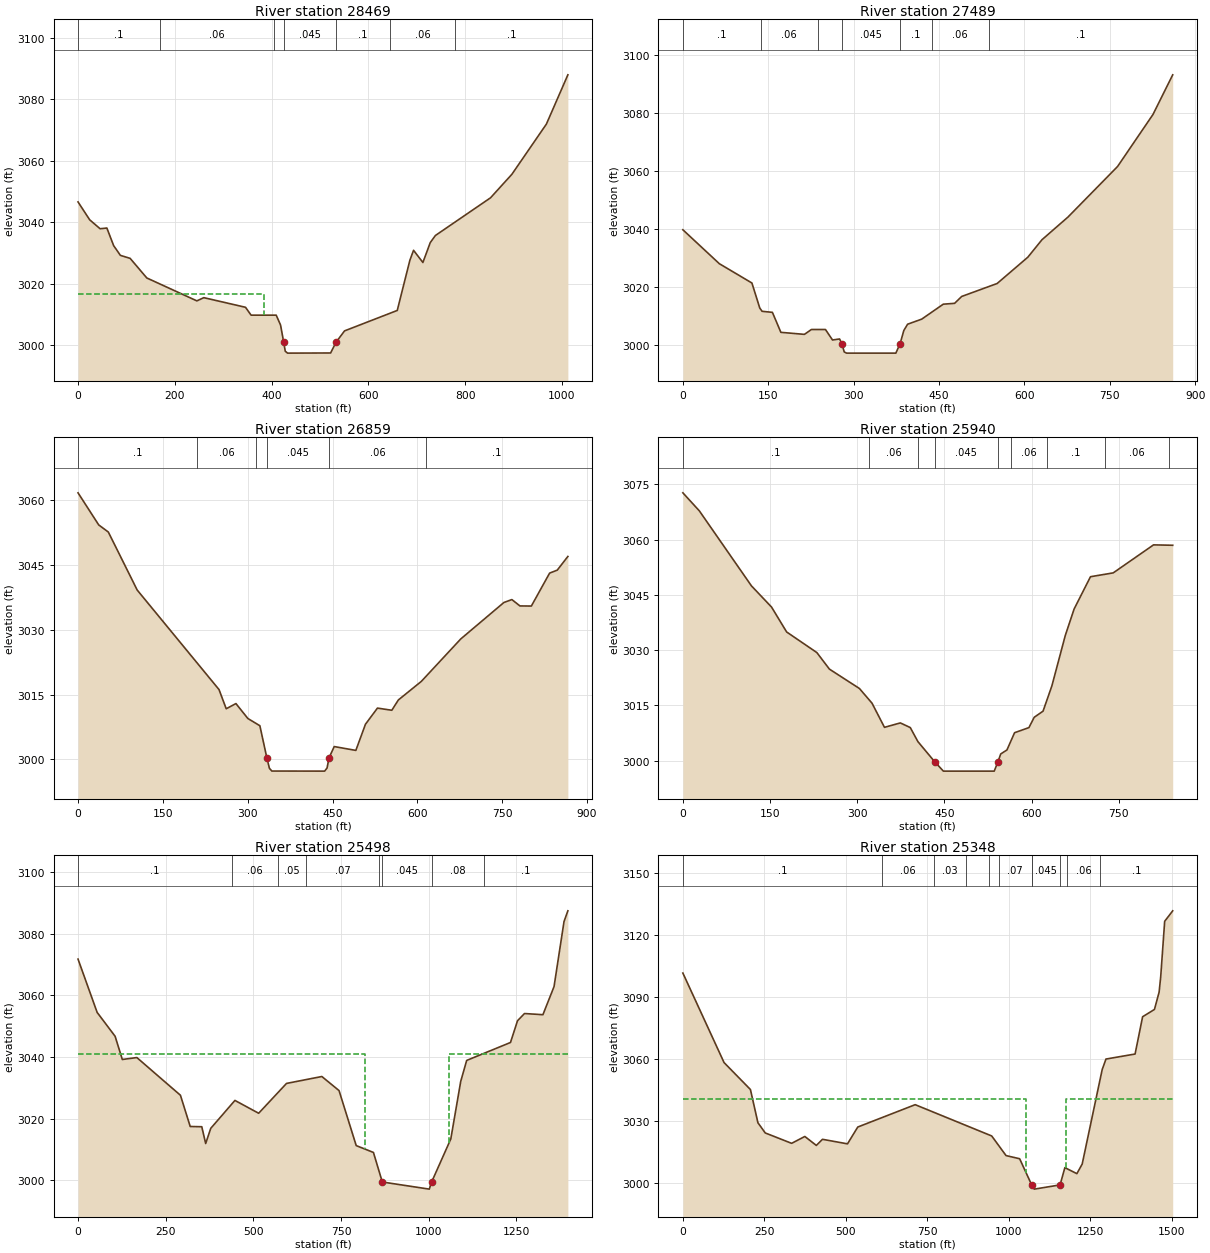
Type RM Length L Ch R = 1 ,28469   ,961.7,980.1,1005
XS GIS Cut Line= 4
2193998.05971959483933.3944674242194201.51328102484224.827947316
2194404.96684245484527.2589170162194597.42291408484747.208713161
#Sta/Elev= 30
       0 3046.62    24.1  3040.8    45.6  3037.9    59.6 3038.13    73.6 3032.41
    87.5 3029.25   107.7 3028.27   142.1  3021.9   245.6 3014.45   259.9  3015.5
   346.1 3012.37   357.6 3009.81   409.5 3009.81   418.5  3006.6  424.983001.005
   428.2 2998.09     433 2997.47   521.9 2997.52  533.123001.007   550.7  3004.7
   659.6 3011.34   685.7 3027.65   693.3 3030.89   712.6 3026.93   727.8 3033.39
   738.4  3035.7   852.4 3047.96   896.5  3055.6   967.8 3071.921012.184 3087.93
#Mann= 7 ,-1,0
       0      .1       0     170     .06       0  405.42    .025       0
  424.98    .045       0  533.12      .1       0  645.42     .06       0
  779.92      .1       0
#XS Ineff= 2 , 0
          383.26 3016.55
Permanent Ineff=
       F       F
Bank Sta=424.98,533.12
XS Rating Curve= 0 ,0
Exp/Cntr(USF)=0,0
Exp/Cntr=0.3,0.1

Type RM Length L Ch R = 1 ,27489   ,635.3,629.9,623.6
XS GIS Cut Line= 4
2193288.72162702484340.3015902922193327.21284134484461.273978172
 2193409.6940149 484791.198672392193514.17016807 485170.61207074
#Sta/Elev= 30
       0 3039.88      64 3028.19   121.3 3021.52   135.1  3012.9   139.2 3011.76
   157.3  3011.4   172.2 3004.51   213.5 3003.81   225.8 3005.48   250.5 3005.49
   262.9 3001.87   275.3 3002.22  279.293000.624   283.5 2997.75   287.7 2997.34
   374.2 2997.34  381.653000.623   388.2 3005.15   394.8 3007.31   419.6 3009.06
   457.5 3014.22   477.4 3014.51   489.8 3016.88   552.1 3021.35     606 3030.41
   630.9 3036.45   676.5 3044.25   763.7  3061.7   825.9 3079.64 860.562 3093.31
#Mann= 7 ,-1,0
       0      .1       0  136.95     .06       0  236.95    .025       0
  279.29    .045       0  381.65      .1       0  436.95     .06       0
  537.03      .1       0
Bank Sta=279.29,381.65
XS Rating Curve= 0 ,0
Exp/Cntr(USF)=0,0
Exp/Cntr=0.3,0.1

Type RM Length L Ch R = 1 ,26859   ,925,919.9,914.6
XS GIS Cut Line= 4
2192645.36847329484466.7727230762192738.84713665484725.213733546
2192832.32580002 484989.153488922192997.28814713485253.093244294
#Sta/Elev= 30
       0 3061.72    36.6 3054.28    53.6 3052.63   104.6  3039.2   249.3 3016.14
     262  3011.7   279.2  3012.9   300.3 3009.44   321.5 3007.77  333.843000.334
   338.4  2997.9   342.7 2997.27     436 2997.25   440.3 2997.97  443.763000.331
     453 3002.94   491.2 3002.05   508.2 3008.11   529.4 3011.85   554.8 3011.35
   566.4 3013.74     607 3018.04   676.7 3027.87     753 3036.32   767.1 3036.99
   781.3 3035.52   801.5 3035.49   833.8 3043.12   847.3 3043.81 866.082 3046.98
#Mann= 6 ,-1,0
       0      .1       0     210     .06       0  314.83      .1       0
  333.84    .045       0  443.76     .06       0  614.83      .1       0
Bank Sta=333.84,443.76
XS Rating Curve= 0 ,0
Exp/Cntr(USF)=0,0
Exp/Cntr=0.3,0.1

Type RM Length L Ch R = 1 ,25940   ,541,442,350.9
BEGIN DESCRIPTION:
structure xs 4
END DESCRIPTION:
XS GIS Cut Line= 4
2191760.07054381484780.201182582 2191892.0404215485099.128386993
2192002.01531957485346.5719076562192089.99523803485555.524213994
#Sta/Elev= 30
       0 3072.69    28.4 3067.78   117.9 3047.44   152.6 3041.66   178.5 3034.91
   230.5 3029.31   252.1 3024.82   303.7 3019.56   325.4 3015.57   346.8 3009.01
   374.1 3010.21   391.2 3008.95   404.3 3005.14  432.922999.723   448.1 2997.12
   535.6 2997.12  542.192999.723   546.8 3001.78   557.5 3002.87   570.6 3007.55
   595.3 3008.94   604.4 3011.74   619.6  3013.4   634.8 3020.27   657.8 3033.93
     673 3041.13   701.2 3049.91   740.3 3050.95   809.7 3058.56842.6539 3058.45
#Mann= 9 ,-1,0
       0      .1       0     320     .06       0  405.15     .07       0
  432.92    .045       0  542.19      .1       0  565.15     .06       0
  625.93      .1       0  725.93     .06       0  835.93      .1       0
Bank Sta=432.92,542.19
XS Rating Curve= 0 ,0
Exp/Cntr(USF)=0,0
Exp/Cntr=0.5,0.3

Type RM Length L Ch R = 1 ,25498   ,132.7,149.3,159
BEGIN DESCRIPTION:
strucure xs 3
END DESCRIPTION:
XS GIS Cut Line= 4
2190976.98827944485107.6106285342191400.92324089485623.149626881
2191954.80811515 485508.111999152192042.15149916485646.583217714
#Sta/Elev= 30
       0 3071.79    54.5 3054.48   105.8 3046.71   126.3 3039.18   167.7 3039.81
     292 3027.56   319.9 3017.41   352.9 3017.33     364 3011.88   378.5 3016.81
   447.4 3025.88   515.1 3021.71   594.5  3031.4   695.3 3033.65   744.3 3029.08
   793.3  3011.2   842.4 3008.98  867.692999.375  1001.7 2997.06 1008.342999.374
    1063 3013.35  1091.3 3032.05  1108.3 3038.88  1233.2  3044.7  1253.3 3051.77
  1273.2 3054.11  1325.7 3053.73  1357.4 3062.85  1385.9    3084 1396.88 3087.48
#Mann= 8 ,-1,0
       0      .1       0     440     .06       0     570     .05       0
     650     .07       0  857.46     .08       0  867.69    .045       0
 1008.34     .08       0 1157.46      .1       0
#XS Ineff= 2 , 0
             817 3040.81    1058         3040.81
Permanent Ineff=
       F       F
Bank Sta=867.69,1008.34
XS Rating Curve= 0 ,0
Exp/Cntr(USF)=0,0
Exp/Cntr=0.5,0.3

Type RM Length L Ch R = 1 ,25348   ,325.7,357.3,395.6
BEGIN DESCRIPTION:
structure xs 2
END DESCRIPTION:
XS GIS Cut Line= 4
2190819.34412292485165.1294423992191290.14626604485774.402804081
2191895.15897484485650.8438705932191965.45974734 485742.44790749
#Sta/Elev= 30
       0 3101.73   126.4 3058.35   207.3 3045.29   230.3 3029.19   252.8 3024.25
   333.7 3019.22   374.2 3022.54   409.5 3018.21   428.4 3021.17   505.1 3018.97
   536.7 3027.12   712.8 3037.95   947.6 3022.79   991.6 3013.28  1033.3 3011.76
 1070.22 2999.08  1078.2 2997.03 1157.33 2999.08  1172.1 3007.45  1208.9 3004.53
  1225.2 3009.18  1286.5 3054.93  1298.2 3060.06  1387.5 3062.49  1410.6 3080.56
  1446.9 3084.09  1461.2 3092.46  1466.1 3099.87  1478.3 3126.811502.951 3131.88
#Mann= 11 ,-1,0
       0      .1       0     610     .06       0  769.98     .03       0
  869.98     .06       0  939.98     .03       0  969.98     .07       0
 1069.98     .08       0 1070.22    .045       0 1157.33     .08       0
 1179.98     .06       0 1279.98      .1       0
#XS Ineff= 2 , 0
            1053 3040.81    1174         3040.81
Permanent Ineff=
       F       F
Bank Sta=1070.22,1157.33
XS Rating Curve= 0 ,0
Exp/Cntr(USF)=0,0
Exp/Cntr=0.5,0.3

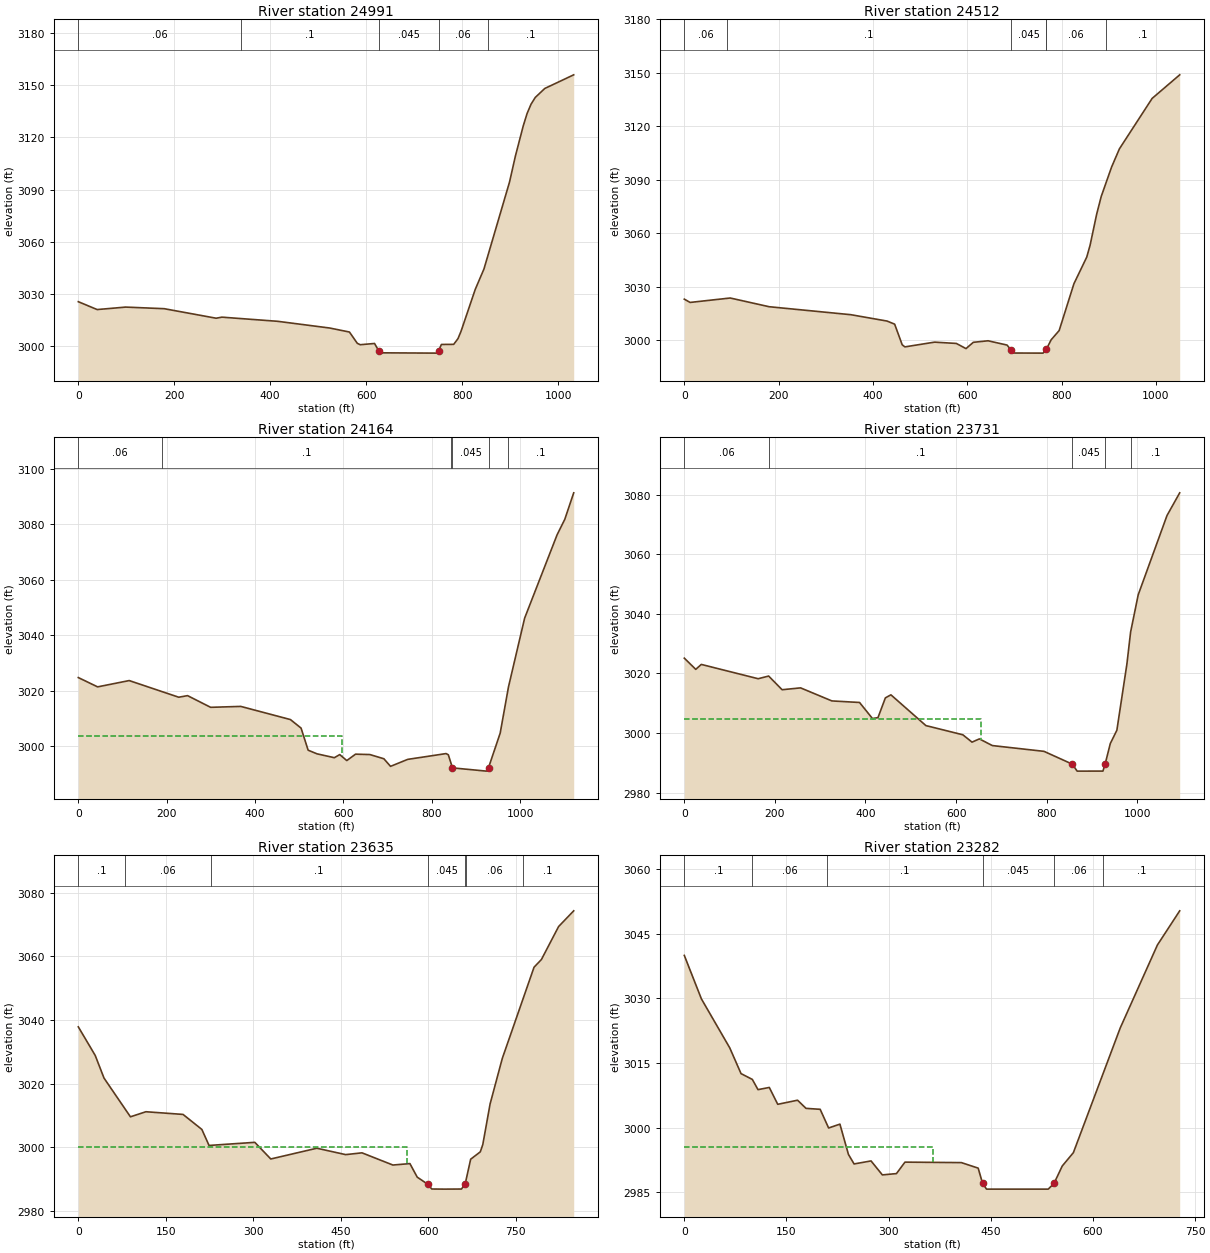
Type RM Length L Ch R = 1 ,24991   ,468.6,478.5,491.9
XS GIS Cut Line= 4
2190857.68999883485957.6108778742191407.31422021485998.087080224
2191639.51980211486098.2124228782191863.20407825486145.079604546
#Sta/Elev= 30
       0 3025.64    39.3 3021.12    98.8 3022.54     179 3021.62   287.3 3016.15
   299.3 3016.76   415.6 3014.37   523.9 3010.52   565.1 3008.22   581.5 3001.73
   587.6 3000.93   617.4 3001.64  626.232997.402   631.1 2996.27   748.1  2996.1
  750.862997.401   756.8 3001.08   782.4 3001.14   791.3 3004.41   797.6 3008.57
   827.3  3032.7   845.5 3044.45   898.7  3094.3   910.9 3109.17   927.3 3126.57
   935.4 3133.75   943.6 3139.07   952.3 3142.91   972.2  3148.11032.527 3155.94
#Mann= 5 ,-1,0
       0     .06       0     340      .1       0  626.23    .045       0
  750.86     .06       0  853.99      .1       0
Bank Sta=626.23,750.86
XS Rating Curve= 0 ,0
Exp/Cntr(USF)=0,0
Exp/Cntr=0.3,0.1

Type RM Length L Ch R = 1 ,24512   ,338.5,348,358.8
XS GIS Cut Line= 6
2190862.01880148485973.831957011 2191027.3320171486175.916923091
2191069.30861712 486256.001651392191194.05101558486365.952781291
2191488.26662491486600.9694625882191616.08621127486690.443173045
#Sta/Elev= 30
       0 3023.14    12.4  3021.3    97.3 3023.78     180 3018.89   353.3 3014.42
     430 3010.85     446 3009.12     462 2997.56   467.7 2996.38   530.7 2999.04
   576.8 2998.31   597.3 2995.42   612.7 2998.94     644  2999.8   684.3  2997.4
   692.4 2994.75   699.7 2992.94   760.7 2992.88767.50042994.933   777.7 3000.31
   794.8 3005.53   826.1 3031.78   853.3 3046.73   860.3 3053.27   874.5 3070.98
     884 3080.71   905.9 3097.16   922.6 3107.43   991.9 3135.67  1050.4 3148.91
#Mann= 6 ,-1,0
       0     .06       0      90      .1       0   692.4    .045       0
767.5004      .1       0  767.79     .06       0  894.35      .1       0
Bank Sta=692.4,767.5004
XS Rating Curve= 0 ,0
Exp/Cntr(USF)=0,0
Exp/Cntr=0.3,0.1

Type RM Length L Ch R = 1 ,24164   ,390.8,433.8,477.2
XS GIS Cut Line= 6
2190836.94979279485959.6006810832190897.23196671486144.692910997
2190925.85397779 486493.361046052191076.64541575486691.153331618
2191197.43492486486836.1007425582191269.90863033486955.164687259
#Sta/Elev= 30
       0  3024.8    43.7 3021.45   115.2 3023.72   227.3 3017.72   247.3 3018.29
   299.5 3014.08   367.7 3014.41   480.1 3009.67   504.2  3006.6   520.2 2998.64
   540.3 2997.32   579.5 2995.93   591.7 2997.04   607.7  2994.9   627.5  2997.2
     660 2997.06   691.6 2995.55   706.7 2992.81   745.5 2995.32   832.3 2997.41
   837.5 2996.99846.89852992.263   923.7 2991.09928.55852992.362   954.9 3004.79
   973.7 3021.46  1010.2  3046.2  1083.6 3076.21  1101.1 3081.82  1121.3 3091.37
#Mann= 6 ,-1,0
       0     .06       0     190      .1       0  843.22     .06       0
846.8985    .045       0928.5585     .06       0  973.22      .1       0
#XS Ineff= 2 , 0
          596.04 3003.64
Permanent Ineff=
       F       F
Bank Sta=846.8985,928.5585
XS Rating Curve= 0 ,0
Exp/Cntr(USF)=0,0
Exp/Cntr=0.3,0.1

Type RM Length L Ch R = 1 ,23731   ,90.8,95.8,100.3
XS GIS Cut Line= 4
2190831.63591308485956.198973558 2190861.3730137486139.884611794
2190711.82409765486929.8096555422190677.31280933487027.591639112
#Sta/Elev= 30
       0  3025.1    25.3 3021.33    37.5 3022.99   163.1 3018.19   186.2 3019.09
   215.9  3014.5   256.7 3015.12   325.8 3010.74   386.9 3010.22   415.4 3004.83
   427.6 3005.14   443.9 3011.76   456.1 3012.79   533.4 3002.46   614.9 2999.38
   635.2 2996.91   651.5    2998     680 2995.76   794.1 2993.82  856.74 2989.51
   867.3 2987.18   924.2 2987.19  929.042989.508   940.5 2996.44     955  3000.9
   977.2 3023.17   985.3 3033.83  1002.1 3046.35  1065.7 3072.971093.727 3080.58
#Mann= 5 ,-1,0
       0     .06       0  186.08      .1       0  856.74    .045       0
  929.04     .06       0  986.08      .1       0
#XS Ineff= 2 , 0
          654.18 3004.55
Permanent Ineff=
       F       F
Bank Sta=856.74,929.04
XS Rating Curve= 0 ,0
Exp/Cntr(USF)=0,0
Exp/Cntr=0.3,0.1

Type RM Length L Ch R = 1 ,23635   ,356,352.9,351.5
XS GIS Cut Line= 6
2190472.10091329486238.8139678812190532.95182561486372.367999185
2190687.77088557486587.0330823332190670.22127216486698.964478803
2190614.83278473486888.5635319142190576.48690882487009.992138962
#Sta/Elev= 30
       0 3037.83      29 3028.85    44.1 3021.73    89.4 3009.57   115.9 3011.16
   179.6 3010.32   211.9  3005.6   224.2 3000.57   302.7 3001.55   330.1 2996.32
   409.1  2999.7   458.5 2997.69   486.5 2998.25   539.5 2994.42   568.7 2994.87
   581.2 2990.62   599.1 2988.41   606.2 2986.89   627.1 2986.85   657.2 2986.88
   663.6 2988.58   672.9 2996.25   689.4 2998.56   693.7 3000.86   706.2  3013.6
   727.1  3027.9   781.6 3056.57   794.2 3058.98   823.7 3069.34   849.6 3074.28
#Mann= 7 ,-1,0
       0      .1       0      80     .06       0  226.76      .1       0
   599.1    .045       0   663.6      .1       0  664.73     .06       0
  762.26      .1       0
#XS Ineff= 2 , 0
          563.38  3000.1
Permanent Ineff=
       F       F
Bank Sta=599.1,663.6
XS Rating Curve= 0 ,0
Exp/Cntr(USF)=0,0
Exp/Cntr=0.3,0.1

Type RM Length L Ch R = 1 ,23282   ,379.9,374.6,369.6
XS GIS Cut Line= 4
2190426.83536096486236.9409083942190324.26408795486607.775510817
2190269.03340249486833.9583179692190237.47301079486939.159623621
#Sta/Elev= 30
       0 3039.92    25.1 3029.84    66.7 3018.49    83.3 3012.51    99.9 3011.16
   108.2 3008.79   124.8  3009.3   137.2 3005.39   166.3 3006.34   178.7 3004.45
   199.5 3004.23   211.9  2999.9   228.5 3000.79     241 2993.77   249.3 2991.56
   274.2 2992.26   290.8 2989.02   311.5 2989.32     324 2991.98   406.8 2991.87
   431.5 2990.59  437.992987.049   443.8 2985.72   534.4 2985.72  542.862987.046
     555 2991.09   571.3 2994.18   640.1  3023.1   694.7 3042.34727.4204 3050.26
#Mann= 6 ,-1,0
       0      .1       0     100     .06       0     210      .1       0
  437.99    .045       0  542.86     .06       0  614.76      .1       0
#XS Ineff= 2 , 0
          365.64 2995.52
Permanent Ineff=
       F       F
Bank Sta=437.99,542.86
XS Rating Curve= 0 ,0
Exp/Cntr(USF)=0,0
Exp/Cntr=0.3,0.1

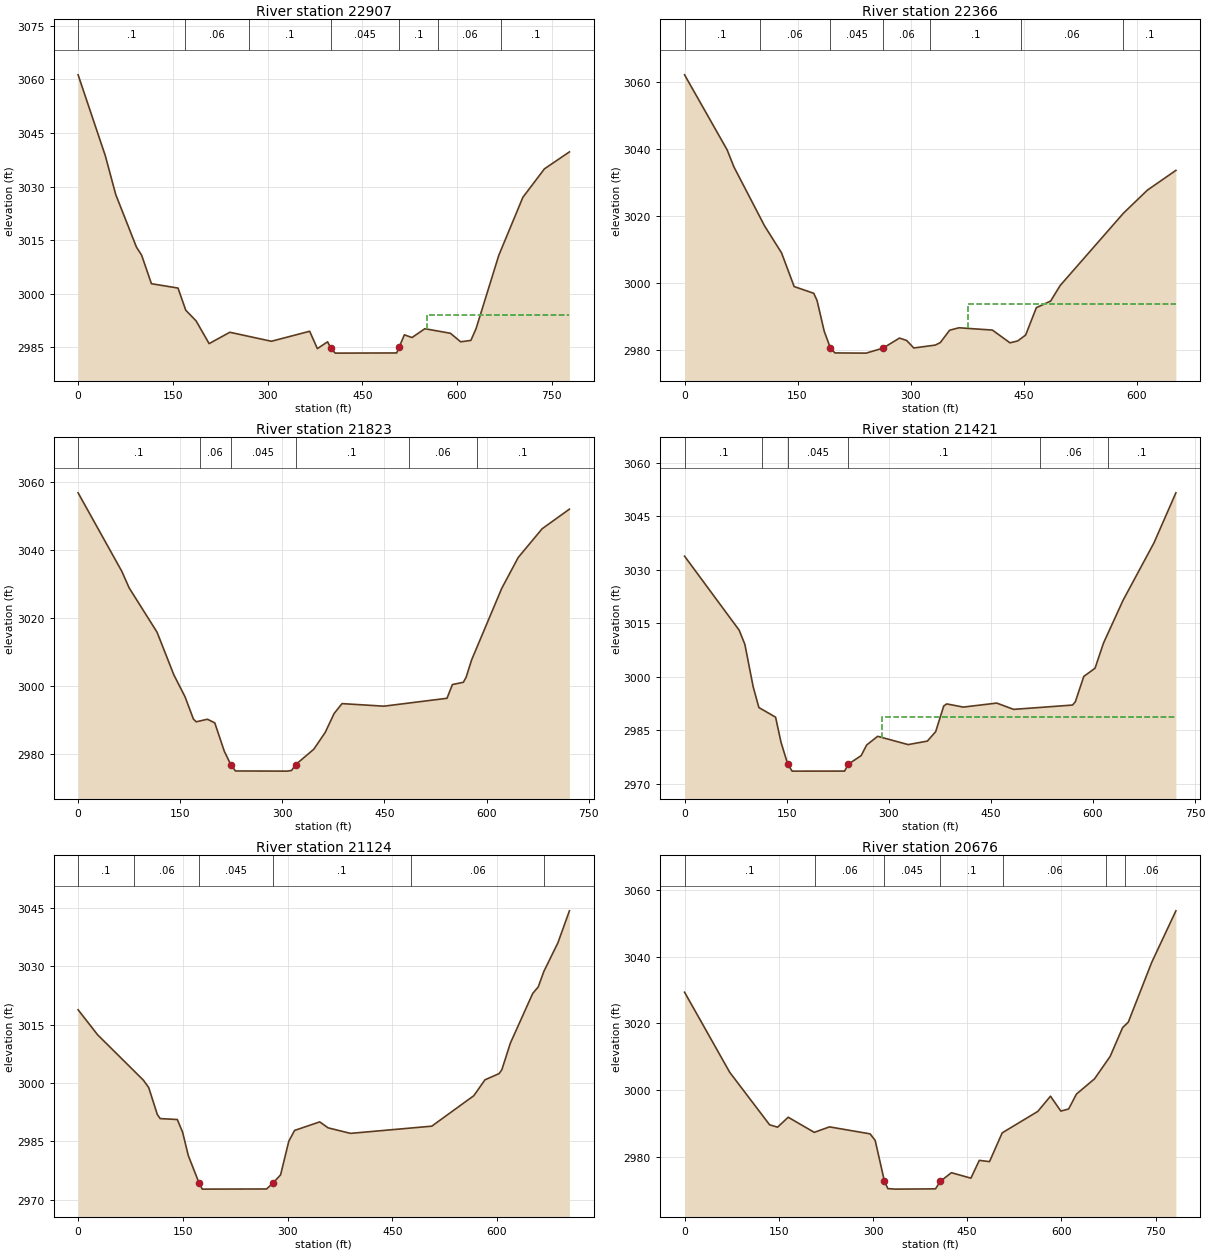
Type RM Length L Ch R = 1 ,22907   ,592.5,541.8,476.9
XS GIS Cut Line= 4
2190029.70043213486171.1900923622189961.31958346486463.123715546
2189908.71893063486789.2477630672189895.56876742486936.529590979
#Sta/Elev= 30
       0 3061.27    43.1 3038.62    59.6 3027.77    92.4 3013.05   100.6  3010.8
   116.1 3002.81   158.2 3001.59   170.5 2995.39   186.9 2992.39   207.5 2986.04
   240.3 2989.22   306.1  2986.7   366.7  2989.5   378.9 2984.64   395.1 2986.55
   400.3 2984.75   407.2 2983.38   504.5 2983.43  508.282985.008   516.7  2988.5
   528.8 2987.74   549.1 2990.21   589.6 2988.94   605.8 2986.55     622 2986.94
   630.2 2990.23   666.2 3010.75   704.3 3026.98   738.5 3034.96778.0418  3039.7
#Mann= 7 ,-1,0
       0      .1       0     170     .06       0     270      .1       0
   400.3    .045       0  508.28      .1       0  569.84     .06       0
  670.17      .1       0
#XS Ineff= 2 , 0
                          552.42         2993.94
Permanent Ineff=
       F       F
Bank Sta=400.3,508.28
XS Rating Curve= 0 ,0
Exp/Cntr(USF)=0,0
Exp/Cntr=0.3,0.1

Type RM Length L Ch R = 1 ,22366   ,554.1,542.2,525.3
XS GIS Cut Line= 4
 2189238.0606071486586.735249687 2189359.0421086486649.856033078
2189624.67540537486820.8081547622189732.50674366486989.130243805
#Sta/Elev= 30
       0 3062.29    56.5 3039.86    65.5 3034.77   106.2 3017.12   128.7 3009.08
   145.5 2998.98   171.5 2996.97   175.9  2994.8   185.4 2985.62  193.692980.563
   199.6 2979.14     241 2979.08  263.392980.565   285.3 2983.58   294.8 2982.87
   304.3 2980.62   332.8 2981.48   339.4 2982.22   351.9 2985.93   364.3 2986.66
   408.7 2985.97     432 2982.16   442.2 2982.72   452.8 2984.49     467 2992.67
     486 2994.65   498.6 2999.29   582.5 3020.89   614.4 3027.81652.2464 3033.72
#Mann= 7 ,-1,0
       0      .1       0     100     .06       0  193.69    .045       0
  263.39     .06       0  326.46      .1       0  446.46     .06       0
  582.35      .1       0
#XS Ineff= 2 , 0
                          376.21         2993.82
Permanent Ineff=
       F       F
Bank Sta=193.69,263.39
XS Rating Curve= 0 ,0
Exp/Cntr(USF)=0,0
Exp/Cntr=0.3,0.1

Type RM Length L Ch R = 1 ,21823   ,406.2,401.9,398.4
XS GIS Cut Line= 4
2189051.32828957 487160.082365492189195.98008484487194.272789826
2189474.76354481  487262.65363852189758.80707007487296.844062837
#Sta/Elev= 30
       0 3056.68    64.3 3033.64    74.9 3028.85     116 3015.82   140.6 3003.35
   157.1 2996.89   169.4 2990.37   173.5 2989.56     190 2990.31   200.8 2989.25
   214.7 2980.98  224.362976.971   231.2 2975.15   306.6  2975.1   313.6 2975.28
  319.462976.972   346.3 2981.53     363 2986.44   376.1 2991.99   387.7 2994.89
   449.2 2994.14   541.9 2996.45   549.9 3000.48     566 3001.15   570.1 3002.65
   578.1 3007.71   622.4  3028.7   646.6 3037.74   681.7 3046.15721.7787 3051.89
#Mann= 6 ,-1,0
       0      .1       0  178.64     .06       0  224.36    .045       0
  319.46      .1       0  485.68     .06       0  585.68      .1       0
Bank Sta=224.36,319.46
XS Rating Curve= 0 ,0
Exp/Cntr(USF)=0,0
Exp/Cntr=0.3,0.1

Type RM Length L Ch R = 1 ,21421   ,303.6,297.3,290.6
XS GIS Cut Line= 4
2189014.50783259487567.7374248912189124.96920352487596.667783945
2189437.94308784487649.2684367712189719.35658045487720.279318086
#Sta/Elev= 30
       0  3033.8    80.3 3013.06    88.6 3009.09   100.8 2997.23   109.2 2991.42
   133.7 2988.73   141.7 2981.69  151.55 2975.57     158 2973.62   235.1 2973.63
  240.62 2975.57   259.4 2977.96   267.5 2980.94   283.7 2983.37   328.4 2981.05
   356.7 2982.03   368.9 2984.67   380.7 2991.84   385.1 2992.44   409.5 2991.55
   458.6 2992.67   483.4 2990.91     570 2992.12   574.1 2993.06   586.5 3000.14
     603 3002.43   615.4 3009.45   644.1 3021.42   689.6 3037.53721.7849 3051.54
#Mann= 6 ,-1,0
       0      .1       0  114.19     .06       0  151.55    .045       0
  240.62      .1       0  521.55     .06       0  621.55      .1       0
#XS Ineff= 2 , 0
                          290.75         2988.79
Permanent Ineff=
       F       F
Bank Sta=151.55,240.62
XS Rating Curve= 0 ,0
Exp/Cntr(USF)=0,0
Exp/Cntr=0.3,0.1

Type RM Length L Ch R = 1 ,21124   ,442.7,448,455.5
XS GIS Cut Line= 4
2188952.71830029487875.3141503142189086.20418194487900.568236033
2189356.78367179487914.9991421582189652.61724735487940.253227877
#Sta/Elev= 30
       0 3018.79    27.9 3012.37    93.6 3000.69   101.2 2998.78   113.4 2991.92
   117.5 2990.84   142.1  2990.6   149.7 2987.33   157.9 2981.31  173.452974.216
   177.9 2972.72     270 2972.76  278.752974.215     290 2976.38   301.8 2985.03
   310.1  2987.8   346.1 2989.99   358.1 2988.46   390.2 2987.04   506.6 2988.89
   566.8 2996.72   582.8  3000.8   602.9 3002.38   606.9 3003.36   619.1  3010.2
   651.1 3022.96   659.1 3024.67   667.1 3028.63   687.2 3035.97703.7274  3044.2
#Mann= 6 ,-1,0
       0      .1       0      80     .06       0  173.45    .045       0
  278.75      .1       0  476.82     .06       0  666.82      .1       0
Bank Sta=173.45,278.75
XS Rating Curve= 0 ,0
Exp/Cntr(USF)=0,0
Exp/Cntr=0.3,0.1

Type RM Length L Ch R = 1 ,20676   ,438.9,471.1,496.3
XS GIS Cut Line= 4
2188736.25470841488257.7331626292188913.03330844 488319.06451366
2189302.66777382 488376.788138162189497.48500651488427.296309598
#Sta/Elev= 30
       0 3029.33    71.9 3005.39   135.4  2989.7   148.1 2988.99     165 2991.96
   206.5 2987.44   230.7 2989.08   295.4 2986.99   303.5 2985.04  318.282972.779
   323.7 2970.62   335.5 2970.47   399.5 2970.55  407.142972.779   424.8 2975.38
   455.9 2973.75   469.3 2979.07   485.5 2978.69   505.7 2987.29   562.3 2993.69
   582.6 2998.25   599.1  2993.8   611.5 2994.42   623.9 2998.87   652.8 3003.46
   677.6 3010.14   697.4 3018.74   706.5 3020.39   743.7 3038.22782.2607 3053.66
#Mann= 7 ,-1,0
       0      .1       0  207.12     .06       0  318.28    .045       0
  407.14      .1       0  507.12     .06       0     671      .1       0
     701     .06       0
Bank Sta=318.28,407.14
XS Rating Curve= 0 ,0
Exp/Cntr(USF)=0,0
Exp/Cntr=0.3,0.1

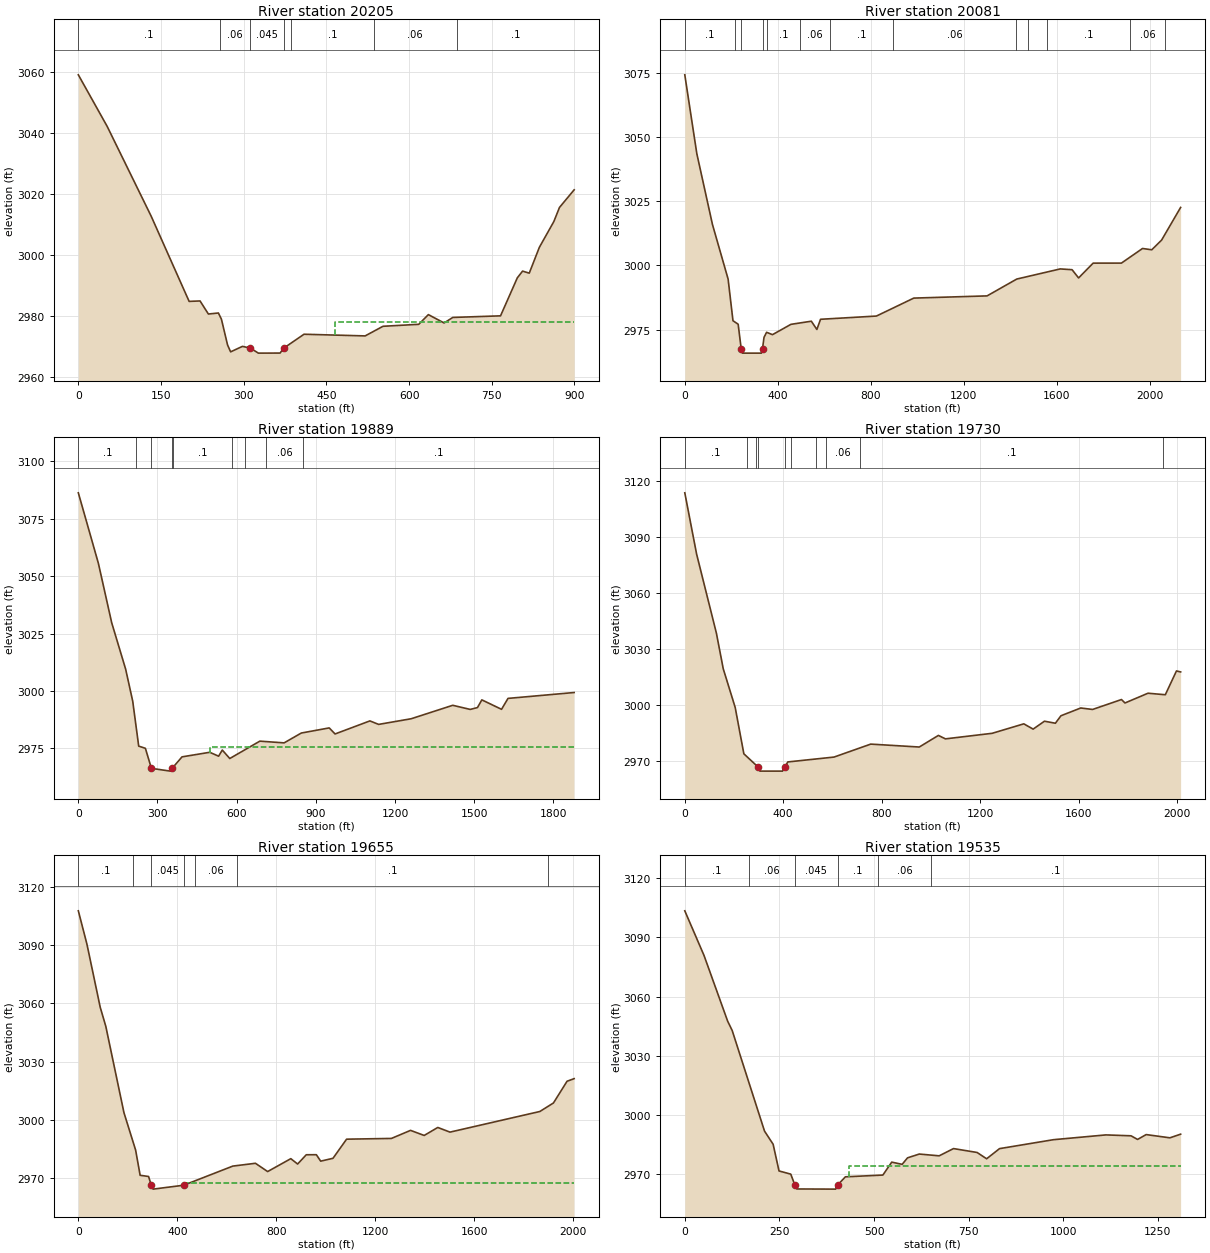
Type RM Length L Ch R = 1 ,20205   ,124.5,124.1,125.2
XS GIS Cut Line= 4
2188624.41518594488553.566738193 2188804.8015125488672.621713725
2189078.98872888488935.9857505082189317.09867994489123.587530134
#Sta/Elev= 30
       0 3059.17    52.4 3042.22   132.4 3012.67     201  2984.8   220.8 2984.95
   235.9 2980.66   254.1 2980.99   259.6 2978.95   270.7  2970.5   276.3 2968.24
   297.8 2970.04   312.3 2969.45   326.6 2967.82     366 2967.84  372.642969.456
   409.4 2974.02   520.3 2973.47   552.7 2976.63   617.6 2977.28     635 2980.46
   663.5 2977.72   679.3 2979.53   765.9 2980.06   796.4 2992.55   805.9 2994.74
     818 2994.07   836.3 3002.54   862.6 3011.01   872.8 3015.63899.4507 3021.43
#Mann= 7 ,-1,0
       0      .1       0  256.13     .06       0   312.3    .045       0
  372.64     .06       0  386.13      .1       0  536.13     .06       0
  686.32      .1       0
#XS Ineff= 2 , 0
                          465.36         2978.19
Permanent Ineff=
       F       F
Bank Sta=312.3,372.64
XS Rating Curve= 0 ,0
Exp/Cntr(USF)=0,0
Exp/Cntr=0.3,0.1

Type RM Length L Ch R = 1 ,20081   ,192,191.8,189.5
XS GIS Cut Line= 4
2188581.12246757488676.2294402562188743.47016147488784.461236194
2188959.93375335488993.7093750082190058.97489219490205.782062515
#Sta/Elev= 30
       0 3074.29    51.7 3043.57     119 3015.94   186.3 2994.67   207.2 2978.44
   229.5 2977.08  242.452967.565   247.9 2965.81   329.6 2965.81  334.24 2967.56
   340.7 2971.96   351.7 2973.93   377.2 2973.01   456.4 2977.03   544.2 2978.25
     568 2975.04   583.8    2979   824.1 2980.26   984.8 2987.26    1300 2988.12
  1427.6 2994.68  1614.5 2998.63  1665.5 2998.33  1693.5 2995.12  1756.1 3000.89
  1877.7  3000.9  1968.5  3006.6  2008.2 3006.09  2050.5 3009.87  2132.3  3022.6
#Mann= 13 ,-1,0
       0      .1       0  215.12     .06       0  242.45    .045       0
  334.24     .07       0  355.12      .1       0  495.12     .06       0
  626.18      .1       0  896.18     .06       0 1426.18      .1       0
 1476.18     .06       0 1556.18      .1       0 1916.18     .06       0
 2066.18      .1       0
Bank Sta=242.45,334.24
XS Rating Curve= 0 ,0
Exp/Cntr(USF)=0,0
Exp/Cntr=0.3,0.1

Type RM Length L Ch R = 1 ,19889   ,157.8,159.3,162.9
BEGIN DESCRIPTION:
structure xs 4
END DESCRIPTION:
XS GIS Cut Line= 3
2188476.94523627488788.9240672732188867.46081421489164.024556605
 2189787.2277675490135.175138576
#Sta/Elev= 30
       0 3086.26      76 3055.57   126.5 3029.69   179.4 3009.47   206.2  2995.5
   228.8 2975.99   254.1 2975.05   276.9 2966.33   348.4 2965.11  356.08  2966.4
     393 2971.32   498.1 2973.31   531.6 2971.61   545.6 2974.29   573.9  2970.6
   687.9 2978.16     780 2977.41     845 2981.69   950.8 2983.92     973 2981.29
    1105 2986.97  1138.1 2985.45  1261.5 2987.91    1419 2993.77  1485.2 2991.97
  1512.7 2992.78  1529.2 2996.13  1603.9 2992.02  1628.4 2996.77  1879.1 2999.33
#Mann= 9 ,-1,0
       0      .1       0     220     .06       0   276.9    .045       0
  356.08     .07       0     360      .1       0  581.48     .06       0
  631.48      .1       0  711.48     .06       0  851.48      .1       0
#XS Ineff= 2 , 0
                          500.27         2975.65
Permanent Ineff=
       F       F
Bank Sta=276.9,356.08
XS Rating Curve= 0 ,0
Exp/Cntr(USF)=0,0
Exp/Cntr=0.5,0.3

Type RM Length L Ch R = 1 ,19730   ,76.9,74.5,73.6
BEGIN DESCRIPTION:
structure xs 3
END DESCRIPTION:
XS GIS Cut Line= 4
2188348.83873301488891.1754816862188526.65626931 489053.85961064
2188704.47380561489231.6771469372189767.59567156 490321.28247574
#Sta/Elev= 30
       0 3113.61    47.9 3080.86   128.4 3038.44   156.3 3019.32   204.8 2998.65
     240 2973.81  296.99 2966.83   305.4 2964.54   397.2 2964.53  407.09 2966.83
   418.5 2969.45   606.5 2972.06   755.5    2979   952.8 2977.44  1030.5 2983.66
  1059.1 2981.81    1249 2984.79  1377.6 2989.86  1415.5 2987.03  1461.4 2991.27
  1505.9 2990.19  1528.5 2994.19    1609 2998.35    1657 2997.56  1774.4 3002.88
  1788.8 3001.04  1882.2 3006.26  1952.6 3005.45  1997.9 3018.18  2014.8 3017.67
#Mann= 10 ,-1,0
       0      .1       0  251.01     .06       0  291.01     .07       0
  296.99    .045       0  407.09      .1       0  431.01     .06       0
  532.48     .07       0  572.48     .06       0  712.48      .1       0
 1942.48     .06       0
#XS Ineff= 2 , 0
             276 2968.43     428         2968.43
Permanent Ineff=
       F       F
Bank Sta=296.99,407.09
XS Rating Curve= 0 ,0
Exp/Cntr(USF)=0,0
Exp/Cntr=0.5,0.3

Type RM Length L Ch R = 1 ,19655   ,117.9,120.2,123
BEGIN DESCRIPTION:
structure xs 2
END DESCRIPTION:
XS GIS Cut Line= 4
2188292.08845547488944.1424073922188485.03939911 489121.95994369
2188659.07358357489284.6440726432189691.92863483490378.032753282
#Sta/Elev= 30
       0  3107.8    34.8  3090.6    88.5 3058.05   111.2 3048.15   184.5 3003.65
   231.7 2984.35   249.9 2971.37   283.9 2970.75   295.2 2966.19   302.3 2964.23
  426.39 2966.25   624.6 2976.11     716 2977.56   765.5 2973.29     859 2979.94
   886.7 2977.18   921.6 2981.96   962.4 2981.98   979.9 2978.66  1029.6 2980.13
  1084.6    2990  1265.8 2990.38  1343.2 2994.54  1398.3 2991.92  1453.3 2996.04
  1502.8 2993.64    1866 3004.28    1921 3008.68    1976 3019.88  2004.7 3021.23
#Mann= 7 ,-1,0
       0      .1       0     220     .07       0   295.2    .045       0
  426.39     .07       0  472.39     .06       0  640.62      .1       0
 1900.62     .06       0
#XS Ineff= 2 , 0
           288.7  2967.6  431.76          2967.6
Permanent Ineff=
       F       F
Bank Sta=295.2,426.39
XS Rating Curve= 0 ,0
Exp/Cntr(USF)=0,0
Exp/Cntr=0.5,0.3

Type RM Length L Ch R = 1 ,19535   ,256.5,254.8,256.9
XS GIS Cut Line= 2
 2188220.0270929489025.2887591812189152.63995336489945.055712476
#Sta/Elev= 30
       0 3103.52    50.8 3080.88   113.2 3047.57   125.2 3042.82   210.6 2991.81
   233.4 2985.11   248.9 2971.59     280 2969.97  290.57 2964.54   296.1 2962.45
   398.6 2962.37   404.7 2964.65   424.3 2968.61   523.3  2969.5   546.7 2976.06
   574.2 2974.94   588.4 2978.23   619.5 2980.16     672 2979.26     710 2982.93
   772.2 2980.96   797.4 2977.76   831.5 2982.91   973.9 2987.44  1112.6 2989.87
    1179 2989.41  1196.1 2987.57  1218.9 2990.03  1281.6 2988.39  1309.9 2990.24
#Mann= 6 ,-1,0
       0      .1       0     170     .06       0  290.57    .045       0
   404.7      .1       0     510     .06       0     650      .1       0
#XS Ineff= 2 , 0
                          433.01         2974.07
Permanent Ineff=
       F       F
Bank Sta=290.57,404.7
XS Rating Curve= 0 ,0
Exp/Cntr(USF)=0,0
Exp/Cntr=0.3,0.1

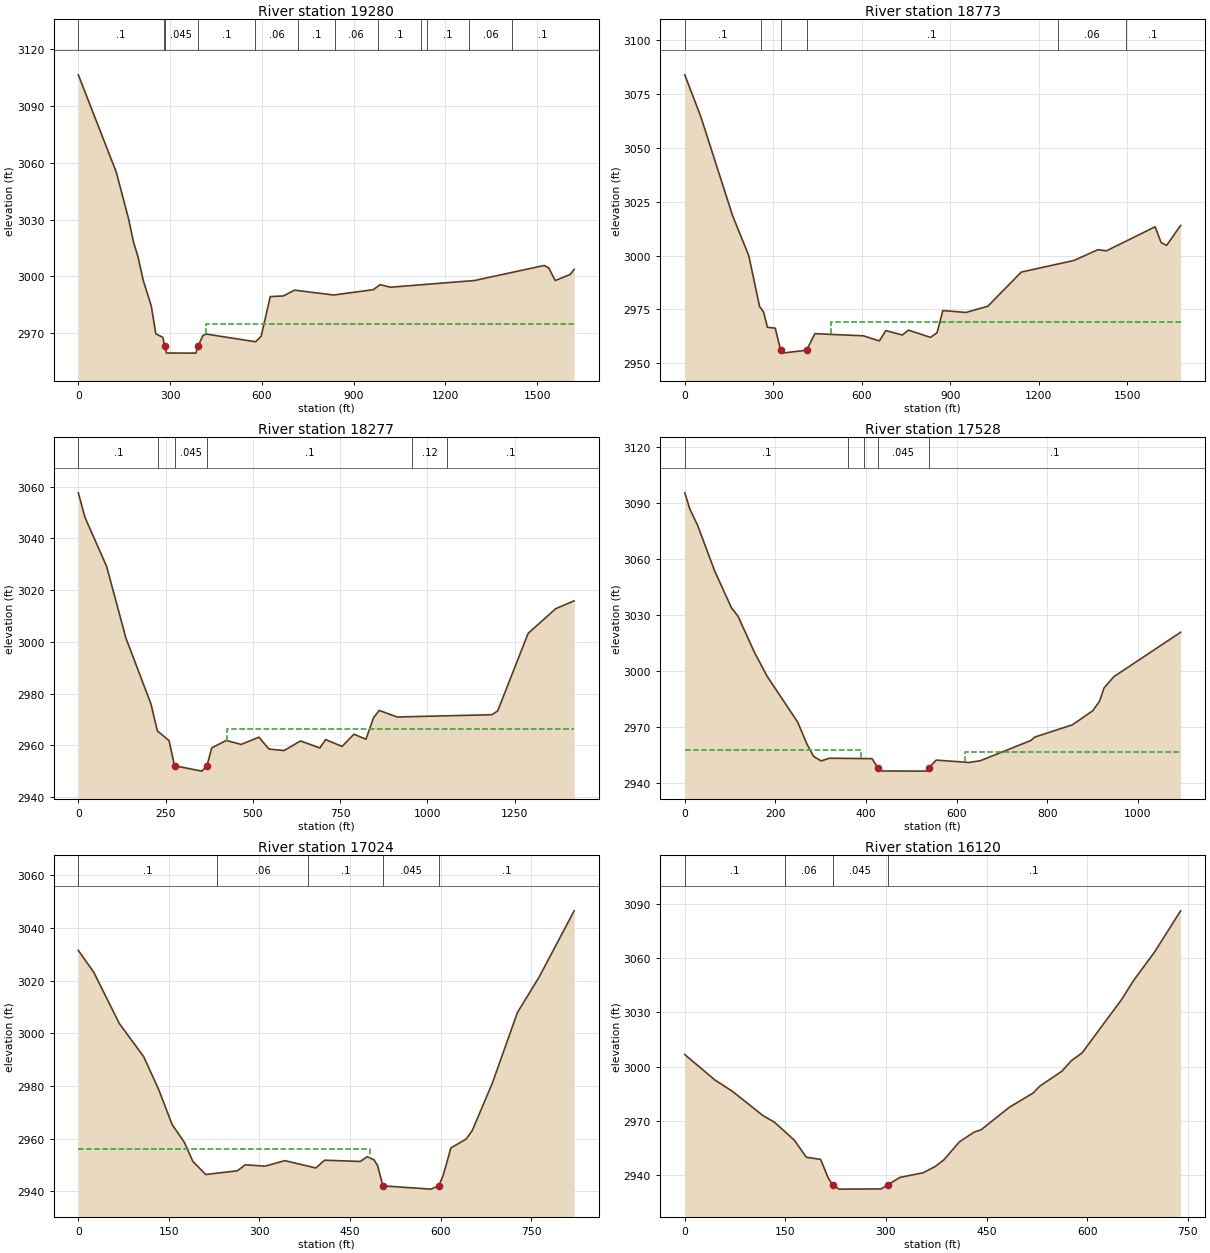
Type RM Length L Ch R = 1 ,19280   ,526.9,507.3,490.3
XS GIS Cut Line= 4
2188019.68712327 489190.060276742188178.58790039489341.394350185
2188363.97214036489522.9952383192189173.60943329490328.849179413
#Sta/Elev= 30
       0 3106.48   124.2 3055.02   163.8 3030.72   180.8 3017.89   194.9 3010.52
   211.9 2998.09   238.5 2984.41   253.4 2969.65   276.3 2967.78   282.6 2963.02
   288.3 2959.52   384.5 2959.46   391.1 2963.05   407.1 2968.69   417.6 2969.54
   579.6 2965.47   597.7 2968.32   627.7 2989.33   670.1 2989.66   706.9 2992.73
   834.8 2990.16   964.6 2992.98   986.7 2995.61    1021 2994.28  1295.2 2997.81
  1523.3 3005.77  1538.5 3004.42  1559.4 2997.82    1608    3001  1621.3  3003.7
#Mann= 12 ,-1,0
       0      .1       0  279.43     .06       0   282.6    .045       0
   391.1      .1       0  578.95     .06       0  718.95      .1       0
  838.95     .06       0  978.95      .1       0 1118.95     .06       0
 1138.95      .1       0 1278.95     .06       0 1418.95      .1       0
#XS Ineff= 2 , 0
                          418.28         2974.91
Permanent Ineff=
       F       F
Bank Sta=282.6,391.1
XS Rating Curve= 0 ,0
Exp/Cntr(USF)=0,0
Exp/Cntr=0.3,0.1

Type RM Length L Ch R = 1 ,18773   ,504.4,496.5,489.5
XS GIS Cut Line= 4
2187617.85948372489643.100150637 2187881.2235205489787.409211888
2188487.32157775490083.2427874522189086.20418194490458.446346704
#Sta/Elev= 30
       0 3083.83    54.3 3064.42     162 3018.55     217 2999.94   253.5 2976.39
   267.2  2973.8   280.2 2966.72   306.8  2966.3  325.132956.089   330.3 2954.73
  412.912956.088   441.1 2963.75   605.9 2962.76   659.7 2960.39   681.9  2965.2
   737.6 2963.13   758.5  2965.4   833.3 2962.03   855.5  2964.2   875.1 2974.49
   953.4 2973.59  1027.7 2976.49    1141 2992.32  1320.3 2997.73  1400.5 3002.69
  1430.4 3002.21  1594.9 3013.34  1615.2 3006.06  1633.9 3004.721681.461 3013.93
#Mann= 6 ,-1,0
       0      .1       0     260     .06       0  325.13    .045       0
  412.91      .1       0 1264.75     .06       0 1494.75      .1       0
#XS Ineff= 2 , 0
                          495.59         2969.33
Permanent Ineff=
       F       F
Bank Sta=325.13,412.91
XS Rating Curve= 0 ,0
Exp/Cntr(USF)=0,0
Exp/Cntr=0.3,0.1

Type RM Length L Ch R = 1 ,18277   ,741.5,748.9,756.8
XS GIS Cut Line= 5
2187433.86543062490180.6514037962187635.89811637490234.767301765
2187899.26215315490321.3527385162188523.39884306490548.639509986
2188783.15515332490620.794040611
#Sta/Elev= 30
       0  3057.6      19 3048.13    81.1 3029.14   136.2 3001.52   208.1 2976.01
   226.3 2965.62     260 2961.82  275.472952.128   353.9 2950.06  368.562952.133
   382.1 2959.04   423.6 2961.92   466.3 2960.37   517.2 2963.17   546.3 2958.57
   589.5 2958.02   636.4 2961.73   691.7 2959.01   708.5 2962.24   755.3  2959.6
   789.5 2964.34   823.7 2962.36   845.8 2970.75     862 2973.52   913.1 2970.98
  1184.6 2971.86  1201.2 2973.33  1288.4 3003.29  1367.3 3012.831420.212 3015.86
#Mann= 6 ,-1,0
       0      .1       0  229.15     .06       0  275.47    .045       0
  368.56      .1       0  956.39     .12       0 1056.39      .1       0
#XS Ineff= 2 , 0
                          424.67         2966.18
Permanent Ineff=
       F       F
Bank Sta=275.47,368.56
XS Rating Curve= 0 ,0
Exp/Cntr(USF)=0,0
Exp/Cntr=0.3,0.1

Type RM Length L Ch R = 1 ,17528   ,480.5,503.2,524.3
XS GIS Cut Line= 4
2187206.57865915490783.141734518 2187524.0585939490963.528061082
2187830.71534906491097.0139427392188148.19528381491331.516167272
#Sta/Elev= 30
       0 3095.67      11 3087.07    28.4 3078.17    66.2 3053.62     103 3034.03
   117.5 3029.52   153.7 3010.17   181.6 2997.38   249.1 2972.79   269.6 2961.01
   284.3 2954.41   300.9 2951.98   319.3 2953.41   413.3 2953.19  426.352948.146
   435.1 2946.58   531.1  2946.5   535.4 2946.59  538.272948.146   554.9 2952.41
     627 2951.14   652.2 2952.07   763.7 2962.92   772.3 2964.73   855.6 2971.34
   900.3 2978.85   915.2 2983.91   925.2 2991.02   946.7 2997.081094.293 3020.94
#Mann= 5 ,-1,0
       0      .1       0     360     .06       0  395.15     .07       0
  426.35    .045       0  538.27      .1       0
#XS Ineff= 2 , 0
           388.9 2958.03  617.97         2956.96
Permanent Ineff=
       F       F
Bank Sta=426.35,538.27
XS Rating Curve= 0 ,0
Exp/Cntr(USF)=0,0
Exp/Cntr=0.3,0.1

Type RM Length L Ch R = 1 ,17024   ,888,904.3,906.9
XS GIS Cut Line= 4
2187098.34686321491078.9753100832187397.78816531491400.062971366
 2187534.8817735491547.9797591482187643.11356943491692.288820399
#Sta/Elev= 30
       0 3031.43    25.5 3023.17    67.9 3003.68   108.2 2991.15     133 2978.69
   155.2 2965.44   175.5 2958.65   189.6  2951.4   210.9 2946.42   263.2 2947.82
   276.5 2950.09   309.3 2949.59   342.1 2951.67   393.4  2948.9   407.8 2951.84
     467 2951.37   478.3 2953.16   489.7 2951.97   495.5 2949.86  504.45 2942.11
   583.8 2940.87  596.842942.107   604.2 2946.07     617 2956.49   642.2 2959.86
   652.2 2963.01   685.4 2980.94   727.2 3007.87   762.9 3021.23821.1115 3046.44
#Mann= 5 ,-1,0
       0      .1       0     230     .06       0     380      .1       0
  504.45    .045       0  596.84      .1       0
#XS Ineff= 2 , 0
          482.38 2956.18
Permanent Ineff=
       F       F
Bank Sta=504.45,596.84
XS Rating Curve= 0 ,0
Exp/Cntr(USF)=0,0
Exp/Cntr=0.3,0.1

Type RM Length L Ch R = 1 ,16120   ,664.1,659.9,653.7
XS GIS Cut Line= 4
2186488.64107943491533.5488530232186582.44196924491659.819281617
2186733.96648355491876.2828734942186867.45236521492164.900995995
#Sta/Elev= 30
       0 3006.65    45.1 2992.55    70.9 2986.39   116.6 2972.92   133.8 2969.24
   163.8 2959.15   181.2 2949.89   202.6 2948.69   214.1 2938.26   220.72934.552
   230.1 2932.25   292.8 2932.36  302.382934.554   320.7 2938.72   355.6  2941.3
   373.8 2944.84   386.4 2948.43   409.4 2958.33   431.3 2963.74   441.9 2965.07
   484.1 2977.53   519.5  2985.4   529.3 2989.16   562.5 2997.47   576.8 3003.37
   592.6  3007.6   651.7 3037.21   669.3 3047.62   700.2 3063.12 739.518 3086.16
#Mann= 4 ,-1,0
       0      .1       0     150     .06       0   220.7    .045       0
  302.38      .1       0
Bank Sta=220.7,302.38
XS Rating Curve= 0 ,0
Exp/Cntr(USF)=0,0
Exp/Cntr=0.3,0.1