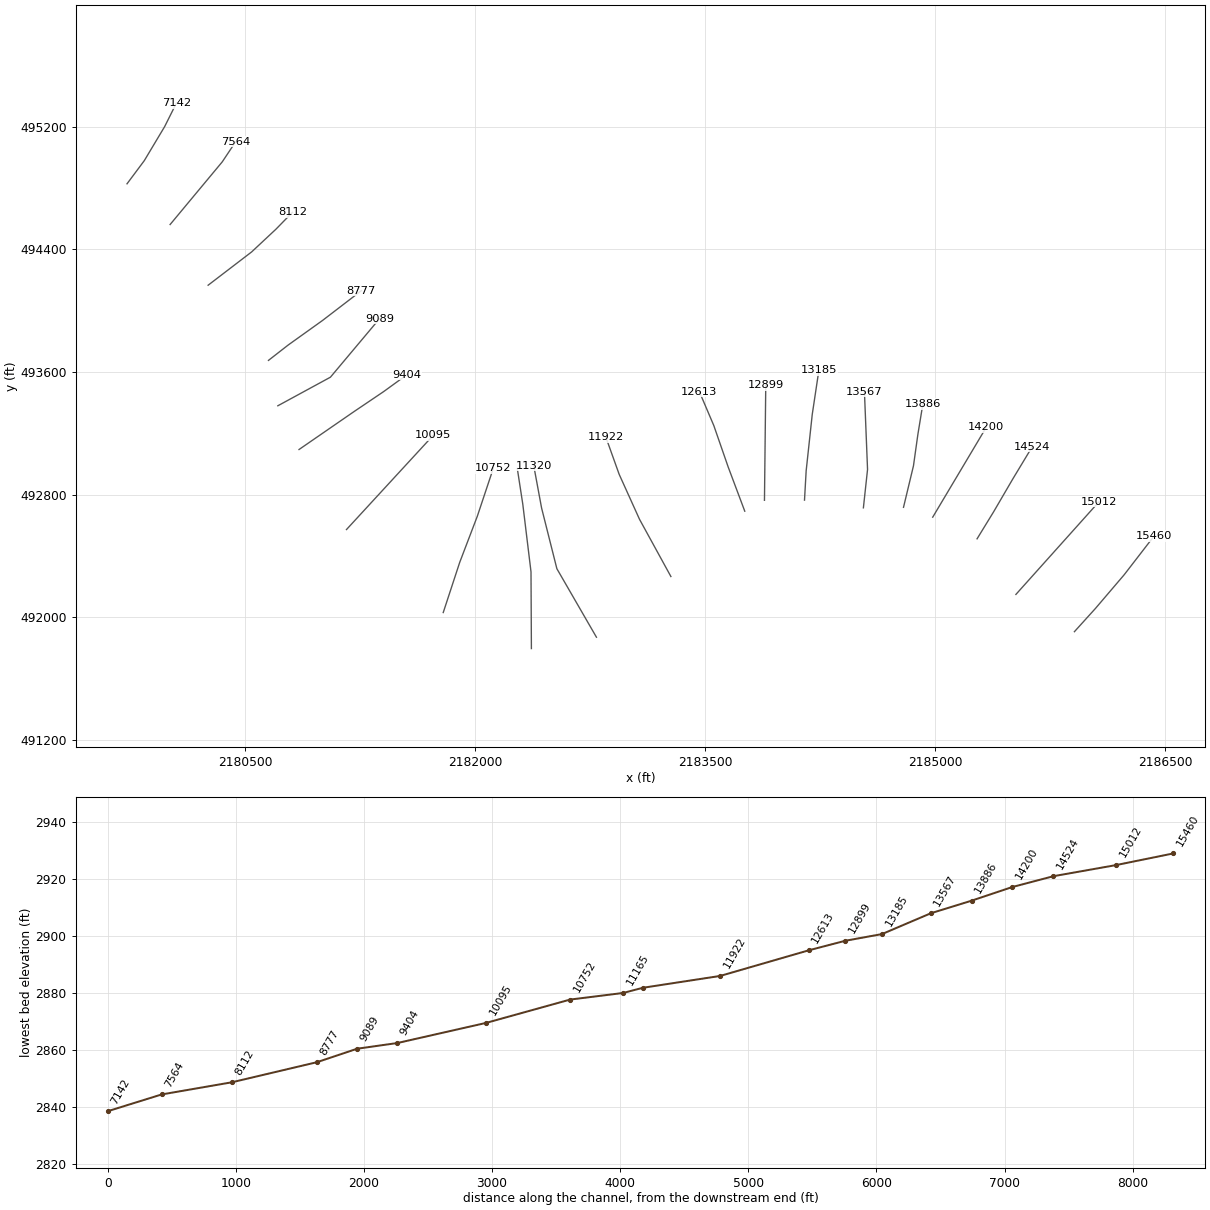
HEC-RAS study WILLIAMSRV.prj: WILLIAMSRV

--- WILLIAMSRV.g01 (geometry) --- (continued)

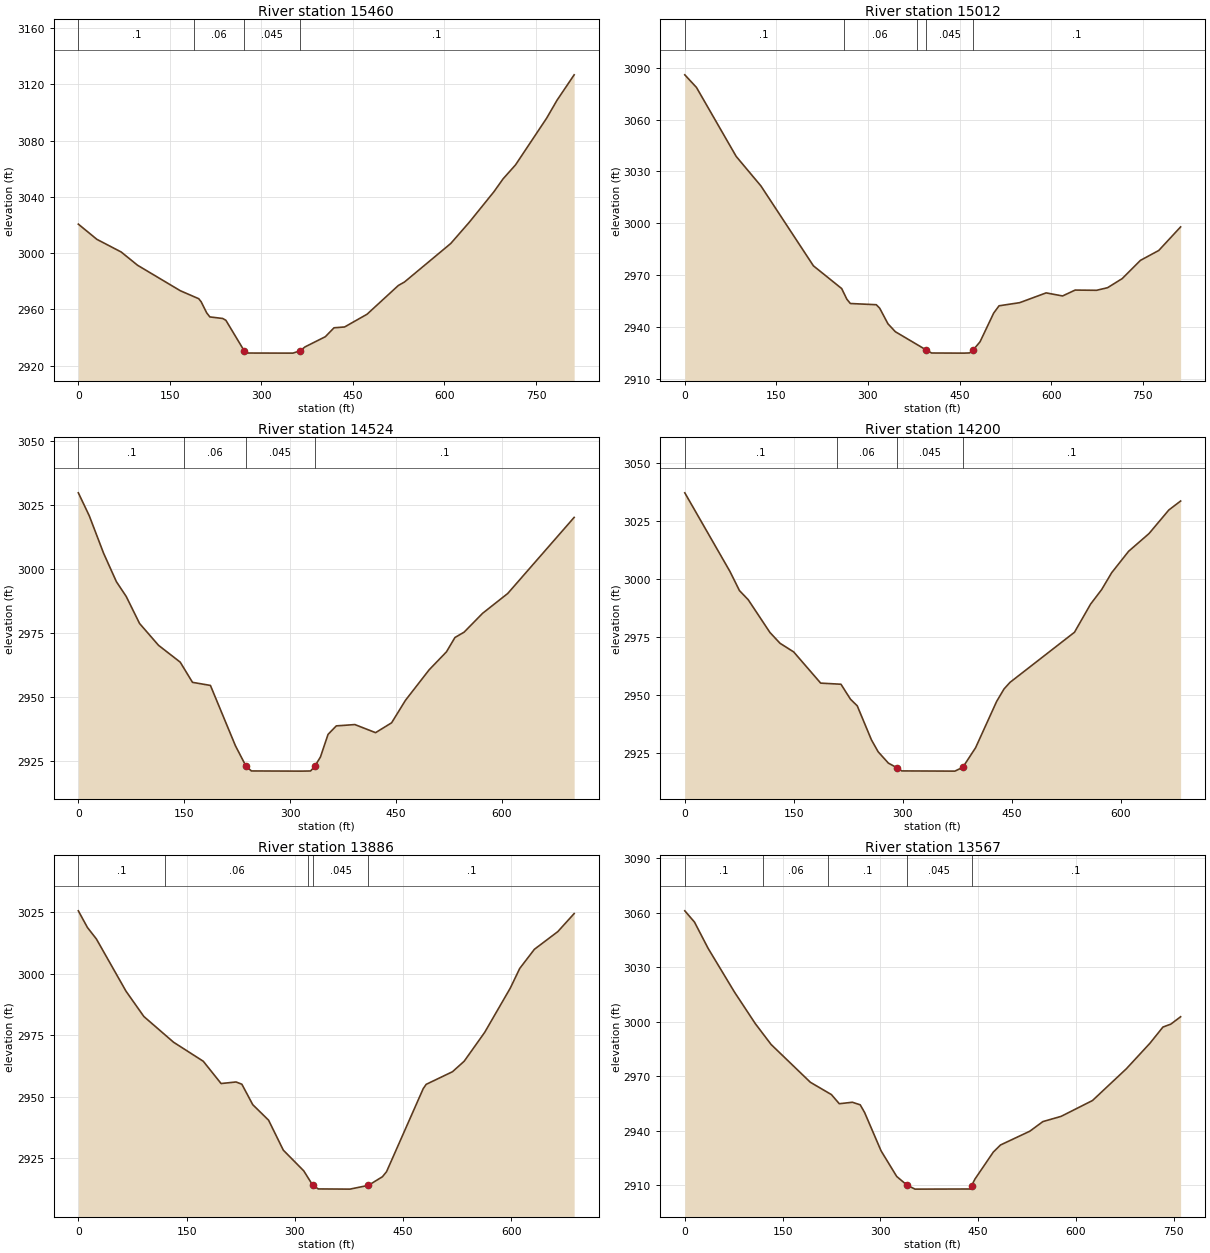
Type RM Length L Ch R = 1 ,15460   ,450.9,448.8,446.3
XS GIS Cut Line= 4
2185907.79710789491905.1446857442186044.89071608492056.669200057
2186232.49249571492276.740518465 2186427.3097284492529.281375654
#Sta/Elev= 30
       0 3020.58    30.4 3009.77    70.2 3000.77    97.1 2991.33   167.3 2973.18
   197.3 2967.55   201.4 2965.29   210.3  2957.5   215.5  2954.6   236.5 2953.49
   241.8 2952.19  271.822930.492   278.6 2928.91   351.7 2928.85  363.352930.496
   371.6 2933.31   404.7 2940.51     419 2946.87   436.3 2947.45   473.1 2956.51
   524.4 2976.96   534.5 2979.45   610.3 3006.83   640.6 3021.91     681 3043.62
   696.1 3052.83   716.4 3062.71   767.4 3095.95   784.5 3108.76812.4725 3126.76
#Mann= 4 ,-1,0
       0      .1       0     190     .06       0  271.82    .045       0
  363.35      .1       0
Bank Sta=271.82,363.35
XS Rating Curve= 0 ,0
Exp/Cntr(USF)=0,0
Exp/Cntr=0.3,0.1

Type RM Length L Ch R = 1 ,15012   ,476.6,487.9,497.8
XS GIS Cut Line= 2
2185526.16418521492148.2577097232186068.04828119492753.247295362
#Sta/Elev= 30
       0  3085.9    19.1 3078.61    84.2 3038.65   124.7 3021.56   210.7  2975.3
     257 2962.13   265.5 2955.95   271.2 2953.48   313.7 2952.78   319.3 2950.74
   332.8 2941.73   344.9 2937.15   395.8  2926.5   404.3 2924.82   457.7 2924.75
   466.6 2924.87   472.3 2926.57   483.6 2931.29     506 2947.95   514.8 2952.16
   548.6 2953.97   591.9 2959.63   618.8 2957.86   639.4 2961.26   674.5 2961.13
   692.5 2962.63   716.5  2967.9   746.4 2978.47   776.4 2984.19   812.2 2997.85
#Mann= 5 ,-1,0
       0      .1       0     260     .06       0     380      .1       0
   395.8    .045       0   472.3      .1       0
Bank Sta=395.8,472.3
XS Rating Curve= 0 ,0
Exp/Cntr(USF)=0,0
Exp/Cntr=0.3,0.1

Type RM Length L Ch R = 1 ,14524   ,324.7,323.6,323.2
XS GIS Cut Line= 4
2185272.83723839492511.2427429972185381.06903433 492688.02134303
2185507.33946292492904.4849349062185633.60989152 493113.73307372
#Sta/Elev= 30
       0 3029.67    15.5  3020.7    35.8 3006.04    53.9 2994.94    67.8 2989.17
    86.7 2978.61   113.6 2970.05   144.3 2963.48   161.7 2955.58   187.1 2954.37
   222.5  2930.8  237.732922.685   245.2 2920.94   315.1 2920.87     329 2920.93
  334.682922.687   342.9 2926.38   353.7 2935.24   365.4 2938.56   391.7 2939.07
     421 2935.91   443.7 2939.76   463.4 2948.58   496.9 2960.48   521.4  2967.5
   533.4  2973.1   546.4  2975.2   572.6 2982.57   608.2 2990.32702.2754 3020.07
#Mann= 4 ,-1,0
       0      .1       0     150     .06       0  237.73    .045       0
  334.68      .1       0
Bank Sta=237.73,334.68
XS Rating Curve= 0 ,0
Exp/Cntr(USF)=0,0
Exp/Cntr=0.3,0.1

Type RM Length L Ch R = 1 ,14200   ,295.4,313.9,335.4
XS GIS Cut Line= 2
2184983.56452549492652.5911827812185332.45692672493238.594924644
#Sta/Elev= 30
       0 3037.05    62.2 3003.09    75.2 2994.88    87.2 2990.97   117.1 2976.84
     131 2972.17   149.8 2968.44   186.9 2954.99   214.8 2954.51   227.9 2948.05
   237.2  2945.2   256.7 2930.54     266 2925.37     280  2920.5   291.6 2918.54
   298.5 2917.13   371.5 2917.04   382.4 2918.68     400 2927.14     429 2947.14
   439.1 2952.47   447.3 2955.31     536 2976.92   558.2 2989.08   573.3 2995.29
   587.2 3002.62   610.5 3011.85   638.5 3019.47   665.8 3029.65     682 3033.52
#Mann= 4 ,-1,0
       0      .1       0     210     .06       0   291.6    .045       0
   382.4      .1       0
Bank Sta=291.6,382.4
XS Rating Curve= 0 ,0
Exp/Cntr(USF)=0,0
Exp/Cntr=0.3,0.1

Type RM Length L Ch R = 1 ,13886   ,310.7,319.6,330.7
XS GIS Cut Line= 4
2184793.00960973 492716.883155282184857.94868729492987.462645125
2184886.81049954493193.1030574082184919.28003832493391.528016628
#Sta/Elev= 30
       0  3025.6    12.6 3018.82      25 3014.15    66.1 2992.87    90.8 2982.58
   131.9 2972.12   173.1 2964.37   197.8 2955.29   218.5 2955.93   226.6 2955.01
   241.7 2946.68   263.6 2940.37     284 2928.18   312.3 2919.76  324.892913.851
   332.5 2912.39   376.3 2912.31  401.96 2913.85   421.4 2917.37     427 2919.38
   477.9 2953.24     482 2954.97   518.4  2960.1   534.6 2964.37     563 2976.12
   598.6  2994.2   611.6 3002.16   631.9 3009.94   664.3 3017.13 686.983 3024.48
#Mann= 5 ,-1,0
       0      .1       0     120     .06       0  318.26      .1       0
  324.89    .045       0  401.96      .1       0
Bank Sta=324.89,401.96
XS Rating Curve= 0 ,0
Exp/Cntr(USF)=0,0
Exp/Cntr=0.3,0.1

Type RM Length L Ch R = 1 ,13567   ,388.5,381.3,371.1
XS GIS Cut Line= 3
2184531.35932585492713.5626703742184558.45776478492964.223230477
2184538.13393558493472.318960416
#Sta/Elev= 30
       0 3061.08    14.9 3054.87    35.8 3040.41    76.1 3016.42   108.2 2998.96
   132.4 2987.51   192.7 2966.68   224.9 2959.93     237 2954.89   257.1  2955.7
   269.1 2954.29   275.8 2950.08   301.1 2928.95   325.1 2914.84   341.1 2910.03
   353.2 2907.88   437.2 2907.95     440 2909.84   445.2 2913.47   473.3  2928.3
   484.3 2932.18   529.3 2939.77   549.3 2945.06   577.3 2947.94   625.4 2956.65
   677.4 2974.15   713.6 2988.21   733.5 2997.11   745.5 2998.69   760.6 3002.77
#Mann= 5 ,-1,0
       0      .1       0     120     .06       0     220      .1       0
   341.1    .045       0     440      .1       0
Bank Sta=341.1,440
XS Rating Curve= 0 ,0
Exp/Cntr(USF)=0,0
Exp/Cntr=0.3,0.1

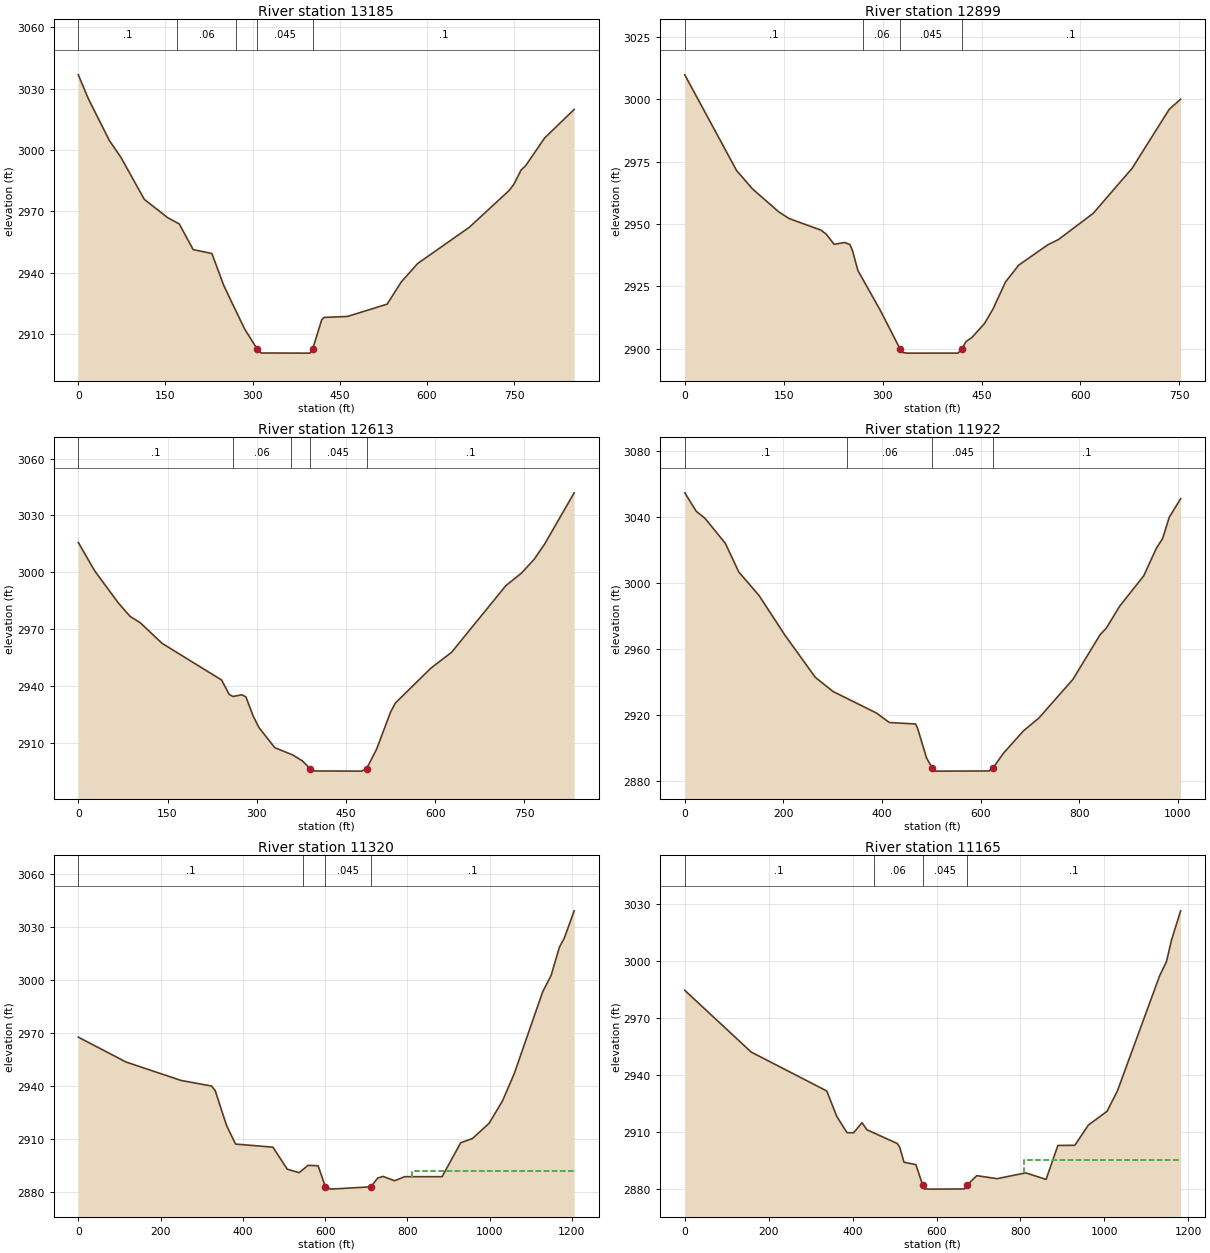
Type RM Length L Ch R = 1 ,13185   ,280.9,286,291.8
XS GIS Cut Line= 4
2184147.22656063492763.7836001862184158.04974023492954.993106344
2184197.73473207493322.9812125332184241.02745045493611.599335035
#Sta/Elev= 30
       0 3036.72    17.4 3024.94    53.5 3004.56    73.5 2996.27   113.6  2975.8
   153.6 2966.89   173.7  2963.8   197.7 2951.22   229.9 2949.33     250 2933.95
   262.1 2926.63   286.2 2912.44  307.852902.611   314.4 2900.66   394.5 2900.59
   398.9 2900.63  403.342902.614     419 2916.96     423 2918.06   463.3 2918.53
   531.7 2924.57   555.8 2935.38   584.1 2944.42   673.1 2962.17   741.8 2980.21
   749.9 2983.27   762.1 2990.15   770.1 2992.31   802.5 3005.77853.4844  3019.8
#Mann= 5 ,-1,0
       0      .1       0     170     .06       0  271.52      .1       0
  307.85    .045       0  403.34      .1       0
Bank Sta=307.85,403.34
XS Rating Curve= 0 ,0
Exp/Cntr(USF)=0,0
Exp/Cntr=0.3,0.1

Type RM Length L Ch R = 1 ,12899   ,266,285.8,305.3
XS GIS Cut Line= 2
2183886.07774883492762.6785909342183894.54601099493514.660271244
#Sta/Elev= 30
       0 3009.79    78.5 2971.46   102.5 2964.11   142.5 2954.86   158.5 2952.15
   206.5 2947.55   214.5 2945.94   226.5 2941.87   242.5 2942.58   250.5 2941.77
   254.5 2939.21   262.5 2931.37   295.8 2915.75   326.5 2899.93   330.5 2898.49
   336.8 2898.25   414.5 2898.26  420.16 2899.95   426.5 2902.86   435.7  2904.6
   454.5 2910.09   467.4 2915.91   486.5 2926.81   506.5 2933.53   550.5 2941.66
   566.8 2943.79   619.4 2954.27   678.5 2972.35   734.5 2995.89     752 3000.04
#Mann= 4 ,-1,0
       0      .1       0     270     .06       0   326.5    .045       0
  420.16      .1       0
Bank Sta=326.5,420.16
XS Rating Curve= 0 ,0
Exp/Cntr(USF)=0,0
Exp/Cntr=0.3,0.1

Type RM Length L Ch R = 1 ,12613   ,686,691,692.7
XS GIS Cut Line= 4
2183757.59209526492691.6290695612183649.36029932492980.247192063
 2183555.5594095493250.8266819082183461.75851969493470.898000315
#Sta/Elev= 30
       0 3015.73    27.3 3000.85    67.5  2983.7    87.1 2976.68   104.2 2973.32
   140.7 2962.47   240.9 2943.06   253.7 2935.46     260 2934.35   275.1 2935.24
   281.9 2934.11   294.1 2923.96   303.7 2917.95   330.4 2907.29   360.2  2903.5
     377 2900.28  390.042896.133   394.8    2895   476.3  2894.9  484.772896.133
   501.7 2906.56   525.1  2926.1   533.1 2930.86   592.8  2949.3   627.6 2957.66
   718.9 2992.89   745.3 2999.59   766.5 3006.81   784.2 3014.89833.8494 3041.98
#Mann= 5 ,-1,0
       0      .1       0     260     .06       0  358.24      .1       0
  390.04    .045       0  484.77      .1       0
Bank Sta=390.04,484.77
XS Rating Curve= 0 ,0
Exp/Cntr(USF)=0,0
Exp/Cntr=0.3,0.1

Type RM Length L Ch R = 1 ,11922   ,615.1,602.6,593.8
XS GIS Cut Line= 4
2183275.74954875492265.1137914032183071.28306127492638.265131042
2182938.37984441492932.1857067862182851.48158724493174.989660661
#Sta/Elev= 30
       0 3054.74    23.3 3043.52      41 3039.29    82.2 3024.13   109.5 3006.75
   150.6 2992.47     203 2968.47   264.9 2942.79   301.1 2934.18   388.7 2921.19
   415.1 2915.42   468.2 2914.52   472.4 2911.82   490.5 2893.92  501.932887.858
   508.6 2885.93   617.5 2886.03  625.35 2887.86   646.6 2896.82     687 2910.33
   718.4 2918.15   787.4 2941.58   842.6 2968.69   855.3 2972.69     882 2985.86
   931.3 3004.49   956.4  3020.9   969.6 3027.15   982.8 3039.881005.955 3051.19
#Mann= 4 ,-1,0
       0      .1       0     330     .06       0  501.93    .045       0
  625.35      .1       0
Bank Sta=501.93,625.35
XS Rating Curve= 0 ,0
Exp/Cntr(USF)=0,0
Exp/Cntr=0.3,0.1

Type RM Length L Ch R = 1 ,11320   ,162.4,154.5,147
XS GIS Cut Line= 4
  2182790.141641491868.9599719222182532.00270056492316.230413271
2182432.32528792492712.3842327522182381.20866605492988.413990841
#Sta/Elev= 30
       0 2967.88   115.8  2953.8   249.6 2943.36     324 2940.17   332.8 2937.62
   360.5 2917.78   382.3 2907.31   473.1 2905.56   508.1 2893.08   536.8 2891.11
   558.6 2895.26     583 2895.03  600.892883.105   614.1 2881.79  711.332883.104
     728 2888.07   741.1 2888.98     769 2886.53   793.5 2888.84   884.5 2888.84
   929.8 2908.06   958.3 2910.44     999 2919.12  1031.5 2931.82    1060 2947.23
  1129.1 2993.55  1149.5 3002.76  1169.8 3018.86    1182 3024.121205.641 3039.41
#Mann= 4 ,-1,0
       0      .1       0  546.42     .06       0  600.89    .045       0
  711.33      .1       0
#XS Ineff= 2 , 0
                          810.51          2891.9
Permanent Ineff=
       F       F
Bank Sta=600.89,711.33
XS Rating Curve= 0 ,0
Exp/Cntr(USF)=0,0
Exp/Cntr=0.3,0.1

Type RM Length L Ch R = 1 ,11165   ,446.5,413.3,385.2
XS GIS Cut Line= 4
2182365.87367949491794.8408702132182363.31784839492295.783764524
2182309.64539543492737.9425436862182273.86376012492970.523173187
#Sta/Elev= 30
       0 2984.56   158.3 2952.09   338.3 2931.63   362.3  2918.2   386.6 2909.69
   402.3  2909.6   422.3 2914.92   434.3 2911.18   506.4 2903.98   512.2 2902.02
   522.5 2894.11   550.7 2892.88  567.27 2881.94   570.9 2880.09   590.7 2879.97
   666.7 2880.07  672.092881.944   695.8 2887.06   744.1 2885.48   812.6 2888.52
     861 2885.09   889.2 2902.96   929.5 2903.02   961.8 2913.68  1006.3 2920.92
  1031.2 2931.74  1131.7 2992.26  1147.9 2999.68  1160.1 3011.151181.671 3026.41
#Mann= 4 ,-1,0
       0      .1       0     450     .06       0  567.27    .045       0
  672.09      .1       0
#XS Ineff= 2 , 0
                          807.49         2895.45
Permanent Ineff=
       F       F
Bank Sta=567.27,672.09
XS Rating Curve= 0 ,0
Exp/Cntr(USF)=0,0
Exp/Cntr=0.3,0.1

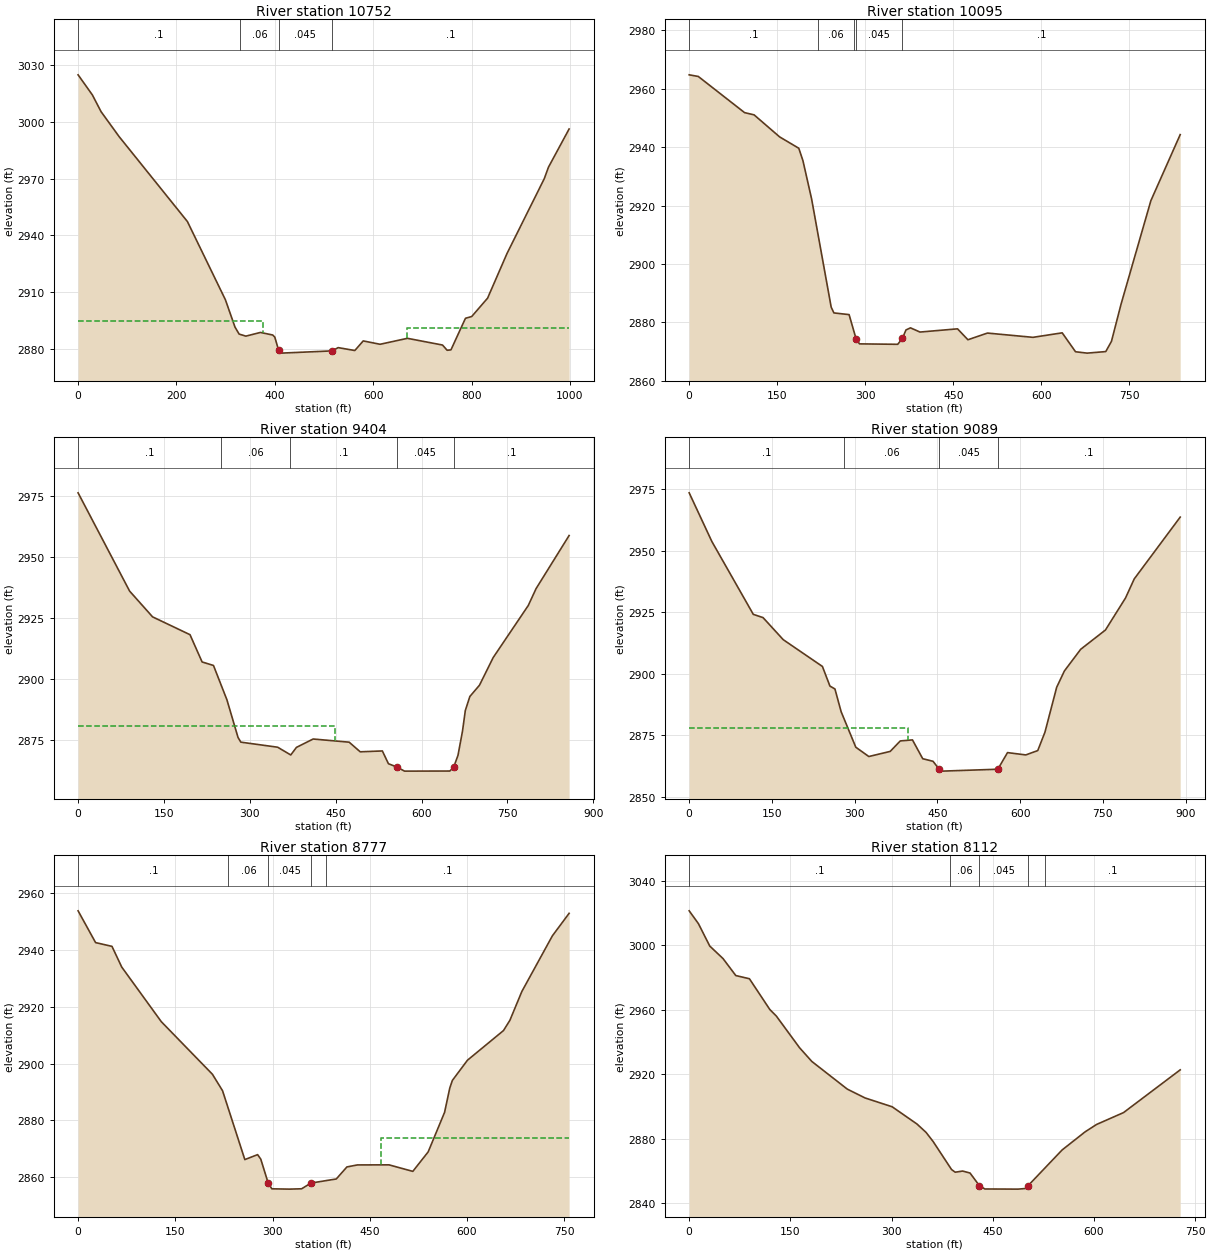
Type RM Length L Ch R = 1 ,10752   ,681.7,656.8,638.9
XS GIS Cut Line= 4
2181790.81168347492029.9773308082181898.15658939492357.123710766
2182013.16898859 492658.711779792182117.95806343492973.079004281
#Sta/Elev= 30
       0 3024.87      29 3014.26    46.7 3005.39    83.4  2992.2   222.3 2947.26
   299.5 2905.92   319.1 2891.41   327.5 2887.73   341.2 2886.65   370.7  2888.6
   395.7 2887.25     400 2886.14  407.582879.312   412.9 2877.66   516.4 2878.84
   528.8 2880.57   562.7 2879.04   579.8 2884.12   614.1 2882.34   669.7 2885.49
     741 2881.94   750.5 2879.16   758.2 2879.39   787.7 2896.09   800.4 2897.02
   832.7 2906.74   872.1 2930.32     948 2969.96   956.4 2975.98998.4539 2996.22
#Mann= 4 ,-1,0
       0      .1       0     330     .06       0  407.58    .045       0
   516.4      .1       0
#XS Ineff= 2 , 0
          375.55 2894.64   669.6         2890.82
Permanent Ineff=
       F       F
Bank Sta=407.58,516.4
XS Rating Curve= 0 ,0
Exp/Cntr(USF)=0,0
Exp/Cntr=0.3,0.1

Type RM Length L Ch R = 1 ,10095   ,692.5,691.2,687.8
XS GIS Cut Line= 2
2181159.75225296492571.7591097992181725.98426494493187.315359883
#Sta/Elev= 30
       0 2964.81    15.5 2964.25    94.3 2951.87   110.6 2951.09   154.2 2943.53
   186.7 2939.66   193.8 2935.38   208.5 2922.33   241.9 2885.22   246.5 2883.25
   272.4 2882.67   284.2 2874.44   290.1 2872.65   355.2  2872.5  363.09  2874.5
   369.3 2877.42   376.9 2878.14   393.2  2876.7   457.1  2877.8   474.8 2874.06
     508 2876.35   585.6 2874.89   635.4 2876.43   658.1 2869.95   677.9 2869.48
   709.6 2870.01   719.3 2873.51   735.6 2886.21   786.4 2921.68   836.4 2944.33
#Mann= 5 ,-1,0
       0      .1       0     220     .06       0     280      .1       0
   284.2    .045       0  363.09      .1       0
Bank Sta=284.2,363.09
XS Rating Curve= 0 ,0
Exp/Cntr(USF)=0,0
Exp/Cntr=0.3,0.1

Type RM Length L Ch R = 1 ,9404    ,294.9,314.8,328.9
XS GIS Cut Line= 4
 2180850.2116309493094.1798570642181210.60845607493342.845567389
2181402.26621889493472.2802283422181554.82656464493583.049336385
#Sta/Elev= 30
       0 2976.38      90 2936.15   130.1  2925.6   195.5  2918.3   216.6 2907.14
   236.5  2905.7     260 2891.62   279.4 2876.22   284.3  2874.3   348.6 2872.23
   371.5 2869.06   381.4 2872.16   410.6 2875.59   473.5 2874.29   492.8 2870.35
   531.5  2870.7   542.1 2865.47   556.4 2864.17   570.3 2862.44   649.3 2862.48
655.83472863.942   663.6  2868.9   671.5 2878.84   676.4 2887.24   684.3 2892.99
   701.1  2897.6   725.1 2908.94   786.4 2930.26     800 2937.16   857.7  2958.9
#Mann= 5 ,-1,0
       0      .1       0     250     .06       0     370      .1       0
   556.4    .045       0655.8347      .1       0
#XS Ineff= 2 , 0
          449.34 2881.09
Permanent Ineff=
       F       F
Bank Sta=556.4,655.8347
XS Rating Curve= 0 ,0
Exp/Cntr(USF)=0,0
Exp/Cntr=0.3,0.1

Type RM Length L Ch R = 1 ,9089    ,324.3,312.6,300.8
XS GIS Cut Line= 3
2180712.07740146493379.6888183162181055.04201917 493566.26157035
2181376.05690135493949.010083713
#Sta/Elev= 30
       0 2973.44    41.1 2953.68   116.2  2924.1   133.9 2922.77   170.5 2913.81
   241.5 2902.94   255.1 2894.98   264.2 2893.79   275.4 2884.58     302 2870.15
   325.6 2866.37   364.4 2868.45   382.6  2872.7   404.7 2873.12   423.3 2865.48
     442 2864.43   452.9 2861.28   458.6 2860.44  559.42 2861.21     577 2867.96
   610.1 2867.02   631.8 2868.78   644.8 2876.21   666.1 2894.48   680.1 2901.11
   709.6  2909.9   754.5 2917.74   790.8 2930.71   806.7 2938.49     890 2963.58
#Mann= 4 ,-1,0
       0      .1       0     280     .06       0   452.9    .045       0
  559.42      .1       0
#XS Ineff= 2 , 0
          396.06 2877.79
Permanent Ineff=
       F       F
Bank Sta=452.9,559.42
XS Rating Curve= 0 ,0
Exp/Cntr(USF)=0,0
Exp/Cntr=0.3,0.1

Type RM Length L Ch R = 1 ,8777    ,656.2,664.4,668.7
XS GIS Cut Line= 4
 2180650.9110158493675.9325549722180778.70257047493775.609967616
2181003.61570669493936.6273265012181256.64298494494130.870489601
#Sta/Elev= 30
       0 2953.84      27 2942.64    52.3 2941.31    67.3 2934.03   128.4 2914.76
   207.3 2896.22   222.9 2890.42   257.3 2866.14     277 2867.89   281.9  2866.3
  293.322857.869     299 2855.84   326.2 2855.73   344.9 2855.85  359.332857.868
   398.4 2859.31   414.8 2863.55   430.9 2864.26   479.7 2864.29   516.5 2861.99
   540.2 2868.86   565.5 2882.79   573.5 2891.33   577.5 2894.04   600.8 2901.17
   656.4 2911.63   666.3 2915.25   684.8 2925.43   731.9 2945.04757.6655 2952.96
#Mann= 5 ,-1,0
       0      .1       0  232.07     .06       0  293.32    .045       0
  359.33     .06       0  382.07      .1       0
#XS Ineff= 2 , 0
                          466.96         2873.64
Permanent Ineff=
       F       F
Bank Sta=293.32,359.33
XS Rating Curve= 0 ,0
Exp/Cntr(USF)=0,0
Exp/Cntr=0.3,0.1

Type RM Length L Ch R = 1 ,8112    ,540.6,547.8,555.8
XS GIS Cut Line= 4
2180257.31302741494166.6521249092180541.01027878 494383.89776785
2180699.47180658494532.135971269 2180806.8167125494642.036708286
#Sta/Elev= 30
       0  3021.5    13.7 3013.54    30.5 2999.63    50.2 2991.84    69.1 2981.31
    89.3 2979.33   119.5 2960.25   129.2 2956.16   163.6  2936.5   181.8 2927.98
   234.4 2910.79   260.7 2905.31   300.9 2899.83   337.7 2889.12   351.2 2883.91
   361.7 2878.22     389 2860.83   394.4  2859.2   405.5 2859.91   416.4 2858.67
   430.22850.852   438.3 2848.78   487.6 2848.69   498.6 2849.08  502.472850.852
   552.9 2873.02   586.9 2884.24   603.8 2888.81     644 2896.23727.9395 2922.75
#Mann= 5 ,-1,0
       0      .1       0  387.32     .06       0   430.2    .045       0
  502.47     .06       0  527.32      .1       0
Bank Sta=430.2,502.47
XS Rating Curve= 0 ,0
Exp/Cntr(USF)=0,0
Exp/Cntr=0.3,0.1

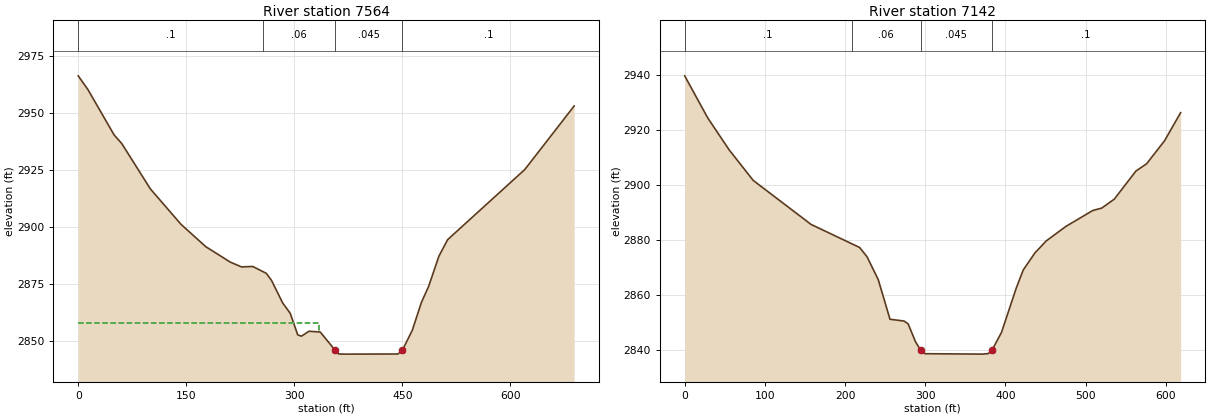
Type RM Length L Ch R = 1 ,7564    ,413.3,421.9,430.7
XS GIS Cut Line= 4
2180009.39741135 494562.80594439 2180147.4122904494728.934965462
2180349.32294678494971.7389193372180436.22120395495102.086305102
#Sta/Elev= 30
       0 2966.26    13.5 2960.24    49.9 2940.36    60.5 2936.59   100.2 2916.75
   142.8 2901.22   176.9 2891.51   211.1 2884.71   226.7 2882.61   242.3 2882.81
     261 2879.81   268.3 2876.74   283.9 2866.79   294.3 2862.31   304.7 2852.88
   309.9 2852.29   320.3 2854.45     336  2854.1  356.442846.224   361.6  2844.5
   370.1 2844.43   443.9 2844.49  450.132846.222   463.8 2854.91   476.4 2867.08
   486.5 2874.14   500.7 2887.32   512.8 2894.54     620 2925.27688.4245 2953.06
#Mann= 4 ,-1,0
       0      .1       0  255.98     .06       0  356.44    .045       0
  450.13      .1       0
#XS Ineff= 2 , 0
          333.81 2858.24
Permanent Ineff=
       F       F
Bank Sta=356.44,450.13
XS Rating Curve= 0 ,0
Exp/Cntr(USF)=0,0
Exp/Cntr=0.3,0.1

Type RM Length L Ch R = 1 ,7142    ,517,518.6,520.2
XS GIS Cut Line= 4
2179728.25599107494828.6123781062179840.71255918494979.406412618
2179973.61577604495201.7637177462180050.29070884495355.113583351
#Sta/Elev= 30
       0 2939.69    28.9 2924.33    55.6 2912.74    85.5 2901.68   157.6  2885.7
   218.2 2877.31   227.5 2873.93   241.5 2865.59   256.1 2851.22   273.6 2850.58
   278.7 2849.56     288 2843.01  294.56 2839.88   299.8  2838.7   371.9 2838.55
   378.6 2838.74  383.172839.882   395.2 2846.45   413.6 2862.57   422.3 2869.13
   436.9 2875.34     451  2879.7   475.5 2884.96   509.1 2890.76   520.2 2891.62
   535.9 2894.88   562.8 2905.07   576.2 2907.73   598.6  2916.1618.6086 2926.31
#Mann= 4 ,-1,0
       0      .1       0  208.11     .06       0  294.56    .045       0
  383.17      .1       0
Bank Sta=294.56,383.17
XS Rating Curve= 0 ,0
Exp/Cntr(USF)=0,0
Exp/Cntr=0.3,0.1