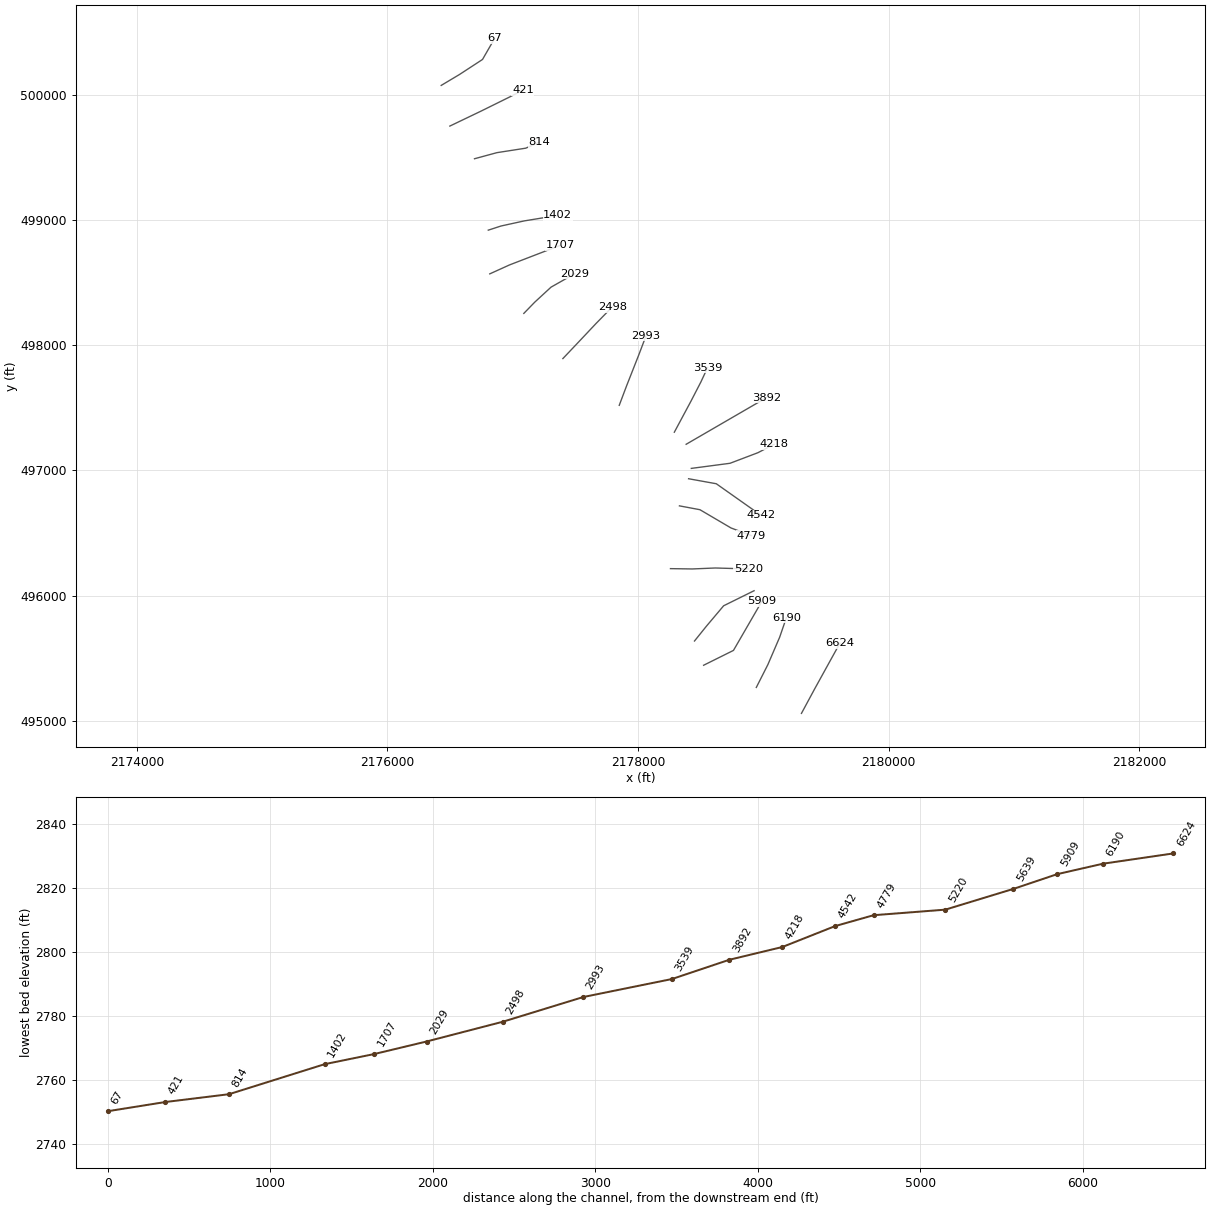
HEC-RAS study WILLIAMSRV.prj: WILLIAMSRV

--- WILLIAMSRV.g01 (geometry) --- (continued)

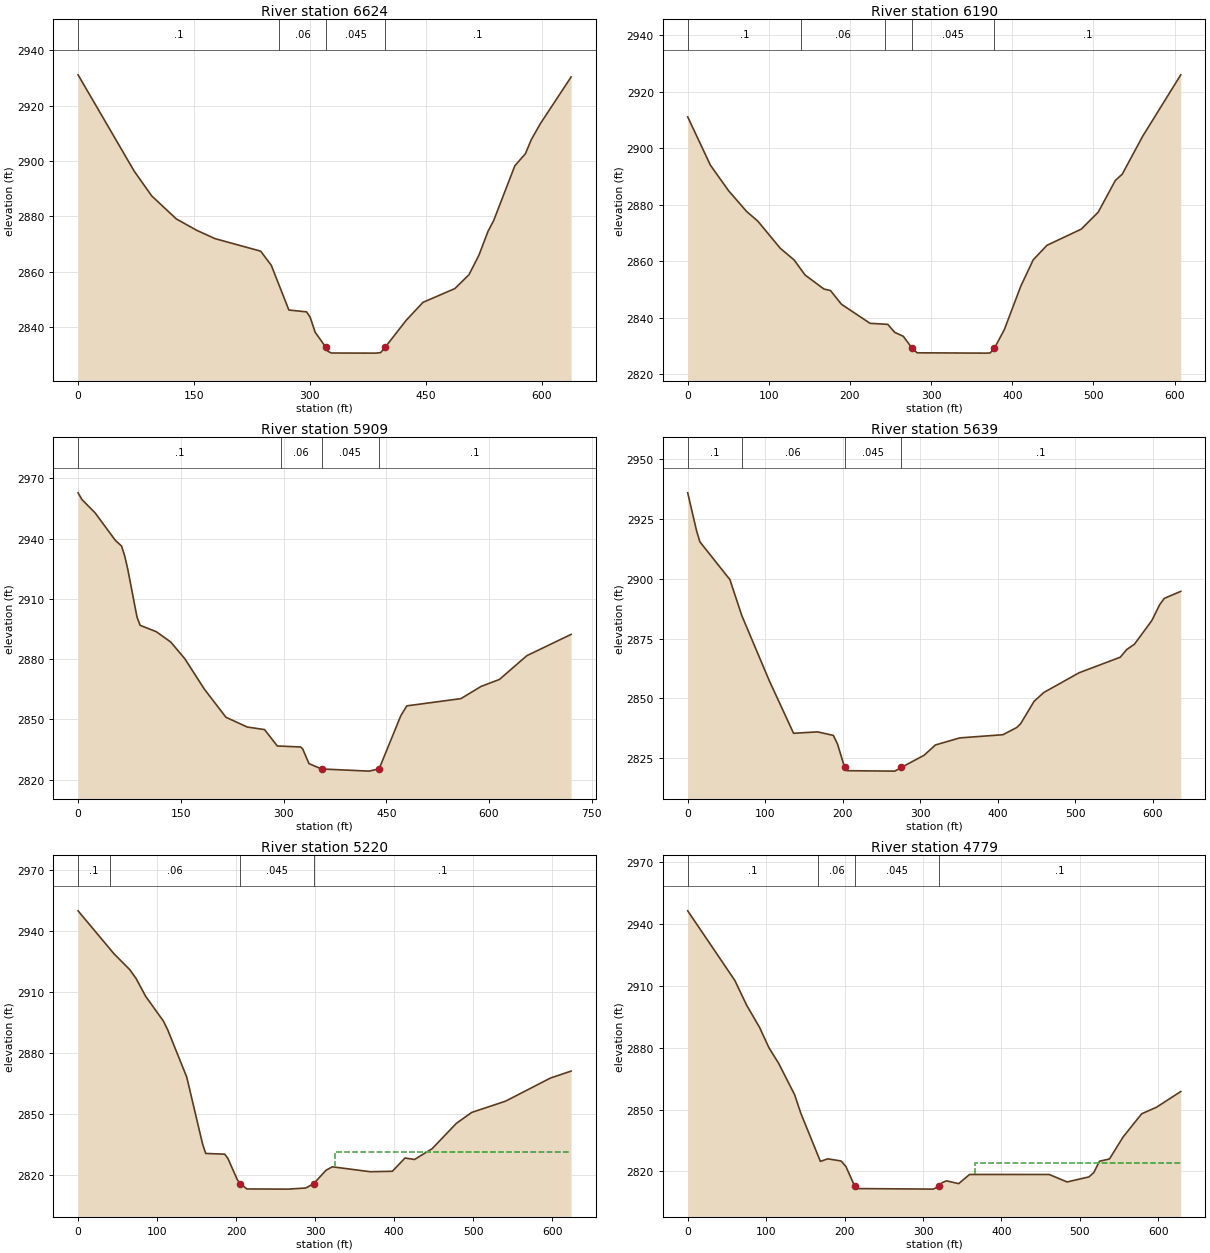
Type RM Length L Ch R = 1 ,6624    ,428.4,433.4,438.9
XS GIS Cut Line= 4
2179303.98802957495061.193007607 2179408.7771044495255.436170707
2179531.45699688495477.7934758352179610.68776078495620.920017067
#Sta/Elev= 30
       0 2931.09    72.7 2896.32    95.4 2887.39   127.2  2879.1   153.6 2874.99
   177.3 2871.99   236.4 2867.47   250.1 2862.38   272.9 2846.23   295.8 2845.57
   300.4 2843.67   306.9 2838.23  320.842832.761   323.2 2831.37   327.8 2830.72
   385.1 2830.68   391.7 2830.86  397.452832.763   424.7 2842.51   446.5    2849
   487.7 2853.96     506 2858.96   518.9 2866.01   530.7 2874.63     538 2878.52
   565.4 2898.28   579.1 2902.63   586.6 2907.66   598.3 2913.41638.2542 2930.33
#Mann= 4 ,-1,0
       0      .1       0  260.71     .06       0  320.84    .045       0
  397.45      .1       0
Bank Sta=320.84,397.45
XS Rating Curve= 0 ,0
Exp/Cntr(USF)=0,0
Exp/Cntr=0.3,0.1

Type RM Length L Ch R = 1 ,6190    ,288,281.3,275.5
XS GIS Cut Line= 4
2178943.61584539495268.2153261752179035.62576476495449.679333808
2179130.19151521495669.4808078422179183.86396817495825.386504541
#Sta/Elev= 30
       0 2911.13      28 2894.02    50.4 2884.98    72.6 2877.63    86.3 2874.25
   114.2 2864.57   131.1 2860.48   144.6 2855.15   167.8 2850.18     176 2849.63
   189.4  2844.8   224.7 2838.03   246.5 2837.66   255.2 2834.82   265.6 2833.45
  276.582829.218   282.7 2827.58   368.4 2827.47   372.7 2827.52  378.022829.217
   390.2  2835.8   410.5 2851.19   425.8 2860.51   442.7 2865.65     485 2871.38
   505.9 2877.39     527 2888.63   535.5 2890.84   560.5 2904.18607.6243 2926.03
#Mann= 5 ,-1,0
       0      .1       0     140     .06       0  243.46      .1       0
  276.58    .045       0  378.02      .1       0
Bank Sta=276.58,378.02
XS Rating Curve= 0 ,0
Exp/Cntr(USF)=0,0
Exp/Cntr=0.3,0.1

Type RM Length L Ch R = 1 ,5909    ,278.2,269.9,261.5
XS GIS Cut Line= 3
2178523.06273021495445.2220558592178761.35454659 495563.75062774
2178988.53430936495956.376522093
#Sta/Elev= 30
       0 2962.84     5.7 2959.47    24.7 2952.93    54.5 2939.15    63.5 2936.34
    68.3 2931.14    72.7 2924.56    86.1 2900.86    90.6 2896.85   114.2 2893.67
   135.3 2888.52   155.9 2880.18   184.4 2865.05   215.9 2851.05     247 2846.18
   272.2 2844.92   290.9 2836.74   324.9 2836.25   327.9  2835.3   337.1 2827.96
   355.52825.296   424.9 2824.22   439.5 2825.36   471.2 2851.86     480 2856.73
   558.9 2860.33   588.3  2866.4   615.2  2869.9   655.1 2881.71   719.8 2892.34
#Mann= 4 ,-1,0
       0      .1       0  296.14     .06       0   355.5    .045       0
   439.5      .1       0
Bank Sta=355.5,439.5
XS Rating Curve= 0 ,0
Exp/Cntr(USF)=0,0
Exp/Cntr=0.3,0.1

Type RM Length L Ch R = 1 ,5639    ,455.6,419,375.9
XS GIS Cut Line= 4
2178450.34044436495638.8108347212178544.90619482495756.379065018
2178682.92107386495919.9522549972178925.72502774496040.076316388
#Sta/Elev= 30
       0 2935.95    11.5    2920    15.7 2915.48    54.4 2899.68    69.8 2884.61
     105 2857.55   136.5 2835.44   167.6 2836.03   187.8 2834.55   193.2 2830.92
  202.342821.182   205.6  2819.8   267.1 2819.62  275.552821.182   304.8 2826.25
   319.4 2830.55   350.8 2833.51   406.5 2834.84   424.3 2837.85   429.5 2839.54
   446.6 2848.77   459.3 2852.51   504.6 2860.72   557.8 2867.24   566.1 2870.44
     576 2872.65   598.4 2882.52   608.6 2889.19   614.6 2891.85 635.794 2894.76
#Mann= 4 ,-1,0
       0      .1       0      70     .06       0  202.34    .045       0
  275.55      .1       0
Bank Sta=202.34,275.55
XS Rating Curve= 0 ,0
Exp/Cntr(USF)=0,0
Exp/Cntr=0.3,0.1

Type RM Length L Ch R = 1 ,5220    ,472.7,441,402.4
XS GIS Cut Line= 4
2178258.65311236496216.4286618342178432.44962671496213.872830741
2178616.46946543496221.5403240212178882.27589915496213.872830741
#Sta/Elev= 30
       0 2949.75    45.5 2928.65    65.5 2920.84    73.5 2916.48    85.5 2907.81
   107.9 2895.68   113.5 2891.28   137.5 2868.18   157.5 2835.39   161.5 2830.66
   185.6 2830.31   189.6 2828.22   201.6 2817.71  205.39 2815.86   213.6 2813.23
   266.2 2813.15   288.2 2813.71  298.222815.858   313.7  2822.4   321.7 2824.11
   369.7 2821.69   397.7 2821.91   413.7 2828.42   425.7  2827.7     448 2832.98
   478.6  2845.4   498.1  2850.8   540.9 2856.32   597.8 2867.68623.9118 2871.09
#Mann= 4 ,-1,0
       0      .1       0      40     .06       0  205.39    .045       0
  298.22      .1       0
#XS Ineff= 2 , 0
                          324.56         2831.27
Permanent Ineff=
       F       F
Bank Sta=205.39,298.22
XS Rating Curve= 0 ,0
Exp/Cntr(USF)=0,0
Exp/Cntr=0.3,0.1

Type RM Length L Ch R = 1 ,4779    ,244.2,237.2,235.4
XS GIS Cut Line= 4
2178330.21638297496717.3715561452178493.78957295496686.701583024
2178741.70518901496541.0192106992178905.27837899496479.679264457
#Sta/Elev= 30
       0 2946.28    60.1 2912.54    75.2  2900.5    91.5 2889.88   103.7 2879.86
   115.9 2872.42   136.3 2857.19   144.4 2848.01   169.2 2824.85   178.5 2826.11
   195.6 2825.05   201.7 2822.39     2132812.773   216.8 2811.69     313 2811.42
  320.652812.769   324.2 2814.51     330 2815.43   345.5 2814.08   359.4 2818.53
   460.9 2818.52   483.7  2814.9   511.7 2817.35   517.9 2819.52     525 2824.92
   537.8 2826.05   555.2 2836.72   578.8 2847.92   597.6 2851.08628.6708 2858.72
#Mann= 4 ,-1,0
       0      .1       0  166.42     .06       0     213    .045       0
  320.65      .1       0
#XS Ineff= 2 , 0
                          366.37         2824.32
Permanent Ineff=
       F       F
Bank Sta=213,320.65
XS Rating Curve= 0 ,0
Exp/Cntr(USF)=0,0
Exp/Cntr=0.3,0.1

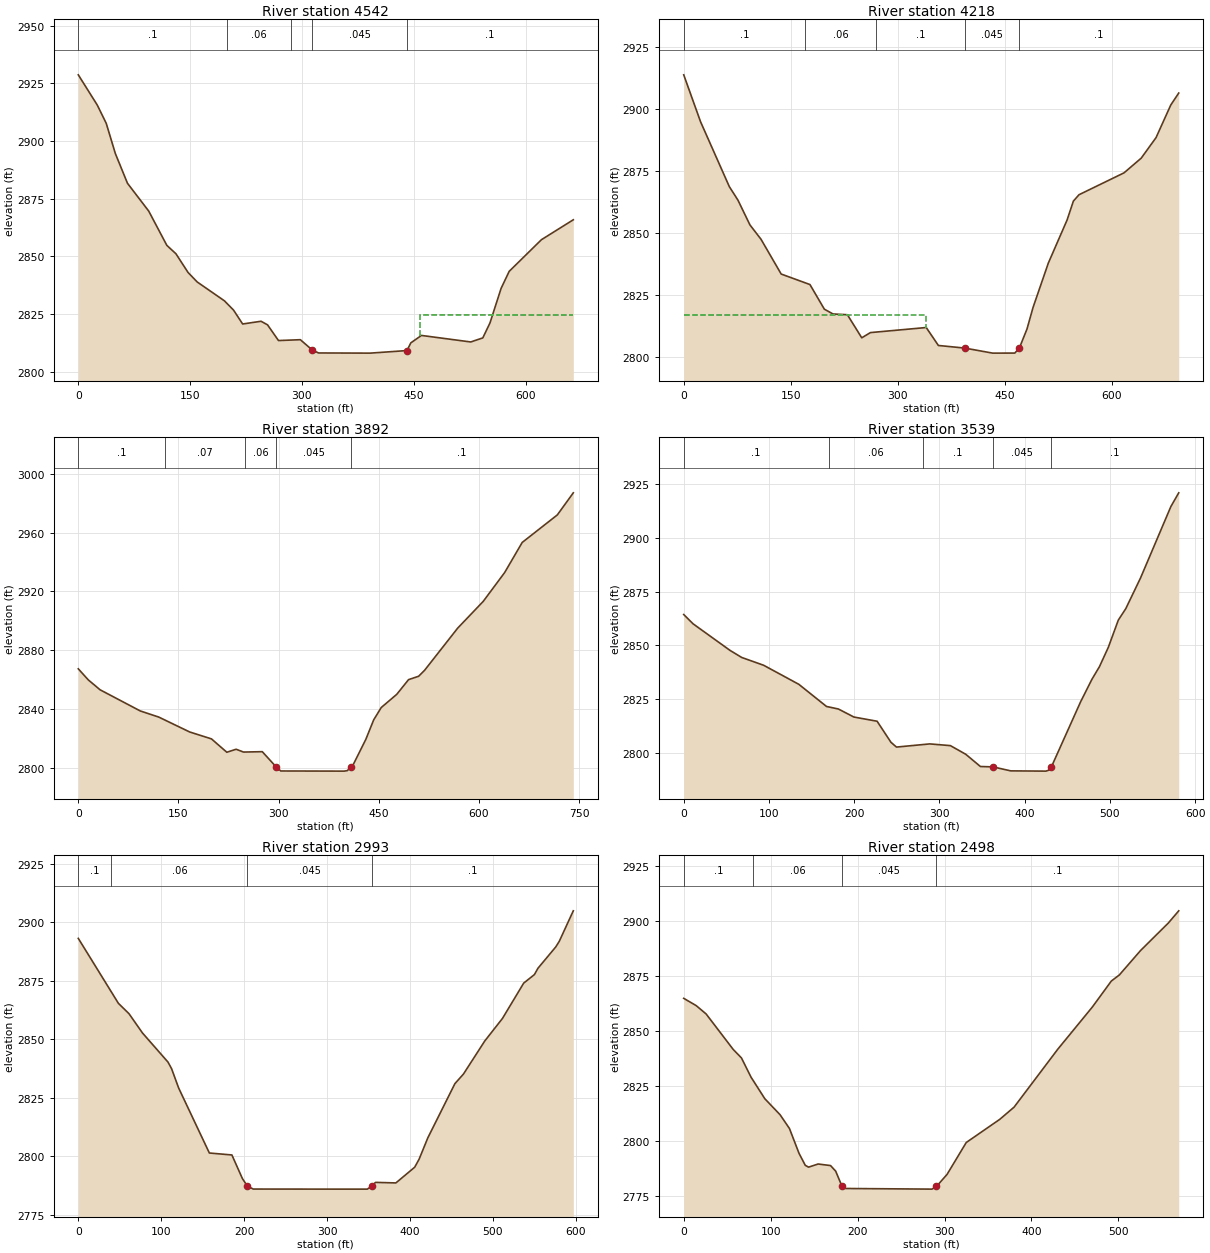
Type RM Length L Ch R = 1 ,4542    ,277.4,324.1,382.9
XS GIS Cut Line= 3
2178403.23196803496933.8869206022178624.36183495496893.883527592
2178983.28116668496640.528705197
#Sta/Elev= 30
       0 2928.65    25.5 2915.53    37.5 2907.62    49.7 2894.55      66 2881.64
    94.5 2869.59   118.8 2854.73     131 2851.09   147.3 2842.97   159.5 2838.87
   196.1 2830.68   208.3 2826.66   220.5 2820.65   245.2 2821.83   253.9 2820.28
   268.6 2813.47   297.9 2813.84   314.1 2809.32   322.4 2808.09   391.6 2808.02
     441 2809.13   446.1 2812.46   460.4 2815.69   526.5 2812.86   542.7 2814.62
   552.3 2821.09   567.2 2836.05   578.1 2843.47   621.3 2857.17   664.1 2865.82
#Mann= 5 ,-1,0
       0      .1       0     200     .06       0  284.72      .1       0
   314.1    .045       0     441      .1       0
#XS Ineff= 2 , 0
                          459.04         2824.62
Permanent Ineff=
       F       F
Bank Sta=314.1,441
XS Rating Curve= 0 ,0
Exp/Cntr(USF)=0,0
Exp/Cntr=0.3,0.1

Type RM Length L Ch R = 1 ,4218    ,319.7,326.3,335.6
XS GIS Cut Line= 4
2178424.78213343497016.4037940762178734.03769573497057.297091571
2178956.39500086497141.6395176542179084.18655553497208.091126082
#Sta/Elev= 30
       0  2913.8    23.6 2894.85    63.9 2868.69      76 2863.24    92.8 2853.24
   108.3 2847.46   136.6 2833.42   176.9 2829.18   197.1 2819.24   209.2 2817.31
   229.4    2817   249.5 2807.69   261.7  2809.8   339.9 2811.84   356.9  2804.6
  393.912803.545     433 2801.51     464 2801.53  470.382803.544   481.1 2811.23
   489.6 2819.95     511 2837.83   537.2 2855.15   546.1 2862.83     554 2865.42
   617.1 2874.25   641.2 2880.18     662 2888.47   682.7 2901.67   693.8 2906.45
#Mann= 5 ,-1,0
       0      .1       0     170     .06       0     270      .1       0
  393.91    .045       0  470.38      .1       0
#XS Ineff= 2 , 0
          339.21 2816.73
Permanent Ineff=
       F       F
Bank Sta=393.91,470.38
XS Rating Curve= 0 ,0
Exp/Cntr(USF)=0,0
Exp/Cntr=0.3,0.1

Type RM Length L Ch R = 1 ,3892    ,321.6,353,377.5
XS GIS Cut Line= 2
2178383.81570059497208.9839446742179024.87007357497581.015499663
#Sta/Elev= 30
       0 2867.22      15 2859.68    32.6 2852.95    92.9 2838.51   120.4 2834.37
   166.9 2824.18   199.4  2819.5   222.4 2810.39   236.3 2812.44   247.4 2810.52
   275.5 2810.78   296.4 2800.35   303.2 2797.63   398.1 2797.53   402.8 2797.86
   408.2 2800.36     412 2802.27   430.6 2819.22   442.3 2832.44   453.6 2840.85
   476.8 2849.82   494.5 2859.85   509.6 2862.15   518.4 2866.15   568.1 2894.95
   606.3 2913.15   638.4  2932.8   664.7 2953.32   717.3 2972.08   741.2 2987.12
#Mann= 5 ,-1,0
       0      .1       0     130     .07       0     250     .06       0
   296.4    .045       0   408.2      .1       0
Bank Sta=296.4,408.2
XS Rating Curve= 0 ,0
Exp/Cntr(USF)=0,0
Exp/Cntr=0.3,0.1

Type RM Length L Ch R = 1 ,3539    ,546.5,545.5,541.4
XS GIS Cut Line= 4
2178289.32308548497305.2127076332178422.22630233497553.128323695
2178501.45706623  497706.47818932178555.12951919497821.490588504
#Sta/Elev= 30
       0 2864.35    10.9 2860.05    54.4 2847.65      68 2844.39    93.7 2840.77
     135 2831.91   167.5  2821.6   181.5 2820.41   199.7 2816.68   226.9 2814.73
   243.1 2804.96   249.6 2802.71   288.7 2804.19   312.9 2803.39   330.9 2799.37
   348.1 2793.68   362.9  2793.5   383.7 2791.65     425 2791.53   429.9 2792.19
  431.512793.595   465.7 2823.79     479 2834.26   487.8 2840.12   498.2 2849.11
   509.9 2861.74   518.7  2867.1     536 2881.36   571.6 2914.57580.8205 2920.94
#Mann= 5 ,-1,0
       0      .1       0     170     .06       0  281.29      .1       0
   362.9    .045       0  431.51      .1       0
Bank Sta=362.9,431.51
XS Rating Curve= 0 ,0
Exp/Cntr(USF)=0,0
Exp/Cntr=0.3,0.1

Type RM Length L Ch R = 1 ,2993    ,524.3,494.9,464.4
XS GIS Cut Line= 4
2177849.72013741 497519.902519482177908.50425256497675.808216179
 2178008.1816652497928.8354944282178064.40994925498077.073697846
#Sta/Elev= 30
       0 2893.17    48.4 2865.38    61.2 2860.94    77.4 2852.72   108.2 2840.26
   112.5 2837.47   121.1 2829.14   158.1 2801.37   185.3 2800.53     198 2790.41
  203.952787.215   211.1 2785.95   307.6 2785.92   348.7 2785.92  353.752787.216
   358.6 2788.81   383.1 2788.57   405.8 2795.29   411.1 2798.71   421.7 2807.91
   454.3 2831.04   464.6 2835.13   490.3 2849.27   511.7 2858.94   537.3 2874.04
   550.2 2877.68   554.4 2880.34   575.8 2889.44   580.1 2891.84597.1167 2904.95
#Mann= 4 ,-1,0
       0      .1       0      40     .06       0  203.95    .045       0
  353.75      .1       0
Bank Sta=203.95,353.75
XS Rating Curve= 0 ,0
Exp/Cntr(USF)=0,0
Exp/Cntr=0.3,0.1

Type RM Length L Ch R = 1 ,2498    ,473.6,469.1,464.6
XS GIS Cut Line= 4
2177399.89386497 497893.053859122177497.01544652497995.287102857
2177665.70029868498174.1952793962177793.49185335498304.542665161
#Sta/Elev= 30
       0 2865.02    14.4 2861.69    25.8 2857.89    56.9 2841.78    66.4 2837.91
    77.4 2829.18    93.3 2819.34   110.8 2812.08   121.6 2805.82   132.6 2794.54
   139.8 2789.06   143.6 2788.22   154.6 2789.65   168.9 2788.94   174.8  2786.4
  182.122779.453   186.4 2778.51   285.6 2778.22  290.772779.453   302.9 2784.91
     325 2799.43   363.5 2809.95     380 2815.51   430.4 2841.93     470 2861.03
   491.9 2872.89   501.1 2875.65   525.5 2886.76   557.6 2899.34569.4439 2904.83
#Mann= 4 ,-1,0
       0      .1       0      80     .06       0  182.12    .045       0
  290.77      .1       0
Bank Sta=182.12,290.77
XS Rating Curve= 0 ,0
Exp/Cntr(USF)=0,0
Exp/Cntr=0.3,0.1

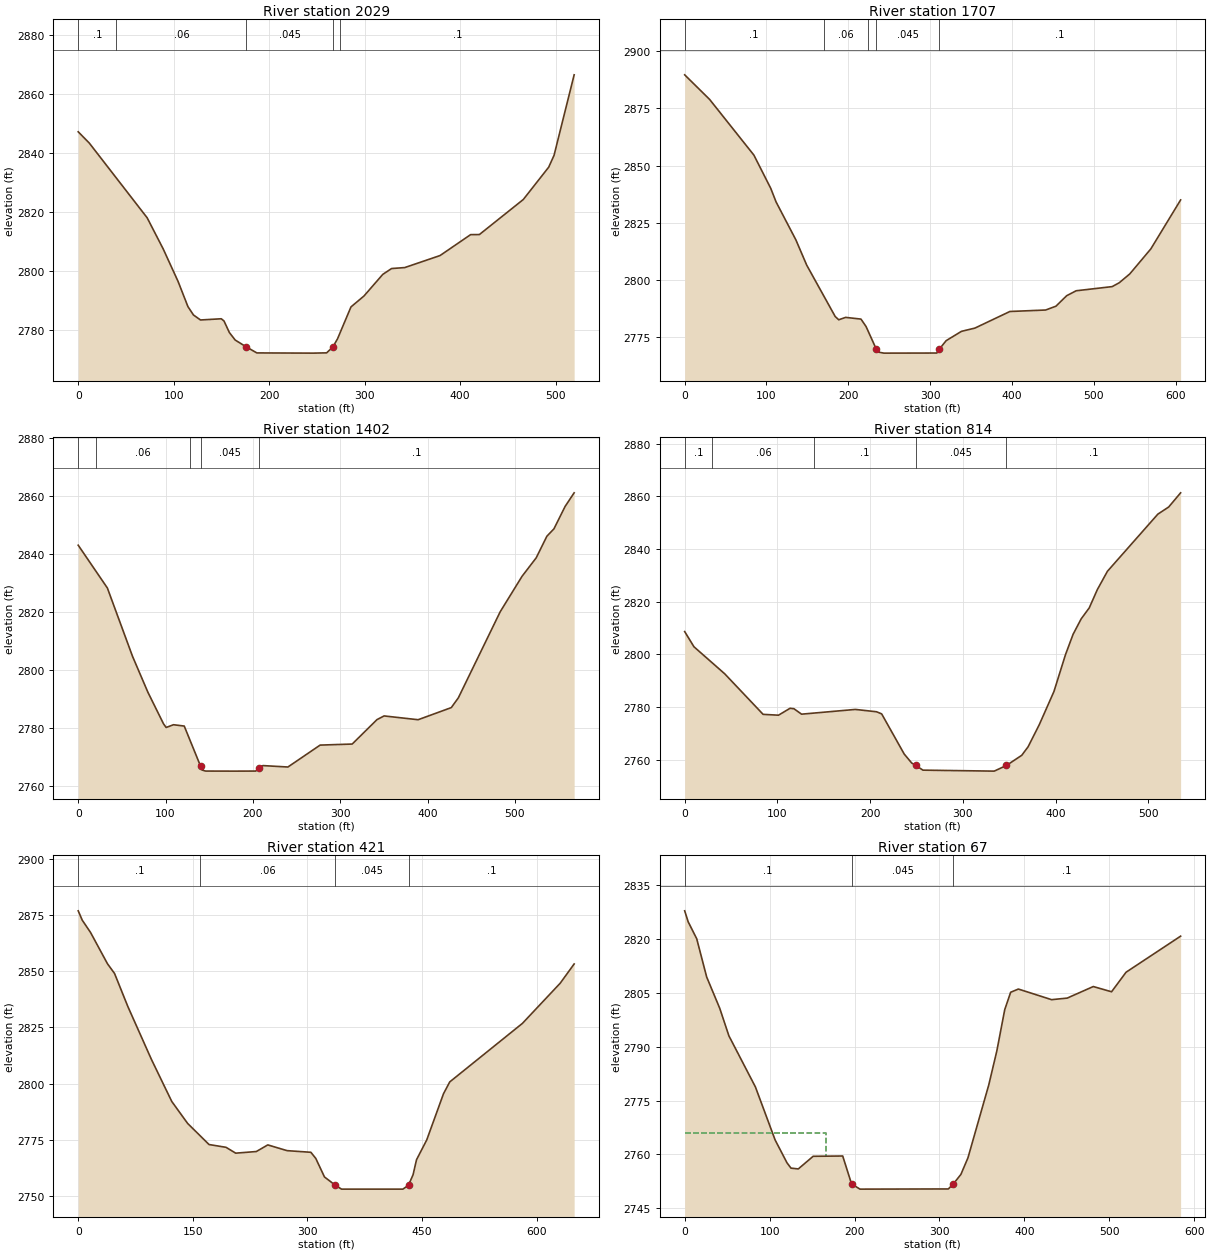
Type RM Length L Ch R = 1 ,2029    ,343,322.2,304.3
XS GIS Cut Line= 4
2177088.08247157498253.4260432922177174.98072874498342.880131562
2177305.32811451498463.0041929532177494.45961542498570.349098877
#Sta/Elev= 30
       0 2847.11    11.6 2843.29    72.2 2817.96    88.9 2807.47   104.6 2796.37
   114.9 2787.85   120.7    2785   128.1  2783.3   149.8 2783.71   152.7 2782.96
   158.3 2779.06   164.4  2776.5  176.032774.176   187.1 2772.13     246 2772.06
   260.2 2772.15  266.782774.175   271.6 2776.91   285.7 2787.73   299.3 2791.43
     319 2798.76   328.2 2800.74     342 2801.07     379 2805.15     411 2812.24
   420.2 2812.27   466.2 2824.16   492.8 2835.12   498.4 2839.14519.4416 2866.43
#Mann= 5 ,-1,0
       0      .1       0      40     .06       0  176.03    .045       0
  266.78     .06       0  274.71      .1       0
Bank Sta=176.03,266.78
XS Rating Curve= 0 ,0
Exp/Cntr(USF)=0,0
Exp/Cntr=0.3,0.1

Type RM Length L Ch R = 1 ,1707    ,312.4,305,298.8
XS GIS Cut Line= 3
2176816.36832276498569.026464889 2176974.4064186498640.637477066
2177378.14436656498796.206227659
#Sta/Elev= 30
       0  2889.6    30.5 2878.86    84.6 2854.57   105.2 2840.07   111.7 2834.14
     136 2817.52   149.1 2806.59     184 2784.12   188.3 2782.71   196.8 2783.75
   215.5    2783   221.7 2779.77   234.1 2769.98   237.2 2768.57   243.4 2768.15
   308.3 2768.19   311.4 2769.94   319.6 2773.59   338.3 2777.65   354.8 2779.08
   397.5 2786.32   441.2 2786.96   453.8 2788.63   466.9  2793.2   478.5 2795.36
   522.6 2797.18   531.2 2798.87   544.1 2802.73   569.8 2813.64   606.2    2835
#Mann= 5 ,-1,0
       0      .1       0     170     .06       0  223.51      .1       0
   234.1    .045       0   311.4      .1       0
Bank Sta=234.1,311.4
XS Rating Curve= 0 ,0
Exp/Cntr(USF)=0,0
Exp/Cntr=0.3,0.1

Type RM Length L Ch R = 1 ,1402    ,590.1,587.9,590.7
XS GIS Cut Line= 4
 2176804.3852202498917.9421275822176906.61846393498951.167931797
2177093.19413375498992.0612292922177359.00056747 499035.51035788
#Sta/Elev= 30
       0    2843    33.4 2828.22    62.2 2804.62    79.7 2792.29    97.6 2781.37
   100.7 2780.06   109.1 2781.01   121.4 2780.55  140.232766.608   141.8 2765.37
   145.9 2765.01   178.7 2764.99   203.3 2765.01   207.4 2766.06   211.5  2766.9
   240.1 2766.41     277 2773.98   313.7 2774.34   342.1 2782.78   350.2 2784.05
   389.2 2782.74   427.2 2786.93   435.3 2790.33   483.2 2820.04   508.2 2832.27
   524.4 2838.65   536.6  2846.1   544.7 2848.65   557.5  2856.4567.8356 2861.09
#Mann= 5 ,-1,0
       0      .1       0      20     .06       0   127.5      .1       0
  140.23    .045       0   207.4      .1       0
Bank Sta=140.23,207.4
XS Rating Curve= 0 ,0
Exp/Cntr(USF)=0,0
Exp/Cntr=0.3,0.1

Type RM Length L Ch R = 1 ,814     ,374.9,393.1,410.5
XS GIS Cut Line= 4
2176694.48448318499487.8924614162176873.39265972499536.453252191
2177103.41745813499572.2348874992177210.76236405 499618.23984718
#Sta/Elev= 30
       0 2808.61      10 2802.85    43.2 2792.58    84.6 2777.19   101.2 2776.87
   113.7  2779.5   117.8 2779.33   126.1 2777.26   184.1 2779.06     207 2778.17
   212.5 2777.36   236.8 2762.13   244.9 2758.71  249.412757.785     257 2756.01
   333.9 2755.64  347.062757.785   363.6 2761.65   370.4 2764.85   382.5 2773.27
   398.3 2785.84   410.8 2799.88     419  2807.6   427.7 2813.44   436.4  2817.6
   445.1 2824.52     456 2831.49   510.4 2853.19   522.1  2855.9534.9604 2861.28
#Mann= 5 ,-1,0
       0      .1       0      30     .06       0     140      .1       0
  249.41    .045       0  347.06      .1       0
Bank Sta=249.41,347.06
XS Rating Curve= 0 ,0
Exp/Cntr(USF)=0,0
Exp/Cntr=0.3,0.1

Type RM Length L Ch R = 1 ,421     ,345.6,353.7,358.9
XS GIS Cut Line= 4
2176497.68548899499748.5872329452176748.15693614499868.711294336
2176975.62590346499981.1678624462177080.41497829500034.840315408
#Sta/Elev= 30
       0 2876.78     5.3 2872.62    16.1  2867.2    38.3 2853.29    47.6 2848.94
    64.9 2834.35    95.9 2810.76   122.5 2792.11   143.2 2782.39   171.3 2772.99
   193.5 2771.76   206.2 2769.16   233.2 2769.89   248.2 2772.83   273.4 2770.28
   304.6 2769.55     311 2766.84   322.4  2758.6  336.452754.956   344.7 2753.19
   425.1 2753.19  432.452754.953   438.4  2759.6   442.9 2766.24   456.3 2775.05
   478.2 2795.53   486.4  2800.8   581.6 2826.81     631 2844.63649.2711 2853.18
#Mann= 4 ,-1,0
       0      .1       0     160     .06       0  336.45    .045       0
  432.45      .1       0
Bank Sta=336.45,432.45
XS Rating Curve= 0 ,0
Exp/Cntr(USF)=0,0
Exp/Cntr=0.3,0.1

Type RM Length L Ch R = 1 ,67      ,,,
XS GIS Cut Line= 4
2176428.67804946500073.1777818092176574.36042179500160.076038986
2176758.38026052500280.2001003772176855.50184207500448.884952543
#Sta/Elev= 30
       0 2827.89     4.1 2824.85    14.2 2820.09    25.9 2809.45    41.3 2800.72
    52.1 2793.04    83.3 2778.81   106.5 2764.04   120.5 2757.66   125.2 2756.18
   133.8 2755.96   151.3 2759.48   186.1 2759.56  196.512751.789   206.4 2750.33
   310.5 2750.38  316.422751.786   325.3 2754.44   333.6 2759.06   358.1 2779.37
   367.6 2788.84   376.9 2800.34   383.9  2805.2     393 2806.09   432.1 2803.13
   450.5 2803.57   481.2 2806.79   502.7 2805.33   519.8 2810.78584.0341 2820.83
#Mann= 3 ,-1,0
       0      .1       0  196.51    .045       0  316.42      .1       0
#XS Ineff= 2 , 0
          166.65 2765.88
Permanent Ineff=
       F       F
Bank Sta=196.51,316.42
XS Rating Curve= 0 ,0
Exp/Cntr(USF)=0,0
Exp/Cntr=0.3,0.1
LCMann Table=0

Chan Stop Cuts=-1
Use User Specified Reach Order=0
Composite Channel Slope=5